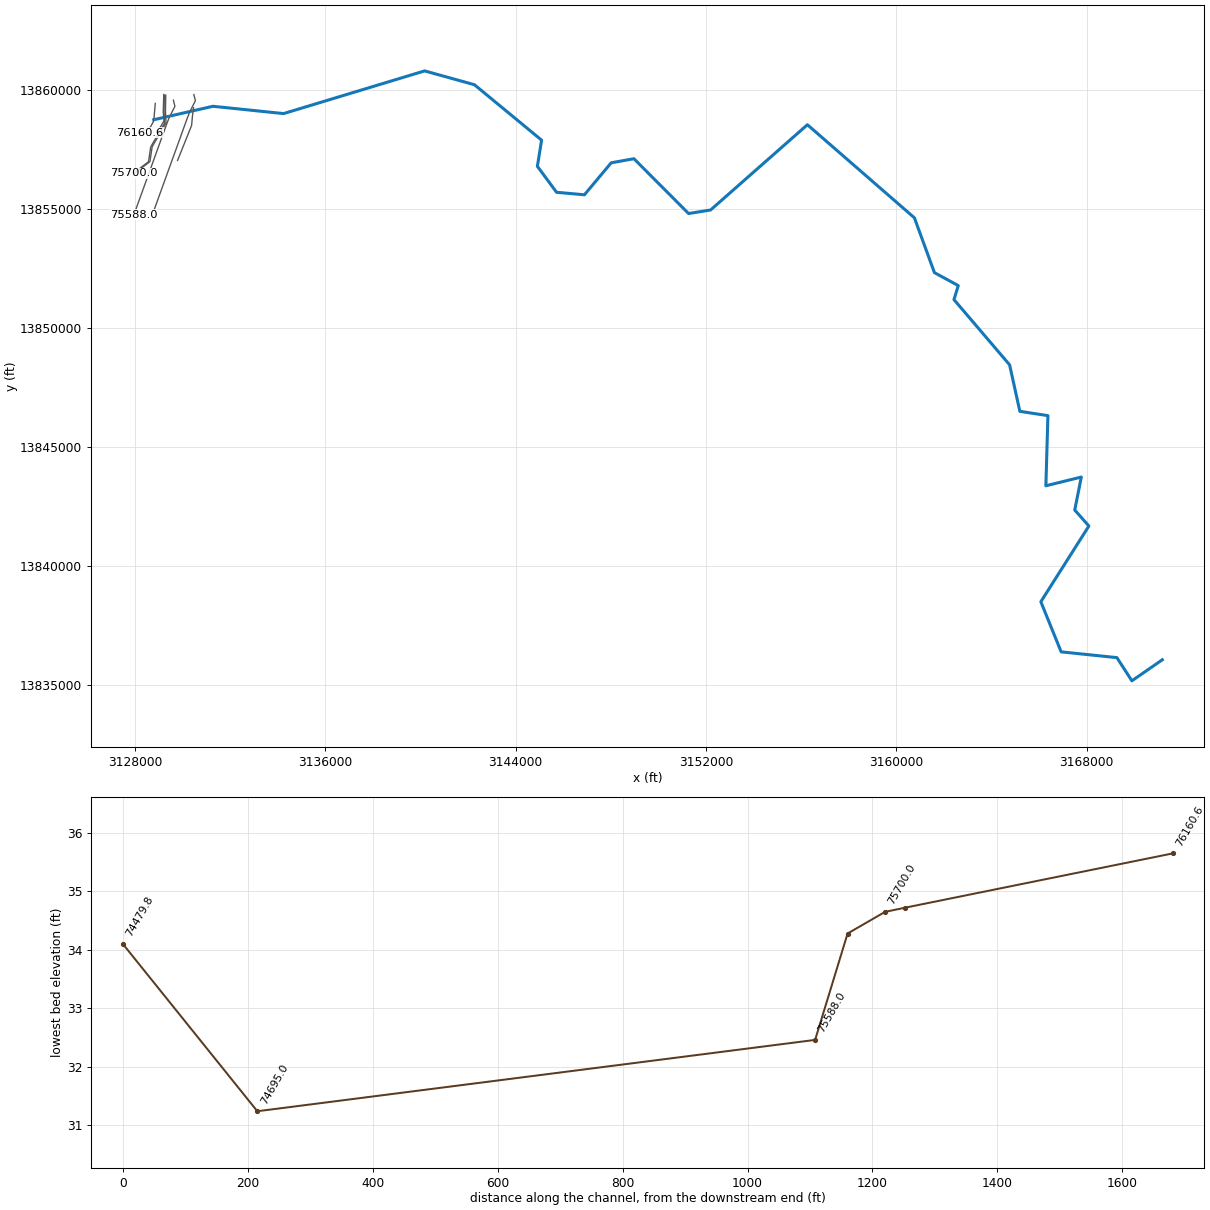
--- H100-00-00.prj (project) ---

Proj Title=H100-00-00
Current Plan=p01
Default Exp/Contr=.3,.1
English Units
Geom File=g01
Flow File=f02
Flow File=f01
Plan File=p02
Plan File=p01
Y Axis Title=Elevation
X Axis Title(PF)=Main Channel Distance
X Axis Title(XS)=Station
BEGIN DESCRIPTION:
HCFCD MODEL SUMMARY METADATA
The purpose of this summary is to document the high points of hydrologic and hydraulic models filed within the HCFCD Model and Map Management (M3) system.  The document includes references to the project that prompted the creation or update of the model.
DESCRIPTION OF PROJECT:
The following model was the hydraulic model which represented the effective condition of Harris County's watersheds.
PURPOSE OF PROJECT:
Development of effective models to support the National Flood Insurance Program.
HCFCD Watershed Unit ID: H
M3 Study Identifier: 2007_Effective_H
Engineer: HCFCD
Project Name: EffectiveFEMA Study for watershed Hunting Bayou (H)
Study Completion Date: 6/18/2007
FEMA Case Number: [No Data]
FEMA Approval Date: [No Date in Database]
Vertical Datum: NAVD 1988
Datum Note: 2001 ADJ
HYDRAULICS
HCFCD Unit No.:  H100-00-00
Hydraulic Program Name: HEC-RAS
Hydraulic Program Version: 3.0.1
Steady Hydraulic Model: Yes
Unsteady Hydraulic Model: No
Update1: The effective FEMA hydraulic model for unit number H100-00-00 has been updated by FEMA LOMR 10-06-3282P with an effective date of 7/7/2011.
Update2: The effective FEMA hydraulic model for unit number H100-00-00 has been updated by FEMA LOMR 16-06-1652P with an effective date of 8/26/2016.
END DESCRIPTION:
DSS Export Rating Curves= 0
DSS Export Rating Curve Sorted= 0
DSS Export Volume Flow Curves= 0
DXF OffsetX= 0
DXF OffsetY= 0
DXF ScaleX= 1
DXF ScaleY= 10

--- H100-00-00.p01 (plan) ---

Plan Title=FEMA Effective Multi-Profile 2016
Program Version=4.10
Short Identifier=Eff MP+LOMR
Geom File=g01
Flow File=f01
Subcritical Flow
K Sum by GR= 0
Std Step Tol= 0.01
Critical Tol= 0.01
Num of Std Step Trials= 20
Max Error Tol= 0.3
Flow Tol Ratio= 0.001
Split Flow NTrial= 30
Split Flow Tol= 0.02
Split Flow Ratio= 0.02
Log Output Level= 0
Friction Slope Method= 1
Unsteady Friction Slope Method= 2
Unsteady Bridges Friction Slope Method= 1
Parabolic Critical Depth
Global Vel Dist= 0 , 0 , 0
Global Log Level= 0
CheckData=True
Encroach Param=-1 ,0,0, 0
BEGIN DESCRIPTION:
FEMA Effective June 2007 + LOMR 10-06-3282P +
LOMR 16-06-1652P
END DESCRIPTION:
Computation Interval=1HOUR
Output Interval=1HOUR
Run HTab= 0
Run UNet= 0
Run PostProcess= 0
Run WQNet= 0
UNET Theta= 1
UNET Theta Warmup= 1
UNET ZTol= 0.02
UNET ZSATol= 0.1
UNET MxIter= 20
UNET MaxInSteps= 20
UNET DtIC= 0
UNET DtMin= 0
UNET MaxCRTS= 20
UNET WFStab= 2
UNET SFStab= 1
UNET WFX= 1
UNET SFX= 1
UNET DSS MLevel= 4
UNET DZMax Abort= 100
UNET Convert EG Bridges=-1
UNET Use Existing IB Tables=-1
UNET Froude Reduction=False
UNET Froude Limit= 1
UNET Froude Power= 10
UNET Time Slicing=0,0, 5
UNET Junction Losses=0
Instantaneous Interval=1HOUR
DSS File=dss
Write IC File= 0
IC Time=0,,
Write IC File at Sim End=0
Echo Input=False
Echo Parameters=False
Echo Output=False
Write Detailed= 0
WQ AD Non Conservative
WQ ULTIMATE=-1
WQ Max Comp Step=1HOUR
WQ Output Interval=15MIN
WQ Output Selected Increments= 0
WQ Output face flow=0
WQ Output face velocity=0
WQ Output face area=0
WQ Output face dispersion=0
WQ Output cell volume=0
WQ Output cell surface area=0
WQ Output cell continuity=0
WQ Output cumulative cell continuity=0
WQ Output face conc=0
WQ Output face dconc_dx=0
WQ Output face courant=0
WQ Output face peclet=0
WQ Output face adv mass=0
WQ Output face disp mass=0
WQ Output cell mass=0
WQ Output cell source sink temp=0
WQ Output cell source sink nsm=0
WQ Output MaxMinRange=-1
WQ Daily Max Min Mean=-1
WQ Daily Range=0
WQ Daily Time=0
WQ Create Restart=0
WQ Fixed Restart=0
WQ System Summary=0
WQ Use Fixed Temperature=0
Sorting and Armoring Iterations= 10
XS Update Threshold= 0.02
Hydraulics Update Threshold= 0.02
Energy Slope Method= 1
Volume Change Method= 0
XS Weighting Method= 0
Number of US Weighted Cross Sections= 1
Number of DS Weighted Cross Sections= 1
Upstream XS Weight=0.25
Main XS Weight=0.5
Downstream XS Weight=0.25
Number of DS XS's Weighted with US Boundary= 1
Upstream Boundary Weight= 1
Weight of XSs Associated with US Boundary= 0
Number of US XS's Weighted with DS Boundary= 1
Downstream Boundary Weight= 0.5
Weight of XSs Associated with DS Boundary= 0.5
Sediment Output Level= 4
Mass or Volume Output= 0
Output Increment Type= 1
Profile and TS Output Increment= 10
XS Output Flag= 0
XS Output Increment= 10
Disregard all LS=0
Disregard all Conn=0
Disregard all Breaches=0
Disregard all Pumps=0

--- H100-00-00.p02 (plan) ---

Plan Title=Effective Floodway 2016
Program Version=4.10
Short Identifier=FW+LOMR
Geom File=g01
Flow File=f02
Subcritical Flow
K Sum by GR= 0
Std Step Tol= 0.01
Critical Tol= 0.01
Num of Std Step Trials= 20
Max Error Tol= 0.3
Flow Tol Ratio= 0.001
Split Flow NTrial= 30
Split Flow Tol= 0.02
Split Flow Ratio= 0.02
Log Output Level= 0
Friction Slope Method= 1
Unsteady Friction Slope Method= 2
Unsteady Bridges Friction Slope Method= 1
Parabolic Critical Depth
Global Vel Dist= 0 , 0 , 0
Global Log Level= 0
CheckData=True
Encroach Param=-1 ,0,0, 2
Encroach River=H100-00-00
Encroach Reach=Reach - 1
Encroach Node=76160.6
       1 4816.23  5017.7
Encroach Node=75731.3
       1    4750    5100
Encroach Node=75700.0
       1    4750    5130
Encroach Node=75670.0
       1    4750    5130
Encroach Node=75640.0
       1    4750    5130
Encroach Node=75588.0
       1  4968.8  5031.6
Encroach Node=75141.5
       1  4968.8  5031.6
Encroach Node=74695.0
       1  4968.8  5031.6
Encroach Node=74479.8
       1    4970    5260
Encroach Node=73611.0
       1    4975    5325
Encroach Node=73463.2
       1    4975    5330
Encroach Node=73450.7
       1    4975    5330
Encroach Node=73438.2
       1    4975    5330
Encroach Node=73056.2
       1 4953.41    5365
Encroach Node=72791.0
       1    4865    5315
Encroach Node=72761.0
       1    4865    5315
Encroach Node=72731.0
       1    4865    5315
Encroach Node=72457.1
       1    4740    5325
Encroach Node=72446.6
       1    4740    5325
Encroach Node=72444.4
       1    4740    5325
Encroach Node=72415.4
       1    4740    5325
Encroach Node=72386.4
       1    4740    5325
Encroach Node=72109.2
       1    4835    5295
Encroach Node=72010.7
       1    4820    5330
Encroach Node=71999.7
       1    4820    5330
Encroach Node=71992.2
       1    4820    5330
Encroach Node=71938.2
       1    4820    5330
Encroach Node=71884.2
       1    4820    5390
Encroach Node=71370.5
       1    4885    5470
Encroach Node=71197.7
       1    4830    5420
Encroach Node=71165.7
       1    4830    5420
Encroach Node=71133.7
       1    4830    5420
Encroach Node=70171.3
       1    4645    5260
Encroach Node=69983.2
       1    4575    5260
Encroach Node=69950.2
       1    4575    5260
Encroach Node=69917.2
       1    4575    5260
Encroach Node=69017.4
       1    4675    5450
Encroach Node=68798.6
       1    4670    5370
Encroach Node=68786.1
       1    4670    5370
Encroach Node=68773.6
       1    4670    5370
Encroach Node=68347.6
       1    4760    5550
Encroach Node=68204.5
       1    4775    5575
Encroach Node=68147.0
       1    4775    5575
Encroach Node=68089.5
       1    4775    5575
Encroach Node=67289.6
       1  4928.2    5380
Encroach Node=66814.8
       1 4847.87 5338.92
Encroach Node=66802.8
       1  4845.1 5339.99
Encroach Node=66790.8
       1  4845.1 5339.99
Encroach Node=66314.8
       1    4875    5370
Encroach Node=65684.5
       1    4815    5150
Encroach Node=65672.5
       1    4815    5150
Encroach Node=65660.5
       1    4815    5150
Encroach Node=65412.0
       1    4920 5072.74
Encroach Node=65287.0
       1    4920 5072.74
Encroach Node=65162.0
       1    4920 5072.74
Encroach Node=64912.2
       1    4940    5086
Encroach Node=64886.7
       1    4940    5086
Encroach Node=64861.2
       1    4940    5086
Encroach Node=64429.5
       1    4645    5600
Encroach Node=64398.0
       1    4645    5600
Encroach Node=64366.5
       1    4645    5600
Encroach Node=64306.8
       1    4700    5620
Encroach Node=64295.3
       1    4700    5620
Encroach Node=64283.8
       1    4700    5620
Encroach Node=63241.1
       1    4740    5215
Encroach Node=63126.2
       1    4725    5200
Encroach Node=63100.7
       1    4725    5200
Encroach Node=63082.5
       1    4725    5215
Encroach Node=63023.8
       1    4725    5215
Encroach Node=62973.5
       1    4725    5225
Encroach Node=62948.0
       1    4725    5225
Encroach Node=62922.5
       1    4725    5225
Encroach Node=62520.2
       1    4650    5160
Encroach Node=61542.4
       1  4878.5    5220
Encroach Node=60409.1
       1    4790    5230
Encroach Node=59662.8
       1    4600  5185.5
Encroach Node=59587.6
       1    4600    5140
Encroach Node=59576.1
       1    4600    5140
Encroach Node=59564.6
       1    4600    5140
Encroach Node=59500.5
       1    4600    5160
Encroach Node=59475.0
       1    4600    5160
Encroach Node=59449.5
       1    4600    5160
Encroach Node=59389.0
       1    4600    5200
Encroach Node=59281.0
       1    4600    5200
Encroach Node=59173.0
       1    4600    5200
Encroach Node=59147.4
       1    4680    5250
Encroach Node=59117.9
       1    4680    5250
Encroach Node=59088.4
       1    4680    5250
Encroach Node=58574.2
       1    4750    5095
Encroach Node=57764.8
       1    4850    5120
Encroach Node=56929.6
       1  4938.7    5090
Encroach Node=56782
       1    4900    5095
Encroach Node=56771
       1    4900    5095
Encroach Node=56770
       1    4900    5095
Encroach Node=56765.3
       1    4900    5095
Encroach Node=56736.3
       1    4900    5095
Encroach Node=56707.3
       1    4900    5095
Encroach Node=56688.5
       1    4940    5050
Encroach Node=56657.5
       1    4940    5050
Encroach Node=56626.5
       1    4940    5050
Encroach Node=56623.5
       1    4940    5065
Encroach Node=56605.5
       1    4940    5065
Encroach Node=56587.5
       1    4940    5065
Encroach Node=56522.3
       1  4909.2    5137
Encroach Node=56391.6
       1  4942.5    5075
Encroach Node=56373.6
       1  4942.5    5075
Encroach Node=56355.6
       1  4942.5    5075
Encroach Node=56240.0
       1    4890 5029.39
Encroach Node=56220.0
       1    4890 5029.42
Encroach Node=56200.0
       1    4890 5029.42
Encroach Node=56193.9
       1  4937.3  5074.4
Encroach Node=56167.9
       1  4937.3  5074.4
Encroach Node=56141.9
       1  4937.3  5074.4
Encroach Node=55943.1
       1    4880    5220
Encroach Node=55888.1
       1    4880    5220
Encroach Node=55833.1
       1    4880    5220
Encroach Node=55781.5
       1    4935    5115
Encroach Node=55755.5
       1    4935    5115
Encroach Node=55729.5
       1    4935    5115
Encroach Node=55110.8
       1  4931.9    5150
Encroach Node=54487.3
       1    4650    5120
Encroach Node=54131.9
       1    4750 5152.57
Encroach Node=53643.9
       1 4803.29 5130.42
Encroach Node=53377.6
       1    4735    5120
Encroach Node=53357.6
       1    4735    5120
Encroach Node=53337.6
       1    4735    5120
Encroach Node=52853.01
       1    4800 5110.45
Encroach Node=52800.68
       1    4808 5120.79
Encroach Node=52720.99
       1    4790    5126
Encroach Node=52698.46
       1    4790    5140
Encroach Node=52584.97
       1    4780    5140
Encroach Node=52412.7
       1    4780    5130
Encroach Node=51482.9
       1    4800    5140
Encroach Node=50435.8
       1    4870    5120
Encroach Node=49468.0
       1    4920    5100
Encroach Node=49308.2
       1    4924    5078
Encroach Node=49266.2
       1    4924    5078
Encroach Node=49224.2
       1    4924    5078
Encroach Node=48627.4
       1    4940    5080
Encroach Node=47722.8
       1    4930    5070
Encroach Node=47592.2
       1  4933.2  5083.7
Encroach Node=47567.2
       1  4933.2  5083.7
Encroach Node=47542.2
       1  4933.2  5083.7
Encroach Node=47503.1
       1  4937.3  5070.3
Encroach Node=47419.4
       1  4937.3  5070.3
Encroach Node=47335.7
       1  4937.3  5070.3
Encroach Node=47289.8
       1  4926.3  5067.7
Encroach Node=47264.8
       1  4926.3  5067.7
Encroach Node=47239.8
       1  4926.3  5067.7
Encroach Node=47192.2
       1 4954.22 5066.72
Encroach Node=47181.2
       1 4954.22 5066.72
Encroach Node=47170.2
       1 4954.22 5066.72
Encroach Node=46680.2
       1  4926.4  5104.6
Encroach Node=45816.6
       1  4928.3  5054.6
Encroach Node=45692.7
       1  4928.3 5116.95
Encroach Node=45667.7
       1  4928.3 5116.95
Encroach Node=45642.7
       1  4928.3 5116.95
Encroach Node=45218.8
       1  4944.8  5064.9
Encroach Node=44455.6
       1  4944.8  5064.9
Encroach Node=43330.8
       1  4934.4  5055.2
Encroach Node=42322.3
       1  4945.9  5102.1
Encroach Node=41384.5
       1  4921.1  5062.5
Encroach Node=40316.2
       1  4926.3  5049.3
Encroach Node=39561.7
       1  4935.9  5062.3
Encroach Node=38631.4
       1    4900  5078.2
Encroach Node=37651.2
       1    4900    5060
Encroach Node=36829.1
       1    4920    5100
Encroach Node=36649.5
       1  4932.5  5097.8
Encroach Node=36599.5
       1  4932.5  5097.8
Encroach Node=36549.5
       1  4932.5  5097.8
Encroach Node=36003.7
       1    4920    5090
Encroach Node=35695.9
       1    4930    5130
Encroach Node=34749.7
       1    4890    5060
Encroach Node=33758.9
       1    4960    5100
Encroach Node=32885.9
       1  4950.6    5060
Encroach Node=31942.8
       1    4947    5060
Encroach Node=30991.0
       1    4950    5035
Encroach Node=29980.7
       1    4940    5045
Encroach Node=29025.3
       1  4931.3  5057.3
Encroach Node=28059.3
       1  4947.8  5108.1
Encroach Node=27048.3
       1  4913.5  5075.8
Encroach Node=26188.4
       1    4910    5080
Encroach Node=25273.1
       1    4945 5043.41
Encroach Node=25218.6
       1    4900 5043.41
Encroach Node=25208.1
       1    4900 5043.41
Encroach Node=25197.6
       1    4900 5043.41
Encroach Node=25166.0
       1  4882.9  5072.9
Encroach Node=25154.0
       1  4882.9  5072.9
Encroach Node=25142.0
       1  4882.9  5072.9
Encroach Node=25091.1
       1  4803.7  5077.7
Encroach Node=24913.1
       1  4803.7  5077.7
Encroach Node=24735.1
       1  4803.7  5077.7
Encroach Node=24245.3
       1  4919.8  5200.8
Encroach Node=23646.0
       1 4895.02 5090.53
Encroach Node=23635.0
       1 4895.02  5090.5
Encroach Node=23624.0
       1 4895.02 5090.29
Encroach Node=23273.1
       1    4900    5069
Encroach Node=22835.8
       1  4932.5    5069
Encroach Node=22364.5
       1 4918.58 5049.59
Encroach Node=22120.2
       1 4903.73  5042.5
Encroach Node=22007.5
       1    4900    5070
Encroach Node=21963.5
       1    4900    5070
Encroach Node=21919.5
       1    4900    5070
Encroach Node=21837.4
       1  4932.5    5102
Encroach Node=21821.4
       1  4947.4  5083.8
Encroach Node=21805.4
       1  4942.5    5092
Encroach Node=21505.9
       1 4951.57    5150
Encroach Node=21494.9
       1 4951.57    5150
Encroach Node=21483.9
       1 4951.57    5150
Encroach Node=20540.8
       1    4890    5080
Encroach Node=19521.0
       1  4957.6 5047.06
Encroach Node=19179.5
       1    4920    5050
Encroach Node=18474.8
       1    4850    5075
Encroach Node=17394.5
       1    4925    5160
Encroach Node=16874.1
       1    4750    5080
Encroach Node=16494.8
       1    4850    5120
Encroach Node=15572.4
       1    4950 5283.33
Encroach Node=15096.1
       1    4800    5060
Encroach Node=14552.2
       1 4852.14 5085.85
Encroach Node=13673.0
       1 4889.61 5092.29
Encroach Node=12705.5
       1 4878.92 5084.87
Encroach Node=11797.1
       1  4849.9    5045
Encroach Node=10723.3
       1 4882.04  5080.8
Encroach Node=9880.8
       1  4619.4 5094.06
Encroach Node=9683.0
       1  4900.2  5104.4
Encroach Node=9663.0
       1  4900.2  5104.4
Encroach Node=9643.0
       1  4900.2  5104.4
Encroach Node=8748.1
       1    4885    5580
Encroach Node=7806.7
       1    4930    5340
Encroach Node=7013.0
       1    4775    5075
Encroach Node=6259.7
       1 4749.48 5198.62
Encroach Node=5578.4
       1  4937.6 5304.44
Encroach Node=5550.9
       1  4937.6 5304.44
Encroach Node=5523.4
       1  4937.6 5304.44
Encroach Node=5009.7
       1    4800    5075
Encroach Node=3937.7
       1    4120  5104.5
Encroach Node=3378.9
       1 4180.64    5110
Encroach Node=2953.2
       1    4335    5200
Encroach Node=2939.7
       1    4335    5200
Encroach Node=2926.2
       1    4335    5200
Encroach Node=2925.2
       1    4335    5200
Encroach Node=2913.2
       1    4335    5200
Encroach Node=2910.3
       1    4335    5200
Encroach Node=2860.3
       1    4335    5200
Encroach Node=2810.3
       1    4335    5200
Encroach Node=1937.4
       1    4795    5205
BEGIN DESCRIPTION:
FEMA Effective June 2007 + LOMR 10-06-3282P +
16-06-1652P
END DESCRIPTION:
Computation Interval=1HOUR
Output Interval=1HOUR
Run HTab= 0
Run UNet= 0
Run PostProcess= 0
Run WQNet= 0
UNET Theta= 1
UNET Theta Warmup= 1
UNET ZTol= 0.02
UNET ZSATol= 0.1
UNET MxIter= 20
UNET MaxInSteps= 20
UNET DtIC= 0
UNET DtMin= 0
UNET MaxCRTS= 20
UNET WFStab= 2
UNET SFStab= 1
UNET WFX= 1
UNET SFX= 1
UNET DSS MLevel= 4
UNET DZMax Abort= 100
UNET Convert EG Bridges=-1
UNET Use Existing IB Tables=-1
UNET Froude Reduction=False
UNET Froude Limit= 1
UNET Froude Power= 10
UNET Time Slicing=0,0, 5
UNET Junction Losses=0
Instantaneous Interval=1HOUR
DSS File=dss
Write IC File= 0
IC Time=0,,
Write IC File at Sim End=0
Echo Input=False
Echo Parameters=False
Echo Output=False
Write Detailed= 0
WQ AD Non Conservative
WQ ULTIMATE=-1
WQ Max Comp Step=1HOUR
WQ Output Interval=15MIN
WQ Output Selected Increments= 0
WQ Output face flow=0
WQ Output face velocity=0
WQ Output face area=0
WQ Output face dispersion=0
WQ Output cell volume=0
WQ Output cell surface area=0
WQ Output cell continuity=0
WQ Output cumulative cell continuity=0
WQ Output face conc=0
WQ Output face dconc_dx=0
WQ Output face courant=0
WQ Output face peclet=0
WQ Output face adv mass=0
WQ Output face disp mass=0
WQ Output cell mass=0
WQ Output cell source sink temp=0
WQ Output cell source sink nsm=0
WQ Output MaxMinRange=-1
WQ Daily Max Min Mean=-1
WQ Daily Range=0
WQ Daily Time=0
WQ Create Restart=0
WQ Fixed Restart=0
WQ System Summary=0
WQ Use Fixed Temperature=0
Sorting and Armoring Iterations= 10
XS Update Threshold= 0.02
Hydraulics Update Threshold= 0.02
Energy Slope Method= 1
Volume Change Method= 0
XS Weighting Method= 0
Number of US Weighted Cross Sections= 1
Number of DS Weighted Cross Sections= 1
Upstream XS Weight=0.25
Main XS Weight=0.5
Downstream XS Weight=0.25
Number of DS XS's Weighted with US Boundary= 1
Upstream Boundary Weight= 1
Weight of XSs Associated with US Boundary= 0
Number of US XS's Weighted with DS Boundary= 1
Downstream Boundary Weight= 0.5
Weight of XSs Associated with DS Boundary= 0.5
Sediment Output Level= 4
Mass or Volume Output= 0
Output Increment Type= 1
Profile and TS Output Increment= 10
XS Output Flag= 0
XS Output Increment= 10
Disregard all LS=0
Disregard all Conn=0
Disregard all Breaches=0
Disregard all Pumps=0

--- H100-00-00.f01 (steady flow) ---

Flow Title=Effective Multi-Profile 2016
Version=Version 3.0.1  Mar 2001
Number of Profiles= 4
Profile Names=10PCT_10yr,2PCT_50yr,1PCT_100yr,0.2PCT_500yr
River Rch & RM=H100-00-00,Reach - 1       ,76160.6
     431     664     788    1156
River Rch & RM=H100-00-00,Reach - 1       ,75588
     563     870    1034    1523
River Rch & RM=H100-00-00,Reach - 1       ,74479.8
     582     901    1070    1577
River Rch & RM=H100-00-00,Reach - 1       ,73611
     675    1047    1245    1837
River Rch & RM=H100-00-00,Reach - 1       ,73056.2
     710    1102    1311    1936
River Rch & RM=H100-00-00,Reach - 1       ,72791
     766    1192    1412    2078
River Rch & RM=H100-00-00,Reach - 1       ,71370.5
     809    1261    1489    2187
River Rch & RM=H100-00-00,Reach - 1       ,71197.7
     872    1363    1604    2349
River Rch & RM=H100-00-00,Reach - 1       ,69983.2
     976    1529    1790    2612
River Rch & RM=H100-00-00,Reach - 1       ,68798.6
    1072    1685    1966    2859
River Rch & RM=H100-00-00,Reach - 1       ,68204.5
    1130    1779    2071    3007
River Rch & RM=H100-00-00,Reach - 1       ,67289.6
    1198    1888    2194    3180
River Rch & RM=H100-00-00,Reach - 1       ,66802.8
    1250    1971    2288    3313
River Rch & RM=H100-00-00,Reach - 1       ,66314.8
    1484    2340    2725    3943
River Rch & RM=H100-00-00,Reach - 1       ,65684.5
    1806    2848    3326    4810
River Rch & RM=H100-00-00,Reach - 1       ,65412
    2051    3235    3784    5469
River Rch & RM=H100-00-00,Reach - 1       ,64912.2
    2199    3469    4060    5868
River Rch & RM=H100-00-00,Reach - 1       ,64429.5
    2626    4085    4781    6757
River Rch & RM=H100-00-00,Reach - 1       ,62520.2
    2892    4397    5134    6989
River Rch & RM=H100-00-00,Reach - 1       ,59662.8
    3171    4726    5506    7234
River Rch & RM=H100-00-00,Reach - 1       ,56688.5
    3482    5130    5911    7646
River Rch & RM=H100-00-00,Reach - 1       ,56193.9
    3608    5303    6073    7846
River Rch & RM=H100-00-00,Reach - 1       ,55943.1
    4181    5829    6534    8193
River Rch & RM=H100-00-00,Reach - 1       ,44455.6
    4584    6190    6870    8470
River Rch & RM=H100-00-00,Reach - 1       ,30991
    4761    6416    7148    9057
River Rch & RM=H100-00-00,Reach - 1       ,29980.7
    4948    6656    7443    9681
River Rch & RM=H100-00-00,Reach - 1       ,29025.3
    5126    6882    7722   10270
River Rch & RM=H100-00-00,Reach - 1       ,28059.3
    5305    7111    8004   10866
River Rch & RM=H100-00-00,Reach - 1       ,27048.3
    5493    7351    8299   11490
River Rch & RM=H100-00-00,Reach - 1       ,26188.4
    5641    7656    8712   12160
River Rch & RM=H100-00-00,Reach - 1       ,21505.9
    5829    8044    9237   13012
River Rch & RM=H100-00-00,Reach - 1       ,18474.8
    5942    8279    9555   13527
River Rch & RM=H100-00-00,Reach - 1       ,15572.4
    6132    8670   10086   14387
River Rch & RM=H100-00-00,Reach - 1       ,9880.8
    6270    9002   10568   15234
Boundary for River Rch & Prof#=H100-00-00,Reach - 1       , 1
Up Type= 0
Dn Type= 3
Dn Slope=.0002
DSS Import GetInterval= 0
DSS Import GetPeak= 0
DSS Import FillOption= 0

--- H100-00-00.f02 (steady flow) ---

Flow Title=Effective Floodway 2016
Version=Version 3.0.1  Mar 2001
Number of Profiles= 2
Profile Names=1PCT_100yr,Floodway
River Rch & RM=H100-00-00,Reach - 1       ,76160.6
     788     788
River Rch & RM=H100-00-00,Reach - 1       ,75588
    1034    1034
River Rch & RM=H100-00-00,Reach - 1       ,74479.8
    1070    1070
River Rch & RM=H100-00-00,Reach - 1       ,73611
    1245    1245
River Rch & RM=H100-00-00,Reach - 1       ,73056.2
    1311    1311
River Rch & RM=H100-00-00,Reach - 1       ,72791
    1412    1412
River Rch & RM=H100-00-00,Reach - 1       ,71370.5
    1489    1489
River Rch & RM=H100-00-00,Reach - 1       ,71197.7
    1604    1604
River Rch & RM=H100-00-00,Reach - 1       ,69983.2
    1790    1790
River Rch & RM=H100-00-00,Reach - 1       ,68798.6
    1966    1966
River Rch & RM=H100-00-00,Reach - 1       ,68204.5
    2071    2071
River Rch & RM=H100-00-00,Reach - 1       ,67289.6
    2194    2194
River Rch & RM=H100-00-00,Reach - 1       ,66802.8
    2288    2288
River Rch & RM=H100-00-00,Reach - 1       ,66314.8
    2725    2725
River Rch & RM=H100-00-00,Reach - 1       ,65684.5
    3326    3326
River Rch & RM=H100-00-00,Reach - 1       ,65412
    3784    3784
River Rch & RM=H100-00-00,Reach - 1       ,64912.2
    4060    4060
River Rch & RM=H100-00-00,Reach - 1       ,64429.5
    4781    4781
River Rch & RM=H100-00-00,Reach - 1       ,62520.2
    5134    5134
River Rch & RM=H100-00-00,Reach - 1       ,59662.8
    5506    5506
River Rch & RM=H100-00-00,Reach - 1       ,56688.5
    5911    5911
River Rch & RM=H100-00-00,Reach - 1       ,56193.9
    6073    6073
River Rch & RM=H100-00-00,Reach - 1       ,55943.1
    6534    6534
River Rch & RM=H100-00-00,Reach - 1       ,44455.6
    6870    6870
River Rch & RM=H100-00-00,Reach - 1       ,30991
    7148    7148
River Rch & RM=H100-00-00,Reach - 1       ,29980.7
    7443    7443
River Rch & RM=H100-00-00,Reach - 1       ,29025.3
    7722    7722
River Rch & RM=H100-00-00,Reach - 1       ,28059.3
    8004    8004
River Rch & RM=H100-00-00,Reach - 1       ,27048.3
    8299    8299
River Rch & RM=H100-00-00,Reach - 1       ,26188.4
    8712    8712
River Rch & RM=H100-00-00,Reach - 1       ,21505.9
    9237    9237
River Rch & RM=H100-00-00,Reach - 1       ,18474.8
    9555    9555
River Rch & RM=H100-00-00,Reach - 1       ,15572.4
   10086   10086
River Rch & RM=H100-00-00,Reach - 1       ,9880.8
   10568   10568
Boundary for River Rch & Prof#=H100-00-00,Reach - 1       , 1
Up Type= 0
Dn Type= 1
Dn Known WS=8.78
Boundary for River Rch & Prof#=H100-00-00,Reach - 1       , 2
Up Type= 0
Dn Type= 1
Dn Known WS=9.78
DSS Import GetInterval= 0
DSS Import GetPeak= 0
DSS Import FillOption= 0

--- H100-00-00.g01 (geometry) ---

Geom Title=H100-00-00 2016
Program Version=4.10

River Reach=H100-00-00      ,Reach - 1
Reach XY= 30
       3128782.1     13858736.06       3131272.2     13859300.94
      3134241.97     13858994.28       3140171.5       13860787.
      3142265.24     13860206.45        3145089.       13857879.
      3144911.75       13856781.       3145718.5       13855689.
      3146889.98     13855584.18       3148015.5       13856927.
       3148971.5       13857099.      3151268.75     13854796.99
      3152194.25       13854946.       3156264.5       13858526.
       3160763.5       13854618.        3161605.       13852316.
      3162608.75       13851770.      3162427.25       13851182.
      3164766.25       13848444.      3165197.41     13846490.28
       3166377.5       13846310.      3166291.42     13843364.35
      3167781.75       13843731.      3167505.25       13842346.
      3168099.75       13841675.        3166080.       13838495.
       3166933.5       13836390.      3169277.47     13836147.93
      3169907.75       13835174.       3171186.5       13836057.

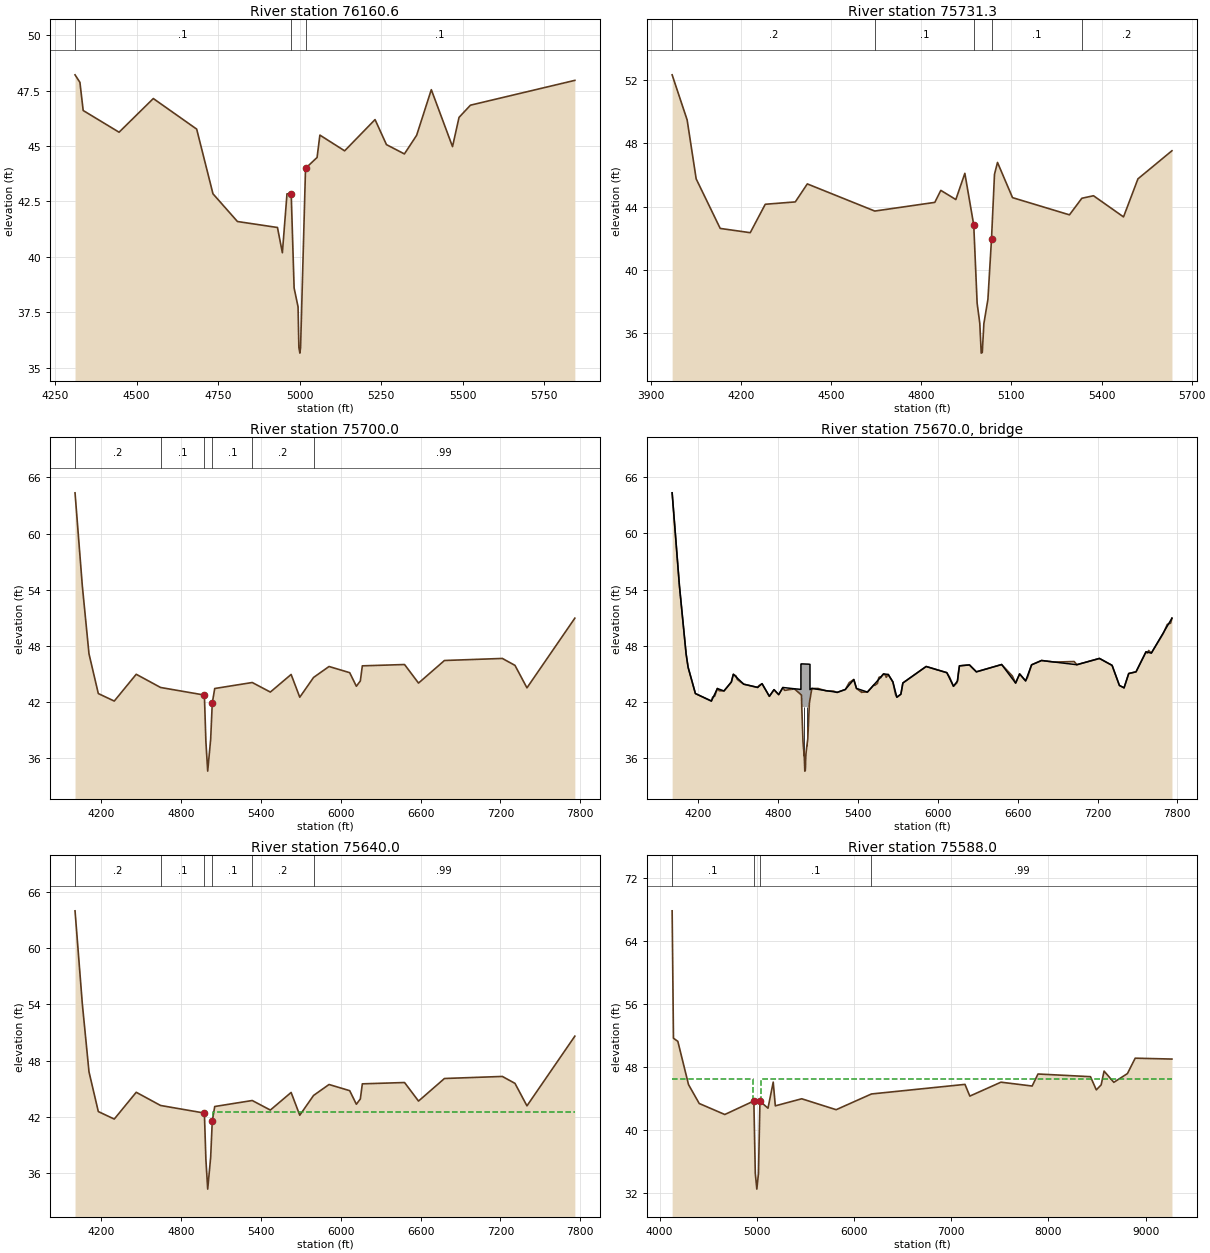
Type RM Length L Ch R = 1 ,76160.6 ,400.9,429.3,425.2
BEGIN DESCRIPTION:
Cross Section 76160.6
END DESCRIPTION:
XS GIS Cut Line= 6
      3128847.27     13859421.73       3128796.6     13858838.36
      3128771.25     13858659.21       3128695.1     13858526.37
      3128643.94     13858426.12      3128199.84     13858196.34
#Sta/Elev= 30
  4311.1   48.21  4326.1   47.87  4336.1    46.6  4446.1   45.62  4551.1   47.14
    4684   45.76    4734   42.84    4809   41.59  4931.7   41.32  4946.7   40.18
  4960.9   42.84  4973.8   42.84  4982.7   38.59  4994.8   37.74  4997.3   35.91
  5000.4   35.65  5002.5    35.9  5017.7   43.99  5053.1   44.48  5061.7   45.49
  5137.6   44.78  5230.8   46.19  5265.8   45.06  5320.8   44.64  5358.3   45.48
  5403.3   47.54  5468.3   44.97  5488.3   46.29  5523.3   46.84  5843.3   47.96
#Mann= 3 , 1 , 0
  4311.1      .1       0  4973.8    .035       0  5017.7      .1       0
Bank Sta=4973.8,5017.7
XS Rating Curve= 0 ,0
Exp/Cntr=0.3,0.1

Type RM Length L Ch R = 1 ,75731.3 ,20.7,31.3,87.9
BEGIN DESCRIPTION:
Cross Section 75731.3
END DESCRIPTION:
XS GIS Cut Line= 6
      3129203.12     13859794.22       3129181.8     13859051.65
      3129215.49     13858694.53      3129087.47      13858468.8
      3128976.29     13858317.19      3128903.11     13858228.86
#Sta/Elev= 30
  3970.6   52.35  4020.6   49.49  4050.6   45.76  4130.6   42.62  4230.6   42.35
  4280.6   44.15  4380.6    44.3  4420.6   45.44  4645.2   43.72    4845   44.27
    4865   45.03    4915   44.45    4945   46.11  4974.6   42.84  4985.9   37.88
  4994.7   36.62  4999.5   34.72    5003   34.76  5008.3   36.59  5021.8   38.13
  5033.8   41.98  5043.7   46.05  5053.7    46.8  5103.7   44.57  5293.2   43.48
  5334.4   44.53  5373.2   44.69  5473.2   43.35  5521.2   45.76  5634.4   47.54
#Mann= 5 ,-1 , 0
  3970.6      .2       0  4645.2      .1       0  4974.6    .035       0
  5033.8      .1       0  5334.4      .2       0
Bank Sta=4974.6,5033.8
XS Rating Curve= 0 ,0
Exp/Cntr=0.5,0.3

Type RM Length L Ch R = 1 ,75700.0 ,60,60,60
BEGIN DESCRIPTION:
Upstream Section of Bridge/Culvert/Weir
END DESCRIPTION:
XS GIS Cut Line= 6
      3129226.95     13859765.47      3129215.26     13859078.74
      3129238.61     13858595.71      3128655.05     13857595.74
      3128562.56     13856972.84      3127926.58     13856488.92
#Sta/Elev= 30
  4002.2   64.36  4057.2    54.4  4107.2   47.17  4177.2   42.93  4297.2   42.13
  4462.2   44.99  4645.2   43.58  4974.6   42.77  4985.9   37.81  4999.5   34.65
  5021.8   38.06  5033.8   41.91  5052.2   43.47  5334.4   44.11  5470.3   43.09
  5626.6   44.97  5691.6   42.54  5795.2   44.65  5911.6   45.82  6066.9   45.16
  6116.9   43.71  6146.9   44.28  6161.9   45.89  6479.2   46.03  6584.2   44.05
  6779.2   46.46  7214.3   46.68  7309.3   45.94  7399.3   43.54  7759.3   50.98
#Mann= 6 , 1 , 0
  4002.2      .2       0  4645.2      .1       0  4974.6    .035       0
  5033.8      .1       0  5334.4      .2       0  5795.2     .99       0
#XS Ineff= 2 , 0
       0  4964.6   42.11  5043.8       0   42.52
Permanent Ineff=
       F       F
Bank Sta=4974.6,5033.8
XS Rating Curve= 0 ,0
Exp/Cntr=0.5,0.3

Type RM Length L Ch R = 3 ,75670.0 ,,,
BEGIN DESCRIPTION:
Neches Road
Structure ID: H00-71
END DESCRIPTION:
Bridge Culvert--1,0,-1,-1, 0
Deck Dist Width WeirC Skew NumUp NumDn MinLoCord MaxHiCord MaxSubmerge Is_Ogee
10,40,2.6,0, 60, 60, , , 0.95, 0, 1,1,,
  4002.2  4057.2  4107.2  4122.2  4177.2  4297.2  4342.2  4392.2  4447.2  4462.2
  4540.6  4645.6  4678.1  4733.1  4768.1  4803.1  4834.5  4921.6 4970.19  4970.3
  4974.6  4976.8  5028.3  5038.4 5038.51  5052.2  5242.7  5304.3  5367.8  5387.8
  5470.3  5591.6  5626.6  5661.6  5691.6  5721.6  5736.6  5911.6  6066.9  6116.9
  6146.9  6161.9  6236.9  6289.2  6479.2  6584.2  6614.2  6659.2  6704.2  6779.2
  7044.3  7214.3  7309.3  7364.3  7399.3  7434.3  7489.3  7564.3  7604.3  7759.3
   64.34   54.38   47.15   45.72   42.91   42.11   43.45   43.19   44.14   44.97
   43.91   43.57   43.97   42.62   43.33    42.8   43.56   43.42   43.36   46.06
   46.08   46.08   46.05   46.03   43.33   43.46   43.04   43.35   44.41   43.46
   43.07   45.01   44.95   44.15   42.52   42.84   44.04    45.8   45.14   43.69
   44.26   45.87   45.97   45.23   46.01   44.03   45.01   44.26   45.98   46.44
   45.99   46.66   45.92   43.78   43.52   45.05   45.23   47.37   47.23   50.96
   64.34   54.38   47.15   45.72   42.91   42.11   43.45   43.19   44.14   44.97
   43.91   43.56   43.96   42.61   43.32   42.79   43.55   43.41    42.8    42.8
   42.75   41.48   41.45   42.28   42.29   43.45   43.03   43.34   44.41   43.46
   43.07   45.01   44.95   44.15   42.52   42.84   44.04    45.8   45.14   43.69
   44.26   45.87   45.97   45.23   46.01   44.03   45.01   44.26   45.98   46.44
   45.99   46.66   45.92   43.78   43.52   45.05   45.23   47.37   47.23   50.96
  4002.2  4057.2  4107.2  4122.2  4177.2  4297.2  4342.2  4392.2  4447.2  4462.2
  4540.6  4645.6  4678.1  4733.1  4768.1  4803.1  4834.5  4921.6 4970.19  4970.3
  4974.6  4976.8  5028.3  5038.4 5038.51  5052.2  5242.7  5304.3  5367.8  5387.8
  5470.3  5591.6  5626.6  5661.6  5691.6  5721.6  5736.6  5911.6  6066.9  6116.9
  6146.9  6161.9  6236.9  6289.2  6479.2  6584.2  6614.2  6659.2  6704.2  6779.2
  7044.3  7214.3  7309.3  7364.3  7399.3  7434.3  7489.3  7564.3  7604.3  7759.3
   64.34   54.38   47.15   45.72   42.91   42.11   43.45   43.19   44.14   44.97
   43.91   43.57   43.97   42.62   43.33    42.8   43.56   43.42   43.36   46.06
   46.08   46.08   46.05   46.03   43.33   43.46   43.04   43.35   44.41   43.46
   43.07   45.01   44.95   44.15   42.52   42.84   44.04    45.8   45.14   43.69
   44.26   45.87   45.97   45.23   46.01   44.03   45.01   44.26   45.98   46.44
   45.99   46.66   45.92   43.78   43.52   45.05   45.23   47.37   47.23   50.96
   64.34   54.38   47.15   45.72   42.91   42.11   43.45   43.19   44.14   44.97
   43.91   43.56   43.96   42.61   43.32   42.79   43.55   43.41    42.8    42.8
   42.75   41.48   41.45   42.28   42.29   43.45   43.03   43.34   44.41   43.46
   43.07   45.01   44.95   44.15   42.52   42.84   44.04    45.8   45.14   43.69
   44.26   45.87   45.97   45.23   46.01   44.03   45.01   44.26   45.98   46.44
   45.99   46.66   45.92   43.78   43.52   45.05   45.23   47.37   47.23   50.96
Pier Skew, UpSta & Num, DnSta & Num=  ,4994.5, 2 ,4994.5, 2 , 0 , 0 , 0 ,,
     1.1     1.1
   35.38   42.47
     1.1     1.1
   35.38   42.47
Pier Skew, UpSta & Num, DnSta & Num=  ,5014.6, 2 ,5014.6, 2 , 0 , 0 , 0 ,,
     1.1     1.1
   36.22   42.46
     1.1     1.1
   36.22   42.46
Abutment Skew #Up #Dn= , 2 , 2
  5028.3 5032.89
   40.13   41.53
  5028.3 5032.89
   40.13   41.53
BR Coef= 1 , 1 , 0 ,1.25, 0 ,,,0.8,0,2,0,
WSPro=,,,, 1 ,,,, 0 ,,,, 0 ,,,,-1 ,-1 ,-1 , 0 , 0 , 0 , 0 , 0
BR U #Sta/Elev= 127
  4002.2   64.34  4057.2   54.38  4107.2   47.15  4122.2   45.72  4177.2   42.91
  4297.2   42.11  4307.2   42.54  4322.2   42.63  4342.2   43.45  4357.2   43.21
  4392.2   43.19  4447.2   44.14  4462.2   44.97  4482.2   44.79  4492.2   44.42
  4515.6   44.16  4540.6   43.91  4645.2   43.56  4645.6   43.56  4653.1   43.74
  4678.1   43.96  4733.1   42.61  4768.1   43.32  4803.1   42.79  4834.5   43.55
  4847.6   43.25  4849.4   43.25  4887.9   43.34  4888.9   43.34  4918.7    43.4
  4921.6   43.41 4970.19    42.8  4970.3    42.8 4970.41    42.8  4974.6   42.75
  4975.6   42.15 4975.71   42.08 4975.83   42.01  4975.9   41.96  4976.8   41.42
  4985.9   37.79  4994.5   36.28  4994.7   36.53  4999.5   34.63    5003   34.67
  5004.9   35.21  5005.4   35.65  5008.3    36.5  5014.6   37.29  5021.8   38.04
  5028.3   40.13 5032.69   41.53  5032.8   41.57  5032.9    41.6  5033.8   41.89
 5038.29   42.27  5038.4   42.28 5038.51   42.29  5052.2   43.45  5053.4   43.45
  5094.9   43.45  5099.5   43.45  5150.2   43.24  5159.7    43.2    5199   43.18
  5215.9   43.17  5242.7   43.03  5304.3   43.34  5332.8   44.07  5334.4   44.09
  5367.8   44.41  5387.8   43.46  5427.8   43.03  5430.3   43.06  5470.3   43.07
  5520.3   43.86  5525.3   43.78  5545.3   43.99  5555.3   44.58  5560.3   44.68
  5570.3   44.59  5571.6   44.67  5591.6   45.01  5606.6   44.86  5611.6   44.65
  5626.6   44.95  5661.6   44.15  5681.6    42.8  5691.6   42.52  5721.6   42.84
  5736.6   44.04  5795.2   44.63  5911.6    45.8  6066.9   45.14  6086.9   44.68
  6116.9   43.69  6141.9   44.04  6146.9   44.26  6156.9   45.44  6161.9   45.87
  6236.9   45.97  6289.2   45.23  6479.2   46.01  6559.2   44.79  6584.2   44.03
  6614.2   45.01  6659.2   44.26  6674.2   44.66  6704.2   45.98  6779.2   46.44
  6874.3   46.27  7024.3   46.33  7044.3   45.99  7214.3   46.66  7309.3   45.92
  7364.3   43.78  7399.3   43.52  7434.3   45.05  7489.3   45.23  7564.3   47.37
  7574.3   47.23  7584.3   47.51  7604.3   47.23  7694.3   49.33  7724.3    50.3
  7749.3   50.43  7759.3   50.96
BR U #Mann= 6
  4002.2      .2  4645.2      .1  4974.6    .035  5033.8      .1  5334.4      .2
  5795.2     .99
BR U Banks=4974.6,5033.8
BR D #Sta/Elev= 127
  4002.2   64.34  4057.2   54.38  4107.2   47.15  4122.2   45.72  4177.2   42.91
  4297.2   42.11  4307.2   42.54  4322.2   42.63  4342.2   43.45  4357.2   43.21
  4392.2   43.19  4447.2   44.14  4462.2   44.97  4482.2   44.79  4492.2   44.42
  4515.6   44.16  4540.6   43.91  4645.2   43.56  4645.6   43.56  4653.1   43.74
  4678.1   43.96  4733.1   42.61  4768.1   43.32  4803.1   42.79  4834.5   43.55
  4847.6   43.25  4849.4   43.25  4887.9   43.34  4888.9   43.34  4918.7    43.4
  4921.6   43.41 4970.19    42.8  4970.3    42.8 4970.41    42.8  4974.6   42.75
  4975.6   42.15 4975.71   42.08 4975.83   42.01  4975.9   41.96  4976.8   41.42
  4985.9   37.79  4994.5   36.28  4994.7   36.53  4999.5   34.63    5003   34.67
  5004.9   35.21  5005.4   35.65  5008.3    36.5  5014.6   37.29  5021.8   38.04
  5028.3   40.13 5032.69   41.53  5032.8   41.57  5032.9    41.6  5033.8   41.89
 5038.29   42.27  5038.4   42.28 5038.51   42.29  5052.2   43.45  5053.4   43.45
  5094.9   43.45  5099.5   43.45  5150.2   43.24  5159.7    43.2    5199   43.18
  5215.9   43.17  5242.7   43.03  5304.3   43.34  5332.8   44.07  5334.4   44.09
  5367.8   44.41  5387.8   43.46  5427.8   43.03  5430.3   43.06  5470.3   43.07
  5520.3   43.86  5525.3   43.78  5545.3   43.99  5555.3   44.58  5560.3   44.68
  5570.3   44.59  5571.6   44.67  5591.6   45.01  5606.6   44.86  5611.6   44.65
  5626.6   44.95  5661.6   44.15  5681.6    42.8  5691.6   42.52  5721.6   42.84
  5736.6   44.04  5795.2   44.63  5911.6    45.8  6066.9   45.14  6086.9   44.68
  6116.9   43.69  6141.9   44.04  6146.9   44.26  6156.9   45.44  6161.9   45.87
  6236.9   45.97  6289.2   45.23  6479.2   46.01  6559.2   44.79  6584.2   44.03
  6614.2   45.01  6659.2   44.26  6674.2   44.66  6704.2   45.98  6779.2   46.44
  6874.3   46.27  7024.3   46.33  7044.3   45.99  7214.3   46.66  7309.3   45.92
  7364.3   43.78  7399.3   43.52  7434.3   45.05  7489.3   45.23  7564.3   47.37
  7574.3   47.23  7584.3   47.51  7604.3   47.23  7694.3   49.33  7724.3    50.3
  7749.3   50.43  7759.3   50.96
BR D #Mann= 6
  4002.2      .2  4645.2      .1  4974.6    .035  5033.8      .1  5334.4      .2
  5795.2     .99
BR D Banks=4974.6,5033.8
BC Design=,, 0 ,, 0 ,,,,,,
BC HTab HWMax=64.36
BC Use User HTab Curves=0
BC User HTab FreeFlow(D)= 0

Type RM Length L Ch R = 1 ,75640.0 ,52,52,52
BEGIN DESCRIPTION:
Downstream Section of Bridge/Culvert/Weir
END DESCRIPTION:
XS GIS Cut Line= 6
      3129286.76     13859770.31      3129275.06     13859083.58
      3129298.41     13858600.55      3128714.85     13857600.58
      3128622.36     13856977.68      3127986.38     13856493.75
#Sta/Elev= 30
  4002.2   63.99  4057.2   54.03  4107.2    46.8  4177.2   42.56  4297.2   41.76
  4462.2   44.62  4645.2   43.21  4974.6    42.4  4985.9   37.44  4999.5   34.28
  5021.8   37.69  5033.8   41.54  5052.2    43.1  5334.4   43.74  5470.3   42.72
  5626.6    44.6  5691.6   42.17  5795.2   44.28  5911.6   45.45  6066.9   44.79
  6116.9   43.34  6146.9   43.91  6161.9   45.52  6479.2   45.66  6584.2   43.68
  6779.2   46.09  7214.3   46.31  7309.3   45.57  7399.3   43.17  7759.3   50.61
#Mann= 6 , 1 , 0
  4002.2      .2       0  4645.2      .1       0  4974.6    .035       0
  5033.8      .1       0  5334.4      .2       0  5795.2     .99       0
#XS Ineff= 2 , 0
       0 4967.93   42.11 5040.47       0   42.52
Permanent Ineff=
       F       F
Bank Sta=4974.6,5033.8
XS Rating Curve= 0 ,0
Exp/Cntr=0.5,0.3

Type RM Length L Ch R = 1 ,75588.0 ,893,893,893
BEGIN DESCRIPTION:
Upstream Section of Bridge/Culvert/Weir
END DESCRIPTION:
XS GIS Cut Line= 5
      3129608.35     13859556.22      3129672.62     13859299.17
      3129427.88      13858815.6      3129332.07      13858570.1
      3127946.85     13854741.45
#Sta/Elev= 30
  4128.1   67.85  4141.8   51.65  4186.8   51.25  4296.8   45.75  4406.8   43.35
  4669.9   41.95  4968.8   43.67  4983.6   34.48  4999.4   32.46  5016.2   34.44
  5031.6   43.64  5114.3   42.75    5168   46.07  5189.6   43.05  5461.3   43.95
  5815.4   42.56  6178.6   44.56  7140.8   45.78  7190.8   44.29  7510.8   46.06
  7831.9   45.57  7891.9    47.1  8431.9   46.76  8491.9   45.08  8541.9   45.72
  8571.9   47.47  8671.9   46.04  8811.9   47.15  8891.9   49.11  9270.1      49
#Mann= 4 , 1 , 0
  4128.1      .1       0  4968.8    .015       0  5031.6      .1       0
  6178.6     .99       0
#XS Ineff= 2 , 0
       0    4960    46.5    5040       0    46.5
Permanent Ineff=
       F       F
Bank Sta=4968.8,5031.6
XS Rating Curve= 0 ,0
Exp/Cntr=0.5,0.3

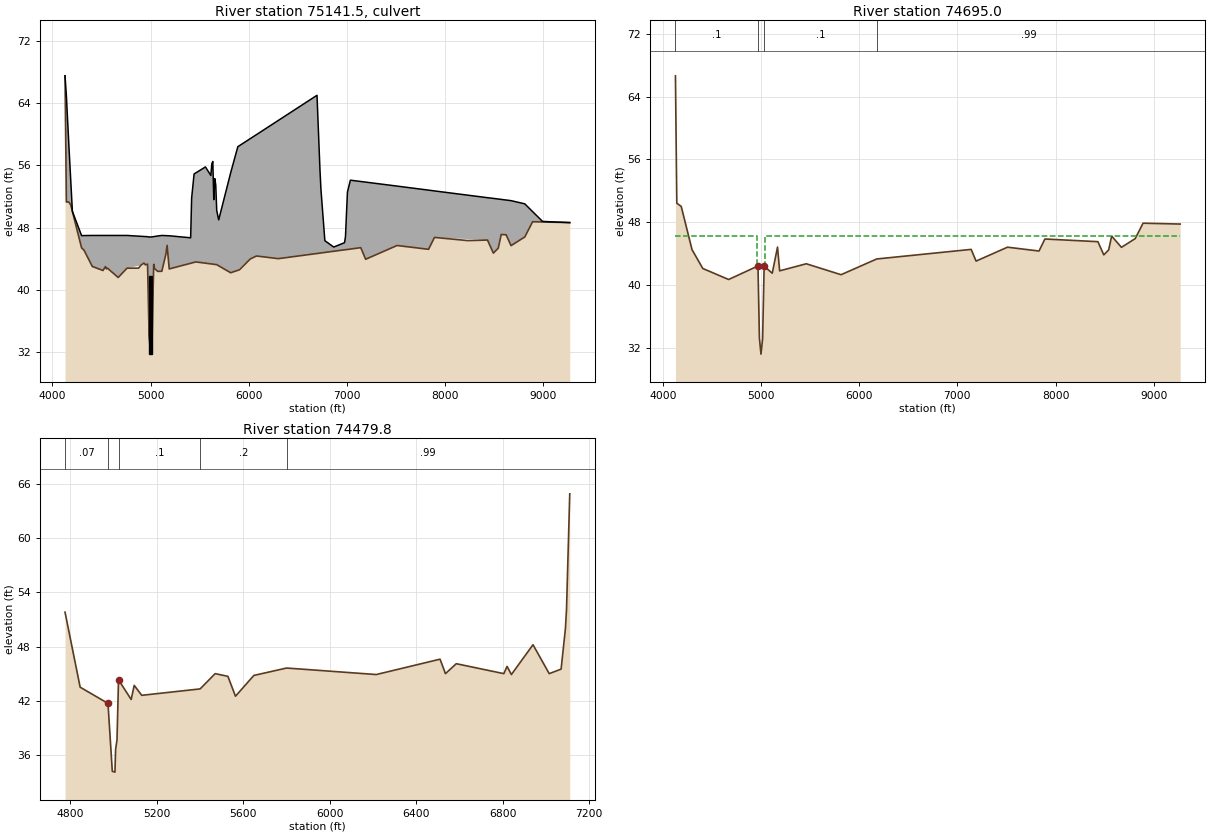
Type RM Length L Ch R = 2 ,75141.5 ,,,
BEGIN DESCRIPTION:
US HWY 59
Structure ID: HOO-70
END DESCRIPTION:
Bridge Culvert--1,0,-1,-1, 0
Deck Dist Width WeirC Skew NumUp NumDn MinLoCord MaxHiCord MaxSubmerge Is_Ogee
10,873,3,0, 60, 60, , , 0.95, 0, 1,1,,
  4128.1  4141.8  4166.8  4203.1  4296.8  4406.8  4514.9  4539.9  4669.9  4759.9
  4968.8  4982.7  4983.6  4999.4  5016.2  5031.6  5071.4  5114.3    5168  5189.6
  5407.9  5417.9  5442.9  5558.6  5613.6  5623.6  5633.6  5643.6  5653.6  5663.6
  5673.6  5693.6  5815.4  5888.6  6078.4  6300.8  6695.2  6725.2  6735.2  6775.2
  6865.2  6975.2  6985.2  7005.2  7035.2  7140.8  7190.8  7510.8  7831.9  7891.9
  8431.9  8491.9  8541.9  8571.9  8621.9  8671.9  8811.9  8891.9  8993.1  9270.1
    67.5   64.94    58.7   50.09   46.98      47      47      47      47      47
   46.84   46.81   46.81    46.8   46.82   46.85   46.93      47   46.97   46.96
    46.7    51.8    54.9    55.8    54.7    56.2    56.5    51.6    54.3    53.5
    50.2      49   55.04    58.4   59.95   61.77      65   55.48   52.94   46.33
   45.51   46.07   46.84   52.57    54.1   53.93   53.85   53.34   52.82   52.72
   51.85   51.76   51.68   51.63   51.55   51.47   51.06   50.06    48.8   48.65
    67.5    51.3    51.3   50.08    45.4      43    42.5      43    41.6    42.8
   43.32   35.16   34.13   32.11   34.09   43.29   42.39    42.4   45.72    42.7
   43.42   43.46   43.54   43.44   43.35   43.33   43.32    43.3   43.28   43.27
   43.25    43.1   42.21   42.52   44.36   44.02   44.68   44.73   44.75   44.82
   44.97   45.15   45.17    45.2   45.25   45.43   43.94   45.71   45.22   46.75
   46.41   44.73   45.37   47.12   47.09   45.69    46.8   48.76   48.73   48.65
  4128.1  4141.8  4166.8  4203.1  4296.8  4406.8  4514.9  4539.9  4669.9  4759.9
  4968.8  4982.7  4983.6  4999.4  5016.2  5031.6  5071.4  5114.3    5168  5189.6
  5407.9  5417.9  5442.9  5558.6  5613.6  5623.6  5633.6  5643.6  5653.6  5663.6
  5673.6  5693.6  5815.4  5888.6  6078.4  6300.8  6695.2  6725.2  6735.2  6775.2
  6865.2  6975.2  6985.2  7005.2  7035.2  7140.8  7190.8  7510.8  7831.9  7891.9
  8431.9  8491.9  8541.9  8571.9  8621.9  8671.9  8811.9  8891.9  8993.1  9270.1
    67.5   64.94    58.7   50.09   46.98      47      47      47      47      47
   46.84   46.81   46.81    46.8   46.82   46.85   46.93      47   46.97   46.96
    46.7    51.8    54.9    55.8    54.7    56.2    56.5    51.6    54.3    53.5
    50.2      49   55.04    58.4   59.95   61.77      65   55.48   52.94   46.33
   45.51   46.07   46.84   52.57    54.1   53.93   53.85   53.34   52.82   52.72
   51.85   51.76   51.68   51.63   51.55   51.47   51.06   50.06    48.8   48.65
    66.5    50.3    50.3   49.08    44.4      42    41.5      42    40.6    41.8
   42.32   34.16   33.13   31.11   33.09   42.29   41.39    41.4   44.72    41.7
   42.42   42.46   42.54   42.44   42.35   42.33   42.32    42.3   42.28   42.27
   42.25    42.1   41.21   41.52   43.36   43.02   43.68   43.73   43.75   43.82
   43.97   44.15   44.17    44.2   44.25   44.43   42.94   44.71   44.22   45.75
   45.41   43.73   44.37   46.12   46.09   44.69    45.8   47.76   47.73   47.65
BR Coef= 1 , 0 , 0 ,1.25, 0 ,,,0.8,-1,2,0,
WSPro=,,,, 1 ,,,, 0 ,,,, 0 ,,,,-1 ,-1 ,-1 , 0 , 0 , 0 , 0 , 0
Culvert=2,10,10,873,0.015,0.4,1,8,1,31.76,4990.7,29.42,4990.7,Culvert #1  , 0 ,10
Culvert Bottom n=0.015
Culvert=2,10,10,873,0.015,0.4,1,8,1,31.76,5001.8,29.42,5001.8,Culvert #2  , 0 ,10
Culvert Bottom n=0.015
Culvert=2,10,10,873,0.015,0.4,1,8,1,31.76,5012.2,29.42,5012.2,Culvert #3  , 0 ,10
Culvert Bottom n=0.015
BR U #Sta/Elev= 101
  4128.1    67.5  4141.8    51.3  4143.1    51.3  4166.8    51.3  4186.8    50.9
  4203.1   50.08  4208.1   49.83  4218.1   49.33  4296.8    45.4  4319.4   45.13
  4321.8    45.1  4406.8      43  4409.9      43  4514.9    42.5  4539.9      43
  4549.9    42.7  4559.9    42.8  4669.9    41.6  4759.9    42.8  4842.4    42.8
  4870.4    42.8  4877.4    42.8  4902.4    43.2  4932.6   43.45  4947.6   43.22
  4968.8   43.32  4974.2   40.34  4982.7   35.16  4983.6   34.13  4990.4   33.26
  4999.4   32.11  5005.4   32.82  5016.2   34.09  5017.3   34.98  5024.3   39.27
  5031.6   43.29  5042.8   42.74  5071.4   42.39  5107.7    42.4  5114.3    42.4
  5156.1   44.62    5168   45.72  5189.6    42.7  5297.7   43.06  5312.7   43.11
  5397.9   43.39  5407.9   43.42  5417.9   43.46  5422.9   43.47  5432.9   43.51
  5442.9   43.54  5461.3    43.6  5558.6   43.44  5613.6   43.35  5623.6   43.33
  5633.6   43.32  5643.1    43.3  5643.6    43.3  5653.6   43.28  5663.6   43.27
  5673.1   43.25  5673.6   43.25  5693.6    43.1  5703.6   43.03  5718.6   42.92
  5815.4   42.21  5888.6   42.52  5905.4   42.59  6015.4   43.98  6078.4   44.36
  6178.6   44.21  6300.8   44.02  6695.2   44.68  6725.2   44.73  6735.2   44.75
  6755.2   44.78  6775.2   44.82  6865.2   44.97  6965.2   45.14  6975.2   45.15
  6985.2   45.17  7005.2    45.2  7035.2   45.25  7140.8   45.43  7190.8   43.94
  7510.8   45.71  7831.9   45.22  7891.9   46.75  8231.9   46.34  8431.9   46.41
  8491.9   44.73  8541.9   45.37  8571.9   47.12  8621.9   47.09  8671.9   45.69
  8795.2   46.67  8811.9    46.8  8891.9   48.76  8993.1   48.73  9211.9   48.67
  9270.1   48.65
BR U #Mann= 4
  4128.1      .1  4968.8    .015  5031.6      .1  6178.6     .99
BR U Banks=4968.8,5031.6
BR D #Sta/Elev= 101
  4128.1    66.5  4141.8    50.3  4143.1    50.3  4166.8    50.3  4186.8    49.9
  4203.1   49.08  4208.1   48.83  4218.1   48.33  4296.8    44.4  4319.4   44.13
  4321.8    44.1  4406.8      42  4409.9      42  4514.9    41.5  4539.9      42
  4549.9    41.7  4559.9    41.8  4669.9    40.6  4759.9    41.8  4842.4    41.8
  4870.4    41.8  4877.4    41.8  4902.4    42.2  4932.6   42.45  4947.6   42.22
  4968.8   42.32  4974.2   39.34  4982.7   34.16  4983.6   33.13  4990.4   32.26
  4999.4   31.11  5005.4   31.82  5016.2   33.09  5017.3   33.98  5024.3   38.27
  5031.6   42.29  5042.8   41.74  5071.4   41.39  5107.7    41.4  5114.3    41.4
  5156.1   43.62    5168   44.72  5189.6    41.7  5297.7   42.06  5312.7   42.11
  5397.9   42.39  5407.9   42.42  5417.9   42.46  5422.9   42.47  5432.9   42.51
  5442.9   42.54  5461.3    42.6  5558.6   42.44  5613.6   42.35  5623.6   42.33
  5633.6   42.32  5643.1    42.3  5643.6    42.3  5653.6   42.28  5663.6   42.27
  5673.1   42.25  5673.6   42.25  5693.6    42.1  5703.6   42.03  5718.6   41.92
  5815.4   41.21  5888.6   41.52  5905.4   41.59  6015.4   42.98  6078.4   43.36
  6178.6   43.21  6300.8   43.02  6695.2   43.68  6725.2   43.73  6735.2   43.75
  6755.2   43.78  6775.2   43.82  6865.2   43.97  6965.2   44.14  6975.2   44.15
  6985.2   44.17  7005.2    44.2  7035.2   44.25  7140.8   44.43  7190.8   42.94
  7510.8   44.71  7831.9   44.22  7891.9   45.75  8231.9   45.34  8431.9   45.41
  8491.9   43.73  8541.9   44.37  8571.9   46.12  8621.9   46.09  8671.9   44.69
  8795.2   45.67  8811.9    45.8  8891.9   47.76  8993.1   47.73  9211.9   47.67
  9270.1   47.65
BR D #Mann= 4
  4128.1      .1  4968.8    .015  5031.6      .1  6178.6     .99
BR D Banks=4968.8,5031.6
BC Design=,, 0 ,, 0 ,,,,,,
BC HTab HWMax=67.85
BC Use User HTab Curves=0
BC User HTab FreeFlow(D)= 0

Type RM Length L Ch R = 1 ,74695.0 ,215.2,215.2,215.2
BEGIN DESCRIPTION:
Downstream Section of Bridge/Culvert/Weir
END DESCRIPTION:
XS GIS Cut Line= 5
      3130469.69     13859791.87      3130533.96     13859534.83
      3130289.22     13859051.26      3130193.41     13858805.76
       3128808.2      13854977.1
#Sta/Elev= 30
  4128.1   66.63  4141.8   50.43  4186.8   50.03  4296.8   44.53  4406.8   42.13
  4669.9   40.73  4968.8   42.45  4983.6   33.26  4999.4   31.24  5016.2   33.22
  5031.6   42.42  5114.3   41.53    5168   44.85  5189.6   41.83  5461.3   42.73
  5815.4   41.34  6178.6   43.34  7140.8   44.56  7190.8   43.07  7510.8   44.84
  7831.9   44.35  7891.9   45.88  8431.9   45.54  8491.9   43.86  8541.9    44.5
  8571.9   46.25  8671.9   44.82  8811.9   45.93  8891.9   47.89  9270.1   47.78
#Mann= 4 , 1 , 0
  4128.1      .1       0  4968.8    .015       0  5031.6      .1       0
  6178.6     .99       0
#XS Ineff= 2 , 0
       0    4960    46.3    5040       0    46.3
Permanent Ineff=
       F       F
Bank Sta=4968.8,5031.6
XS Rating Curve= 0 ,0
Exp/Cntr=0.5,0.3

Type RM Length L Ch R = 1 ,74479.8 ,880.2,868.8,574.8
BEGIN DESCRIPTION:
Cross Section 74479.8
END DESCRIPTION:
XS GIS Cut Line= 4
      3130455.21     13859244.59      3130409.83     13858888.03
      3130374.16     13858495.64       3129784.7     13857028.15
#Sta/Elev= 30
  4775.1    51.8  4845.1    43.5  4973.8   41.71  4993.8   34.19  5006.1    34.1
    5009   36.59  5015.5   37.66  5022.5   44.32  5081.1   42.14  5095.1    43.7
  5130.1    42.6  5400.1   43.31  5469.6      45  5528.6    44.7  5563.6    42.5
  5648.6    44.8  5800.1   45.62    6215    44.9    6510    46.6    6535      45
    6585    46.1    6805      45    6820    45.8    6840    44.9    6940    48.2
    7015      45    7070    45.5    7090      50    7095    52.1    7110    64.9
#Mann= 5 , 1 , 0
  4775.1     .07       0  4973.8    .035       0  5022.5      .1       0
  5400.1      .2       0  5800.1     .99       0
Bank Sta=4973.8,5022.5
XS Rating Curve= 0 ,0
Exp/Cntr=0.3,0.1