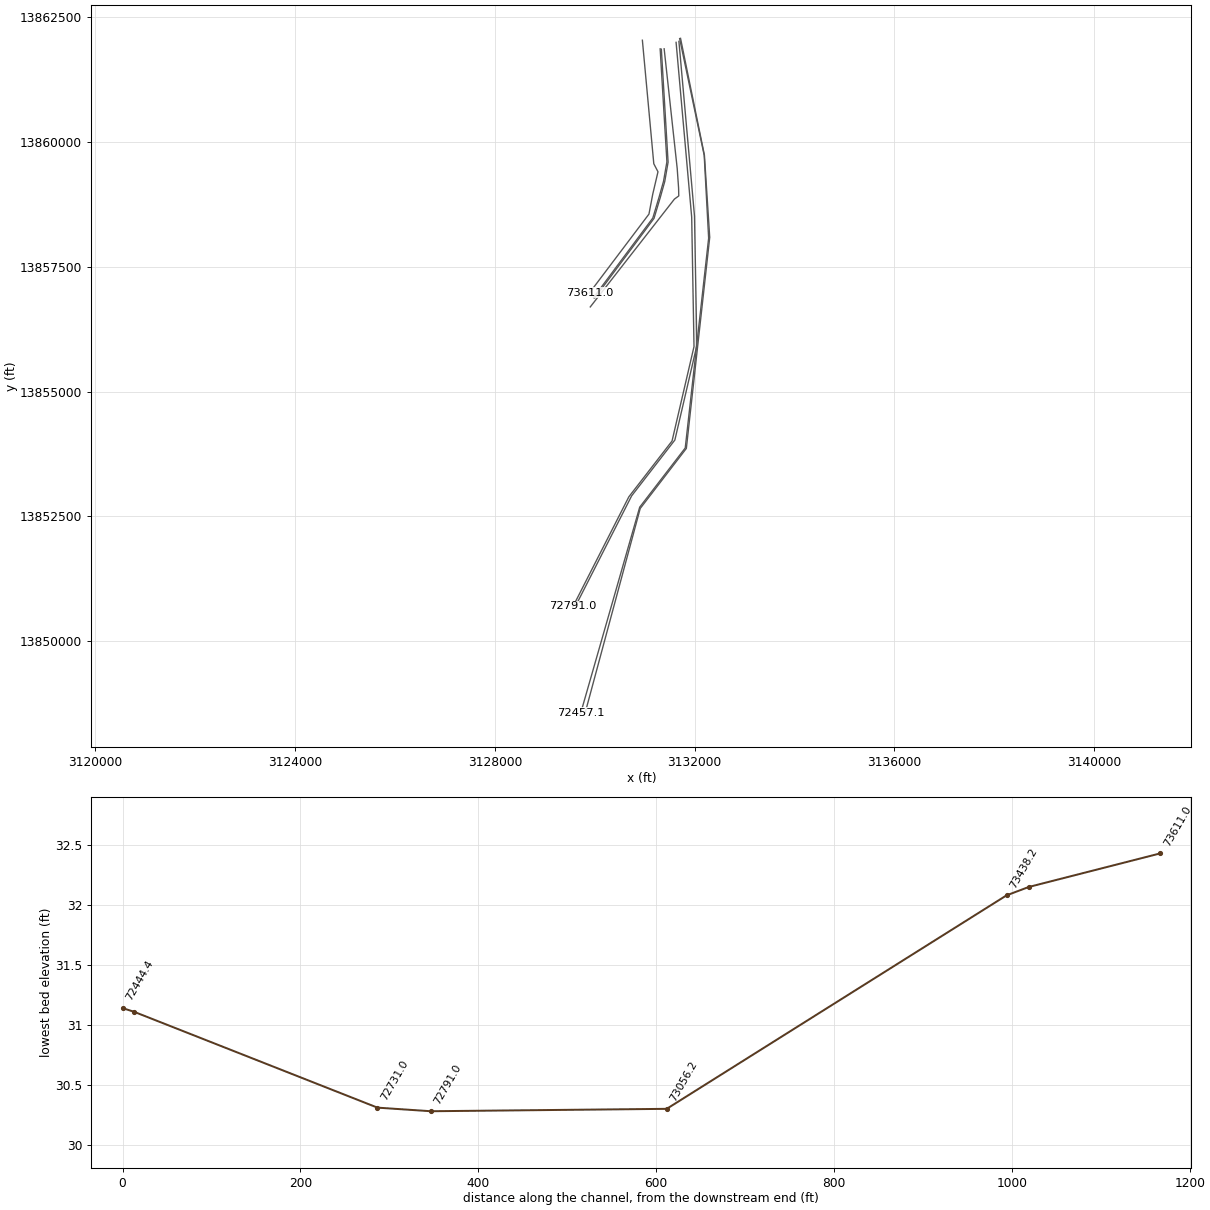
HEC-RAS study H100-00-00.prj: H100-00-00

--- H100-00-00.g01 (geometry) --- (continued)

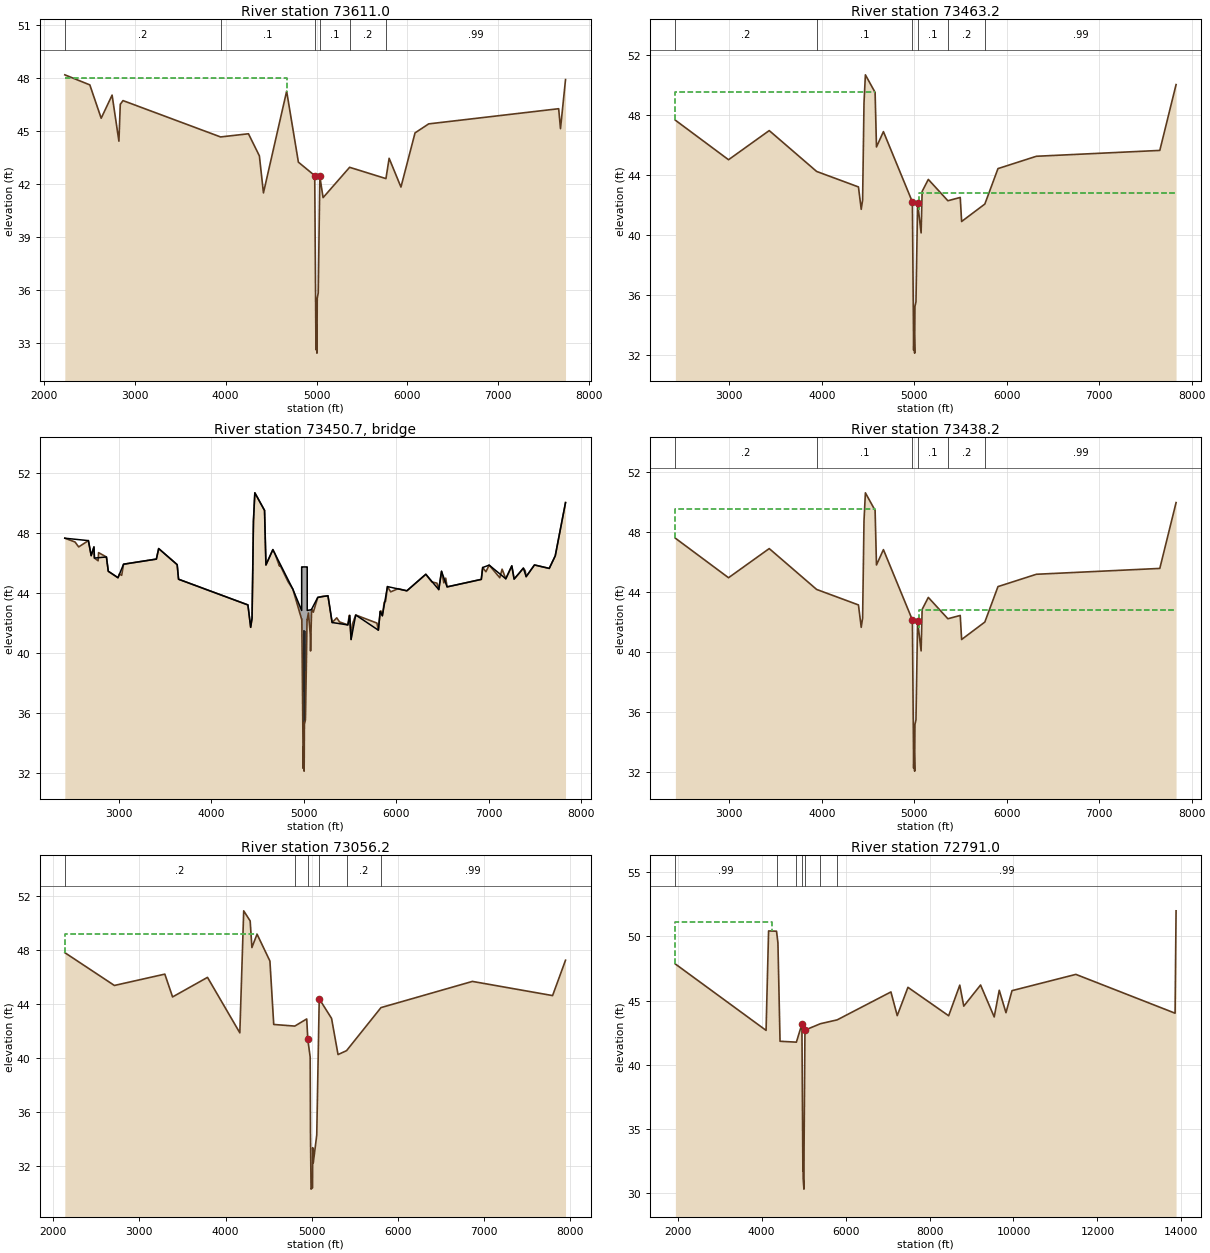
Type RM Length L Ch R = 1 ,73611.0 ,134.8,147.8,101.7
BEGIN DESCRIPTION:
Cross Section 73611.0 - Interpolated
END DESCRIPTION:
XS GIS Cut Line= 6
       3130953.8     13862034.24      3131182.45     13859560.42
      3131266.36     13859399.59      3131161.63     13858952.11
      3131085.47     13858552.24      3129895.51     13856975.63
#Sta/Elev= 30
    2231    48.2    2506   47.63    2631   45.74    2751   47.05    2826   44.44
    2841   46.53    2871   46.74  3944.3   44.68    4251   44.86    4371   43.61
    4416   41.51    4671   47.27  4800.4   43.25  4979.9   42.49  4993.5   32.62
  4997.5   34.04  5004.4   32.43  5007.6   35.54  5018.6   35.84  5036.2   42.44
  5071.8   41.24  5363.8   42.96  5763.3   42.32  5798.4   43.47  5928.4   41.84
  6083.4   44.91  6233.4   45.42  7663.4   46.28  7683.4   45.15  7738.7   47.93
#Mann= 6 ,-1 , 0
    2231      .2       0  3944.3      .1       0  4979.9    .035       0
  5036.2      .1       0  5363.8      .2       0  5763.3     .99       0
#XS Ineff= 2 , 0
       0    4673      48               0
Permanent Ineff=
       F       F
Bank Sta=4979.9,5036.2
XS Rating Curve= 0 ,0
Exp/Cntr=0.5,0.3

Type RM Length L Ch R = 1 ,73463.2 ,25,25,25
BEGIN DESCRIPTION:
Upstream Section of Bridge/Culvert/Weir
END DESCRIPTION:
XS GIS Cut Line= 6
      3131309.65     13861861.86      3131444.88     13859599.47
      3131377.52     13859210.56      3131289.37     13858896.07
      3131162.62     13858473.44      3129976.13     13856880.78
#Sta/Elev= 30
  2416.6   47.65  2991.6   45.02  3431.6   46.96  3944.3   44.24  4396.6   43.21
  4426.6   41.72  4441.6   42.34  4456.6    48.8  4471.6   50.67  4576.6    49.5
  4591.6   45.87  4666.6   46.89  4979.9   42.21  4993.5   32.34  4997.5   33.76
  5004.4   32.15  5007.6   35.26  5018.6   35.56  5036.2   42.16  5074.2   40.15
  5085.3   42.91  5152.1   43.71  5363.8   42.29  5497.4   42.51  5512.4   40.91
  5763.3   42.07  5905.7   44.43  6320.7   45.25  7655.7   45.64  7831.6   50.02
#Mann= 6 ,-1 , 0
  2416.6      .2       0  3944.3      .1       0  4979.9    .035       0
  5036.2      .1       0  5363.8      .2       0  5763.3     .99       0
#XS Ineff= 2 , 0
       0  4572.5   49.55    5046       0    42.8
Permanent Ineff=
       F       F
Bank Sta=4979.9,5036.2
XS Rating Curve= 0 ,0
Exp/Cntr=0.5,0.3

Type RM Length L Ch R = 3 ,73450.7 ,,,
BEGIN DESCRIPTION:
Footbridge
Structure ID: H00-69
END DESCRIPTION:
Bridge Culvert--1,0,-1,-1, 0
Deck Dist Width WeirC Skew NumUp NumDn MinLoCord MaxHiCord MaxSubmerge Is_Ogee
10,5,2.6,0, 60, 60, , , 0.95, 0, 1,1,,
  2416.6  2671.6  2701.6  2731.6  2736.6  2866.6  2886.6  2991.6  3051.6  3406.6
  3431.6  3631.6  3646.6  4396.6  4426.6  4441.6  4456.6  4471.6  4576.6  4591.6
  4666.6  4882.6 4977.97 4978.08  4980.9  5034.6    5038 5038.11  5050.8  5070.8
  5074.2  5085.3  5152.1  5262.4  5307.4  5477.4  5497.4  5512.4  5562.4  5807.4
  5827.4  5850.7  5905.7  6115.7  6320.7  6460.7  6490.7  6550.7  6920.7  6935.7
  7005.7  7185.7  7250.7  7275.7  7375.7  7405.7  7495.7  7655.7  7720.7  7831.6
   47.63   47.47   46.47   47.05   46.31   46.38   45.43      45    45.9   46.24
   46.94   45.87    44.9   43.19    41.7   42.32   48.78   50.65   49.48   45.85
   46.87   44.24   42.82   45.72   45.72   45.72   45.72   42.82   42.84   42.86
   42.86    42.9   43.69    43.8   42.02   41.86   42.49   40.89   42.52   41.51
   42.76   42.47   44.41   44.13   45.23   44.21   45.43   44.39   44.89   45.68
   45.84   44.93   45.79   44.91   45.64   45.07   45.85   45.62   46.46      50
   47.63   47.47   46.47   47.05   46.31   46.38   45.43      45    45.9   46.24
   46.94   45.87    44.9   43.19    41.7   42.32   48.78   50.65   49.48   45.85
   46.87   44.24   42.23   42.23   41.52   41.52    42.2   42.21   42.65   41.25
   40.13   42.89   43.69    43.8   42.02   41.86   42.49   40.89   42.52   41.51
   42.76   42.47   44.41   44.13   45.23   44.21   45.43   44.39   44.89   45.68
   45.84   44.93   45.79   44.91   45.64   45.07   45.85   45.62   46.46      50
  2416.6  2671.6  2701.6  2731.6  2736.6  2866.6  2886.6  2991.6  3051.6  3406.6
  3431.6  3631.6  3646.6  4396.6  4426.6  4441.6  4456.6  4471.6  4576.6  4591.6
  4666.6  4882.6 4977.97 4978.08  4980.9  5034.6    5038 5038.11  5050.8  5070.8
  5074.2  5085.3  5152.1  5262.4  5307.4  5477.4  5497.4  5512.4  5562.4  5807.4
  5827.4  5850.7  5905.7  6115.7  6320.7  6460.7  6490.7  6550.7  6920.7  6935.7
  7005.7  7185.7  7250.7  7275.7  7375.7  7405.7  7495.7  7655.7  7720.7  7831.6
   47.63   47.47   46.47   47.05   46.31   46.38   45.43      45    45.9   46.24
   46.94   45.87    44.9   43.19    41.7   42.32   48.78   50.65   49.48   45.85
   46.87   44.24   42.82   45.72   45.72   45.72   45.72   42.82   42.84   42.86
   42.86    42.9   43.69    43.8   42.02   41.86   42.49   40.89   42.52   41.51
   42.76   42.47   44.41   44.13   45.23   44.21   45.43   44.39   44.89   45.68
   45.84   44.93   45.79   44.91   45.64   45.07   45.85   45.62   46.46      50
   47.63   47.47   46.47   47.05   46.31   46.38   45.43      45    45.9   46.24
   46.94   45.87    44.9   43.19    41.7   42.32   48.78   50.65   49.48   45.85
   46.87   44.24   42.23   42.23   41.52   41.52    42.2   42.21   42.65   41.25
   40.13   42.89   43.69    43.8   42.02   41.86   42.49   40.89   42.52   41.51
   42.76   42.47   44.41   44.13   45.23   44.21   45.43   44.39   44.89   45.68
   45.84   44.93   45.79   44.91   45.64   45.07   45.85   45.62   46.46      50
Pier Skew, UpSta & Num, DnSta & Num=  ,4997.5, 2 ,4997.5, 2 , 0 , 0 , 0 ,,
       1       1
   32.56   42.52
       1       1
   32.56   42.52
Pier Skew, UpSta & Num, DnSta & Num=  ,5018.6, 2 ,5018.6, 2 , 0 , 0 , 0 ,,
       1       1
   34.53   42.52
       1       1
   34.53   42.52
BR Coef= 1 , 1 , 0 ,1.25, 0 ,,,0.8,0,2,0,
WSPro=,,,, 1 ,,,, 0 ,,,, 0 ,,,,-1 ,-1 ,-1 , 0 , 0 , 0 , 0 , 0
BR U #Sta/Elev= 116
  2416.6   47.63  2526.6   47.38  2566.6   47.05  2671.6   47.47  2701.6   46.47
  2731.6   47.05  2736.6   46.31  2776.6   46.13  2781.6   46.67  2866.6   46.38
  2886.6   45.43  2991.6      45  3006.6   45.25  3031.6   45.16  3051.6    45.9
  3406.6   46.24  3431.6   46.94  3631.6   45.87  3646.6    44.9  3944.3   44.22
  4396.6   43.19  4426.6    41.7  4441.6   42.32  4456.6   48.78  4471.6   50.65
  4576.6   49.48  4591.6   45.85  4666.6   46.87  4690.3   46.57  4738.5   45.77
  4741.3   45.88  4830.3   44.74  4882.6   44.24  4914.3   43.57 4977.97   42.23
 4978.08   42.23 4978.19   42.23 4978.31   42.22  4978.4   42.22  4978.5   42.22
  4979.9   42.19  4980.9   41.51  4990.2   35.38  4992.4   33.93  4993.5   32.32
  4997.5   33.74  5004.4   32.13  5005.6   32.87  5007.6   35.24  5018.6   35.54
  5021.1   36.27  5034.6   41.51  5036.2   42.14 5037.79    42.2    5038    42.2
 5038.11   42.21  5038.2   42.21 5038.29   42.21  5038.4   42.22  5038.5   42.22
  5050.8   42.65  5070.8   41.25  5074.2   40.13  5085.3   42.89  5086.3   42.88
  5104.1   42.71  5152.1   43.69  5202.9   43.76  5262.4    43.8  5307.4   42.02
  5357.4   42.33  5363.8   42.27  5387.4   42.06  5477.4   41.86  5492.4   42.49
  5497.4   42.49  5512.4   40.89  5527.4   41.92  5562.4   42.52  5763.3   42.05
  5792.4   41.98  5807.4   41.51  5827.4   42.76  5835.7   42.79  5850.7   42.47
  5870.7   43.37  5885.7   43.43  5905.7   44.41  5940.7   44.06  6020.7   44.27
  6115.7   44.13  6320.7   45.23  6385.7   44.72  6440.7   44.64  6460.7   44.21
  6490.7   45.43  6515.7   44.66  6535.7   44.97  6550.7   44.39  6920.7   44.89
  6935.7   45.68  6970.7    45.4  7005.7   45.84  7120.7      45  7145.7   45.57
  7185.7   44.93  7250.7   45.79  7275.7   44.91  7330.7    45.3  7375.7   45.64
  7395.7   45.46  7405.7   45.07  7495.7   45.85  7655.7   45.62  7720.7   46.46
  7831.6      50
BR U #Mann= 6
  2416.6      .2  3944.3      .1  4979.9    .035  5036.2      .1  5363.8      .2
  5763.3     .99
BR U Banks=4979.9,5036.2
BR D #Sta/Elev= 116
  2416.6   47.63  2526.6   47.38  2566.6   47.05  2671.6   47.47  2701.6   46.47
  2731.6   47.05  2736.6   46.31  2776.6   46.13  2781.6   46.67  2866.6   46.38
  2886.6   45.43  2991.6      45  3006.6   45.25  3031.6   45.16  3051.6    45.9
  3406.6   46.24  3431.6   46.94  3631.6   45.87  3646.6    44.9  3944.3   44.22
  4396.6   43.19  4426.6    41.7  4441.6   42.32  4456.6   48.78  4471.6   50.65
  4576.6   49.48  4591.6   45.85  4666.6   46.87  4690.3   46.57  4738.5   45.77
  4741.3   45.88  4830.3   44.74  4882.6   44.24  4914.3   43.57 4977.97   42.23
 4978.08   42.23 4978.19   42.23 4978.31   42.22  4978.4   42.22  4978.5   42.22
  4979.9   42.19  4980.9   41.51  4990.2   35.38  4992.4   33.93  4993.5   32.32
  4997.5   33.74  5004.4   32.13  5005.6   32.87  5007.6   35.24  5018.6   35.54
  5021.1   36.27  5034.6   41.51  5036.2   42.14 5037.79    42.2    5038    42.2
 5038.11   42.21  5038.2   42.21 5038.29   42.21  5038.4   42.22  5038.5   42.22
  5050.8   42.65  5070.8   41.25  5074.2   40.13  5085.3   42.89  5086.3   42.88
  5104.1   42.71  5152.1   43.69  5202.9   43.76  5262.4    43.8  5307.4   42.02
  5357.4   42.33  5363.8   42.27  5387.4   42.06  5477.4   41.86  5492.4   42.49
  5497.4   42.49  5512.4   40.89  5527.4   41.92  5562.4   42.52  5763.3   42.05
  5792.4   41.98  5807.4   41.51  5827.4   42.76  5835.7   42.79  5850.7   42.47
  5870.7   43.37  5885.7   43.43  5905.7   44.41  5940.7   44.06  6020.7   44.27
  6115.7   44.13  6320.7   45.23  6385.7   44.72  6440.7   44.64  6460.7   44.21
  6490.7   45.43  6515.7   44.66  6535.7   44.97  6550.7   44.39  6920.7   44.89
  6935.7   45.68  6970.7    45.4  7005.7   45.84  7120.7      45  7145.7   45.57
  7185.7   44.93  7250.7   45.79  7275.7   44.91  7330.7    45.3  7375.7   45.64
  7395.7   45.46  7405.7   45.07  7495.7   45.85  7655.7   45.62  7720.7   46.46
  7831.6      50
BR D #Mann= 6
  2416.6      .2  3944.3      .1  4979.9    .035  5036.2      .1  5363.8      .2
  5763.3     .99
BR D Banks=4979.9,5036.2
BC Design=,, 0 ,, 0 ,,,,,,
BC HTab HWMax=50.67
BC Use User HTab Curves=0
BC User HTab FreeFlow(D)= 0

Type RM Length L Ch R = 1 ,73438.2 ,382,382,382
BEGIN DESCRIPTION:
Downstream Section of Bridge/Culvert/Weir
END DESCRIPTION:
XS GIS Cut Line= 6
      3131333.54     13861854.49      3131468.76     13859592.09
       3131401.4     13859203.18      3131313.25     13858888.69
       3131186.5     13858466.06      3130000.02     13856873.41
#Sta/Elev= 30
  2416.6   47.58  2991.6   44.95  3431.6   46.89  3944.3   44.17  4396.6   43.14
  4426.6   41.65  4441.6   42.27  4456.6   48.73  4471.6    50.6  4576.6   49.43
  4591.6    45.8  4666.6   46.82  4979.9   42.14  4993.5   32.27  4997.5   33.69
  5004.4   32.08  5007.6   35.19  5018.6   35.49  5036.2   42.09  5074.2   40.08
  5085.3   42.84  5152.1   43.64  5363.8   42.22  5497.4   42.44  5512.4   40.84
  5763.3      42  5905.7   44.36  6320.7   45.18  7655.7   45.57  7831.6   49.95
#Mann= 6 , 1 , 0
  2416.6      .2       0  3944.3      .1       0  4979.9    .035       0
  5036.2      .1       0  5363.8      .2       0  5763.3     .99       0
#XS Ineff= 2 , 0
       0  4572.5   49.55    5046       0    42.8
Permanent Ineff=
       F       F
Bank Sta=4979.9,5036.2
XS Rating Curve= 0 ,0
Exp/Cntr=0.5,0.3

Type RM Length L Ch R = 1 ,73056.2 ,229.5,265.2,270.3
BEGIN DESCRIPTION:
Cross Section 73056.2
END DESCRIPTION:
XS GIS Cut Line= 6
      3131389.83      13861862.6      3131650.96     13859468.56
      3131678.94     13859073.47      3131682.51     13858916.21
      3131595.64     13858852.82      3129910.57     13856693.59
#Sta/Elev= 30
  2134.8   47.82  2709.8   45.39  3294.8   46.23  3384.8   44.54  3789.8   45.99
  4164.8   41.88  4209.8   50.92  4284.8   50.17  4304.8    48.2  4364.8   49.19
  4513.9    47.2  4558.1    42.5  4802.3   42.38 4940.81   42.91 4953.41   41.39
 4981.01   40.08 4984.31   34.55 4991.11    30.3 5008.41    30.4 5010.01   33.37
 5017.01   32.25 5057.11   34.31 5085.91    44.4    5229   42.95    5304   40.27
  5402.9   40.56  5802.3   43.75  6862.8   45.69  7792.8   44.64  7942.9   47.26
#Mann= 6 , 1 , 0
  2134.8      .2       0  4802.3      .1       0 4953.41    .035       0
 5085.91      .1       0  5402.9      .2       0  5802.3     .99       0
#XS Ineff= 2 , 0
       0  4364.5   49.18               0
Permanent Ineff=
       F       F
Bank Sta=4953.41,5085.91
XS Rating Curve= 0 ,0
Exp/Cntr=0.5,0.3

Type RM Length L Ch R = 1 ,72791.0 ,60,60,60
BEGIN DESCRIPTION:
Upstream Section of Bridge/Culvert/Weir
END DESCRIPTION:
XS GIS Cut Line= 6
      3131628.86     13861991.56      3131941.25      13858489.9
       3131987.6     13855899.03      3131547.87     13854008.55
      3130683.01     13852891.56       3129565.2     13850696.15
#Sta/Elev= 30
  1947.2   47.85  4107.2   42.67  4167.2   50.43  4356.3   50.41  4389.9    49.5
  4439.9   41.82  4829.3   41.75  4960.7   43.16  4984.3   31.69  4989.7   32.87
  4991.4   31.08  5009.2   30.28  5012.3   33.46  5033.3   42.69  5402.2   43.19
  5801.3   43.49  7081.2   45.67  7231.2   43.82  7486.2   46.03  8455.9   43.81
  8720.9    46.2  8815.9   44.56  9215.9   46.21  9540.9   43.72  9660.9    45.8
  9820.9   44.05  9964.6   45.77   11486   47.04 13848.8   44.01 13872.2      52
#Mann= 7 , 1 , 0
  1947.2     .99       0  4356.3      .2       0  4829.3      .1       0
  4960.7    .035       0  5033.3      .1       0  5402.2      .2       0
  5801.3     .99       0
#XS Ineff= 2 , 0
       0  4251.6   51.15   11039       0   46.26
Permanent Ineff=
       F       F
Bank Sta=4960.7,5033.3
XS Rating Curve= 0 ,0
Exp/Cntr=0.5,0.3

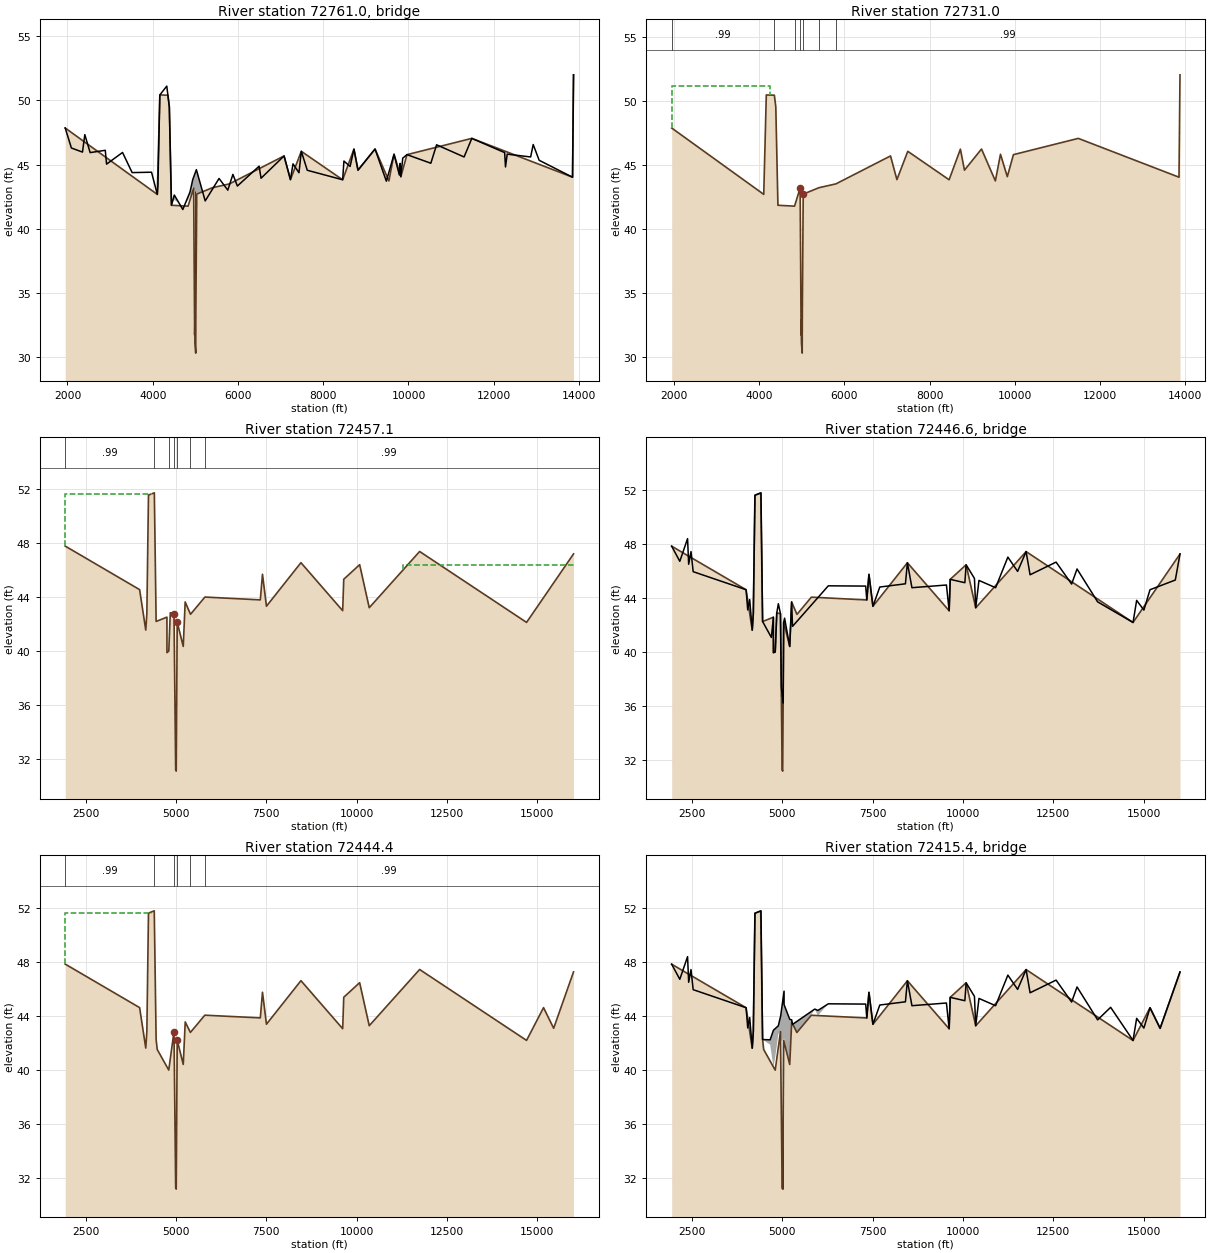
Type RM Length L Ch R = 3 ,72761.0 ,,,
BEGIN DESCRIPTION:
FALLS ROAD
Structure ID: H00-67
END DESCRIPTION:
Bridge Culvert--1,0,-1,-1, 0
Deck Dist Width WeirC Skew NumUp NumDn MinLoCord MaxHiCord MaxSubmerge Is_Ogee
10,40,2.6,0, 60, 60, , , 0.95, 0, 1,1,,
  1947.2  2092.2  2352.2  2407.2  2532.2  2887.2  2917.2  3292.2  3517.2  3972.2
  4107.2  4122.2  4167.2  4329.9  4389.9  4439.9  4506.3  4706.2  4873.6  4909.6
  4938.5 5024.39  5231.3  5556.4  5761.4  5881.2  5986.2  6496.2  6541.2  7081.2
  7231.2  7291.2  7431.2  7486.2  7626.2  8455.9  8485.9  8630.9  8720.9  8815.9
  9215.9  9480.9  9660.9  9785.9  9805.9  9820.9  9865.9  9964.6 10524.6 10659.6
 11304.6   11486   12256   12276   12316   12866   12926   13066 13848.8 13872.2
   47.85   46.29   45.97   47.33   45.93   46.11   45.03   45.94   44.37    44.4
   42.67   43.37   50.43   51.12    49.5   41.82   42.62   41.49   42.85   43.37
   43.82    44.6   42.16   43.91      43   44.23   43.32   44.87   43.93   45.67
   43.82   45.05   44.36   46.03   44.55   43.81   45.27   44.85    46.2   44.56
   46.21    43.7    45.8   44.18   45.09   44.05    45.5   45.77    45.1   46.54
   45.59   47.04   45.93   44.81   45.81   45.59   46.56   45.33   44.01      52
   47.85   46.29   45.97   47.33   45.93   46.11   45.03   45.94   44.37    44.4
   42.67   43.37   50.43   51.12    49.5   41.82   42.24   41.13   42.59   41.53
   43.26    42.7   41.91   43.91      43   44.23   43.32   44.87   43.93   45.67
   43.82   45.05   44.36   46.03   44.55   43.81   45.27   44.85    46.2   44.56
   46.21    43.7    45.8   44.18   45.09   44.05    45.5   45.77    45.1   46.54
   45.59   47.04   45.93   44.81   45.81   45.59   46.56   45.33   44.01      52
  1947.2  2092.2  2352.2  2407.2  2532.2  2887.2  2917.2  3292.2  3517.2  3972.2
  4107.2  4122.2  4167.2  4329.9  4389.9  4439.9  4506.3  4706.2  4873.6  4909.6
  4938.5 5024.39  5231.3  5556.4  5761.4  5881.2  5986.2  6496.2  6541.2  7081.2
  7231.2  7291.2  7431.2  7486.2  7626.2  8455.9  8485.9  8630.9  8720.9  8815.9
  9215.9  9480.9  9660.9  9785.9  9805.9  9820.9  9865.9  9964.6 10524.6 10659.6
 11304.6   11486   12256   12276   12316   12866   12926   13066 13848.8 13872.2
   47.85   46.29   45.97   47.33   45.93   46.11   45.03   45.94   44.37    44.4
   42.67   43.37   50.43   51.12    49.5   41.82   42.62   41.49   42.85   43.37
   43.82    44.6   42.16   43.91      43   44.23   43.32   44.87   43.93   45.67
   43.82   45.05   44.36   46.03   44.55   43.81   45.27   44.85    46.2   44.56
   46.21    43.7    45.8   44.18   45.09   44.05    45.5   45.77    45.1   46.54
   45.59   47.04   45.93   44.81   45.81   45.59   46.56   45.33   44.01      52
   47.85   46.29   45.97   47.33   45.93   46.11   45.03   45.94   44.37    44.4
   42.67   43.37   50.43   51.12    49.5   41.82   42.24   41.13   42.59   41.53
   43.26    42.7   41.91   43.91      43   44.23   43.32   44.87   43.93   45.67
   43.82   45.05   44.36   46.03   44.55   43.81   45.27   44.85    46.2   44.56
   46.21    43.7    45.8   44.18   45.09   44.05    45.5   45.77    45.1   46.54
   45.59   47.04   45.93   44.81   45.81   45.59   46.56   45.33   44.01      52
Pier Skew, UpSta & Num, DnSta & Num=  ,4984.3, 2 ,4984.3, 2 , 0 , 0 , 0 ,,
     1.4     1.4
   31.03   43.42
     1.4     1.4
   31.03   43.42
BR Coef= 1 , 1 , 0 ,1.25, 0 ,,,0.8,0,2,0,
WSPro=,,,, 1 ,,,, 0 ,,,, 0 ,,,,-1 ,-1 ,-1 , 0 , 0 , 0 , 0 , 0
BR U #Sta/Elev= 30
  1947.2   47.85  4107.2   42.67  4167.2   50.43  4356.3   50.41  4389.9    49.5
  4439.9   41.82  4829.3   41.75  4960.7   43.16  4984.3   31.69  4989.7   32.87
  4991.4   31.08  5009.2   30.28  5012.3   33.46  5033.3   42.69  5402.2   43.19
  5801.3   43.49  7081.2   45.67  7231.2   43.82  7486.2   46.03  8455.9   43.81
  8720.9    46.2  8815.9   44.56  9215.9   46.21  9540.9   43.72  9660.9    45.8
  9820.9   44.05  9964.6   45.77   11486   47.04 13848.8   44.01 13872.2      52
BR U #Mann= 7
  1947.2     .99  4356.3      .2  4829.3      .1  4960.7    .035  5033.3      .1
  5402.2      .2  5801.3     .99
BR U Banks=4960.7,5033.3
BR D #Sta/Elev= 30
  1947.2   47.85  4107.2   42.67  4167.2   50.43  4356.3   50.41  4389.9    49.5
  4439.9   41.82  4829.3   41.75  4960.7   43.16  4984.3   31.69  4989.7   32.87
  4991.4   31.08  5009.2   30.28  5012.3   33.46  5033.3   42.69  5402.2   43.19
  5801.3   43.49  7081.2   45.67  7231.2   43.82  7486.2   46.03  8455.9   43.81
  8720.9    46.2  8815.9   44.56  9215.9   46.21  9540.9   43.72  9660.9    45.8
  9820.9   44.05  9964.6   45.77   11486   47.04 13848.8   44.01 13872.2      52
BR D #Mann= 7
  1947.2     .99  4356.3      .2  4829.3      .1  4960.7    .035  5033.3      .1
  5402.2      .2  5801.3     .99
BR D Banks=4960.7,5033.3
BC Design=,, 0 ,, 0 ,,,,,,
BC HTab HWMax=52
BC Use User HTab Curves=0
BC User HTab FreeFlow(D)= 0

Type RM Length L Ch R = 1 ,72731.0 ,273.9,273.9,273.9
BEGIN DESCRIPTION:
Downstream Section of Bridge/Culvert/Weir
END DESCRIPTION:
XS GIS Cut Line= 6
      3131685.41      13862011.6      3131997.81     13858509.94
      3132044.16     13855919.07      3131604.43     13854028.59
      3130739.57      13852911.6      3129621.75     13850716.19
#Sta/Elev= 30
  1947.2   47.88  4107.2    42.7  4167.2   50.46  4356.3   50.44  4389.9   49.53
  4439.9   41.85  4829.3   41.78  4960.7   43.19  4984.3   31.72  4989.7    32.9
  4991.4   31.11  5009.2   30.31  5012.3   33.49  5033.3   42.72  5402.2   43.22
  5801.3   43.52  7081.2    45.7  7231.2   43.85  7486.2   46.06  8455.9   43.84
  8720.9   46.23  8815.9   44.59  9215.9   46.24  9540.9   43.75  9660.9   45.83
  9820.9   44.08  9964.6    45.8   11486   47.07 13848.8   44.04 13872.2   52.03
#Mann= 7 , 1 , 0
  1947.2     .99       0  4356.3      .2       0  4829.3      .1       0
  4960.7    .035       0  5033.3      .1       0  5402.2      .2       0
  5801.3     .99       0
#XS Ineff= 2 , 0
       0  4251.6   51.15   11039       0   46.26
Permanent Ineff=
       F       F
Bank Sta=4960.7,5033.3
XS Rating Curve= 0 ,0
Exp/Cntr=0.5,0.3

Type RM Length L Ch R = 1 ,72457.1 ,12.7,12.7,12.7
BEGIN DESCRIPTION:
Upstream Section of Bridge/Culvert/Weir
END DESCRIPTION:
XS GIS Cut Line= 6
      3131700.05     13862065.81      3132191.54     13859730.19
       3132280.7     13858070.64      3131811.91     13853868.72
      3130900.34     13852684.27      3129720.05     13848564.64
#Sta/Elev= 30
  1934.7    47.8  3994.7   44.57  4164.7   41.57  4194.7    42.8  4239.7   51.58
  4401.8   51.75  4451.5   42.21  4750.1   42.53  4751.3    39.9  4801.8   40.01
  4843.9   42.85    4946   42.79  4992.7    31.2  5007.7   31.11    5035   42.15
  5202.4   40.36  5255.2   43.66  5402.7   42.74  5801.8   44.02  7335.3   43.81
  7395.3   45.71  7505.3   43.34    8460   46.57    9615   43.01    9645   45.34
   10085   46.42 10350.6   43.23 11745.2    47.4 14705.2   42.14 16005.2   47.22
#Mann= 7 , 1 , 0
  1934.7     .99       0  4401.8      .2       0  4801.8      .1       0
    4946    .035       0    5035      .1       0  5402.7      .2       0
  5801.8     .99       0
#XS Ineff= 2 , 0
       0    4328    51.7   11274       0    46.4
Permanent Ineff=
       F       F
Bank Sta=4946,5035
XS Rating Curve= 0 ,0
Exp/Cntr=0.5,0.3

Type RM Length L Ch R = 3 ,72446.6 ,,,
BEGIN DESCRIPTION:
Pipeline
END DESCRIPTION:
Bridge Culvert--1,0,-1,-1, 0
Deck Dist Width WeirC Skew NumUp NumDn MinLoCord MaxHiCord MaxSubmerge Is_Ogee
10,1,2.6,0, 60, 60, , , 0.95, 0, 1,1,,
  1934.7  2159.7  2374.7  2404.7  2469.7  2529.7  3994.7  4039.7  4094.7  4164.7
  4194.7  4239.7  4406.5  4451.5  4694.7  4750.1  4751.3  4800.8  4843.9  4887.6
    4946 4970.81  5019.9    5035  5060.1  5202.4  5255.2  5279.5  6270.3  7305.3
  7335.3  7395.3  7505.3  7695.3    8405    8460    8585    9540    9615    9645
   10050   10085 10315.6 10350.6 10440.6 10900.6 11240.6 11510.6 11745.2 11855.2
 12575.2 13005.2 13155.2 13725.2 14705.2 14805.2 15005.2 15175.2 15875.2 16005.2
   47.83   46.71   48.39   46.49   47.43   45.94    44.6    43.1   43.87    41.6
   42.83   51.61   51.79   42.24   41.06   42.56   39.93   39.97   42.88   43.56
   42.82   37.33   36.19   42.18   42.49   40.39   43.69   41.88   44.89   44.87
   43.84   45.74   43.37    44.8   45.04    46.6   44.75   44.95   43.04   45.37
   45.12   46.45   45.44   43.26   45.29   44.75   47.02   45.96   47.43   45.71
   46.65   45.02   46.14    43.7   42.17   43.81   43.09    44.6   45.32   47.25
   47.83   46.71   48.39   46.49   47.43   45.94    44.6    43.1   43.87    41.6
   42.83   51.61   51.79   42.24   41.06   42.56   39.93   39.97   42.88   43.56
   42.82   35.91   36.19   42.18   42.49   40.39   43.69   41.88   44.89   44.87
   43.84   45.74   43.37    44.8   45.04    46.6   44.75   44.95   43.04   45.37
   45.12   46.45   45.44   43.26   45.29   44.75   47.02   45.96   47.43   45.71
   46.65   45.02   46.14    43.7   42.17   43.81   43.09    44.6   45.32   47.25
  1934.7  2159.7  2374.7  2404.7  2469.7  2529.7  3994.7  4039.7  4094.7  4164.7
  4194.7  4239.7  4406.5  4451.5  4694.7  4750.1  4751.3  4800.8  4843.9  4887.6
    4946 4970.81  5019.9    5035  5060.1  5202.4  5255.2  5279.5  6270.3  7305.3
  7335.3  7395.3  7505.3  7695.3    8405    8460    8585    9540    9615    9645
   10050   10085 10315.6 10350.6 10440.6 10900.6 11240.6 11510.6 11745.2 11855.2
 12575.2 13005.2 13155.2 13725.2 14705.2 14805.2 15005.2 15175.2 15875.2 16005.2
   47.83   46.71   48.39   46.49   47.43   45.94    44.6    43.1   43.87    41.6
   42.83   51.61   51.79   42.24   41.06   42.56   39.93   39.97   42.88   43.56
   42.82   37.33   36.19   42.18   42.49   40.39   43.69   41.88   44.89   44.87
   43.84   45.74   43.37    44.8   45.04    46.6   44.75   44.95   43.04   45.37
   45.12   46.45   45.44   43.26   45.29   44.75   47.02   45.96   47.43   45.71
   46.65   45.02   46.14    43.7   42.17   43.81   43.09    44.6   45.32   47.25
   47.83   46.71   48.39   46.49   47.43   45.94    44.6    43.1   43.87    41.6
   42.83   51.61   51.79   42.24   41.06   42.56   39.93   39.97   42.88   43.56
   42.82   35.91   36.19   42.18   42.49   40.39   43.69   41.88   44.89   44.87
   43.84   45.74   43.37    44.8   45.04    46.6   44.75   44.95   43.04   45.37
   45.12   46.45   45.44   43.26   45.29   44.75   47.02   45.96   47.43   45.71
   46.65   45.02   46.14    43.7   42.17   43.81   43.09    44.6   45.32   47.25
BR Coef= 1 , 1 , 0 ,1.25, 0 ,,,0.8,0,2,0,
WSPro=,,,, 1 ,,,, 0 ,,,, 0 ,,,,-1 ,-1 ,-1 , 0 , 0 , 0 , 0 , 0
BR U #Sta/Elev= 30
  1934.7   47.83  3994.7    44.6  4164.7    41.6  4194.7   42.83  4239.7   51.61
  4401.8   51.78  4451.5   42.24  4750.1   42.56  4751.3   39.93  4801.8   40.04
  4843.9   42.88    4946   42.82  4992.7   31.23  5007.7   31.14    5035   42.18
  5202.4   40.39  5255.2   43.69  5402.7   42.77  5801.8   44.05  7335.3   43.84
  7395.3   45.74  7505.3   43.37    8460    46.6    9615   43.04    9645   45.37
   10085   46.45 10350.6   43.26 11745.2   47.43 14705.2   42.17 16005.2   47.25
BR U #Mann= 7
  1934.7     .99  4401.8      .2  4801.8      .1    4946    .035    5035      .1
  5402.7      .2  5801.8     .99
BR U Banks=4946,5035
BR D #Sta/Elev= 30
  1934.7   47.83  3994.7    44.6  4164.7    41.6  4194.7   42.83  4239.7   51.61
  4401.8   51.78  4451.5   42.24  4750.1   42.56  4751.3   39.93  4801.8   40.04
  4843.9   42.88    4946   42.82  4992.7   31.23  5007.7   31.14    5035   42.18
  5202.4   40.39  5255.2   43.69  5402.7   42.77  5801.8   44.05  7335.3   43.84
  7395.3   45.74  7505.3   43.37    8460    46.6    9615   43.04    9645   45.37
   10085   46.45 10350.6   43.26 11745.2   47.43 14705.2   42.17 16005.2   47.25
BR D #Mann= 7
  1934.7     .99  4401.8      .2  4801.8      .1    4946    .035    5035      .1
  5402.7      .2  5801.8     .99
BR D Banks=4946,5035
BC Design=,, 0 ,, 0 ,,,,,,
BC HTab HWMax=51.76
BC Use User HTab Curves=0
BC User HTab FreeFlow(D)= 0

Type RM Length L Ch R = 1 ,72444.4 ,58,58,58
BEGIN DESCRIPTION:
Upstream Section of Bridge/Culvert/Weir
END DESCRIPTION:
XS GIS Cut Line= 6
      3131717.85     13862071.78      3132195.79     13859734.06
      3132302.34     13858085.89      3131834.17     13853860.05
      3130910.68      13852658.2      3129805.19     13848554.88
#Sta/Elev= 30
  1934.7   47.83  3994.7    44.6  4164.7    41.6  4194.7   42.83  4239.7   51.61
  4399.5   51.78  4451.5   42.24  4481.5    41.5  4800.8   39.97    4946   42.82
  4992.7   31.23  5007.7   31.14    5035   42.18  5202.4   40.39  5256.9   43.54
    5400   42.76  5799.5   44.04  7335.3   43.84  7395.3   45.74  7505.3   43.37
    8460    46.6    9615   43.04    9645   45.37   10085   46.45 10350.6   43.26
 11745.2   47.43 14705.2   42.17 15175.2    44.6 15455.2   43.07 16005.2   47.25
#Mann= 6 , 1 , 0
  1934.7     .99       0  4399.5      .1       0    4946    .035       0
    5035      .1       0    5400      .2       0  5799.5     .99       0
#XS Ineff= 2 , 0
       0    4328    51.6   11506       0      46
Permanent Ineff=
       F       F
Bank Sta=4946,5035
XS Rating Curve= 0 ,0
Exp/Cntr=0.5,0.3

Type RM Length L Ch R = 3 ,72415.4 ,,,
BEGIN DESCRIPTION:
LEFFINGWELL STREET
Structure ID: H00-66
END DESCRIPTION:
Bridge Culvert--1,0,-1,-1, 0
Deck Dist Width WeirC Skew NumUp NumDn MinLoCord MaxHiCord MaxSubmerge Is_Ogee
10,38,2.6,0, 60, 60, , , 0.95, 0, 1,1,,
  1934.7  2159.7  2374.7  2404.7  2469.7  2529.7  3994.7  4039.7  4094.7  4164.7
  4194.7  4239.7  4406.5  4451.5  4659.7  4751.3  4886.7    4946 4952.91    4953
 5045.69 5045.91  5202.4  5256.9  5279.5  5895.3  5983.4  6270.3  7305.3  7335.3
  7395.3  7505.3  7695.3    8405    8460    8585    9540    9615    9645   10050
   10085 10315.6 10350.6 10440.6 10900.6 11240.6 11510.6 11745.2 11855.2 12575.2
 13005.2 13155.2 13725.2 14085.2 14705.2 14805.2 15005.2 15175.2 15455.2 16005.2
   47.83   46.71   48.39   46.49   47.43   45.94    44.6    43.1   43.87    41.6
   42.83   51.61   51.79   42.24   42.22   42.93   43.26   43.93   44.01   44.01
   45.83   44.83   43.74    43.7   43.36    44.5    44.4   44.89   44.87   43.84
   45.74   43.37    44.8   45.04    46.6   44.75   44.95   43.04   45.37   45.12
   46.45   45.44   43.26   45.29   44.75   47.02   45.96   47.43   45.71   46.65
   45.02   46.14    43.7   44.63   42.17   43.81   43.09    44.6   43.07   47.25
   47.83   46.71   48.39   46.49   47.43   45.94    44.6    43.1   43.87    41.6
   42.83   51.61   51.79   42.24   41.86   39.93   42.63   42.82    40.9   42.11
   42.31   42.31   40.39   43.54   41.88   44.49   43.43   44.89   44.87   43.84
   45.74   43.37    44.8   45.04    46.6   44.75   44.95   43.04   45.37   45.12
   46.45   45.44   43.26   45.29   44.75   47.02   45.96   47.43   45.71   46.65
   45.02   46.14    43.7   44.63   42.17   43.81   43.09    44.6   43.07   47.25
  1934.7  2159.7  2374.7  2404.7  2469.7  2529.7  3994.7  4039.7  4094.7  4164.7
  4194.7  4239.7  4406.5  4451.5  4659.7  4751.3  4886.7    4946 4952.91    4953
 5045.69 5045.91  5202.4  5256.9  5279.5  5895.3  5983.4  6270.3  7305.3  7335.3
  7395.3  7505.3  7695.3    8405    8460    8585    9540    9615    9645   10050
   10085 10315.6 10350.6 10440.6 10900.6 11240.6 11510.6 11745.2 11855.2 12575.2
 13005.2 13155.2 13725.2 14085.2 14705.2 14805.2 15005.2 15175.2 15455.2 16005.2
   47.83   46.71   48.39   46.49   47.43   45.94    44.6    43.1   43.87    41.6
   42.83   51.61   51.79   42.24   42.22   42.93   43.26   43.93   44.01   44.01
   45.83   44.83   43.74    43.7   43.36    44.5    44.4   44.89   44.87   43.84
   45.74   43.37    44.8   45.04    46.6   44.75   44.95   43.04   45.37   45.12
   46.45   45.44   43.26   45.29   44.75   47.02   45.96   47.43   45.71   46.65
   45.02   46.14    43.7   44.63   42.17   43.81   43.09    44.6   43.07   47.25
   47.73   46.61   48.29   46.39   47.33   45.84    44.5      43   43.77    41.5
   42.73   51.51   51.69   42.14   41.76   39.83   42.53   42.72    40.8   42.01
   42.21   42.21   40.29   43.44   41.78   44.39   43.33   44.79   44.77   43.74
   45.64   43.27    44.7   44.94    46.5   44.65   44.85   42.94   45.27   45.02
   46.35   45.34   43.16   45.19   44.65   46.92   45.86   47.33   45.61   46.55
   44.92   46.04    43.6   44.53   42.07   43.71   42.99    44.5   42.97   47.15
Pier Skew, UpSta & Num, DnSta & Num=  ,5006.5, 2 ,5006.5, 2 , 0 , 0 , 0 ,,
     1.4     1.4
   30.46   43.81
     1.4     1.4
   30.36   43.71
BR Coef= 1 , 1 , 0 ,1.25, 0 ,,,0.8,0,2,0,
WSPro=,,,, 1 ,,,, 0 ,,,, 0 ,,,,-1 ,-1 ,-1 , 0 , 0 , 0 , 0 , 0
BR U #Sta/Elev= 30
  1934.7   47.83  3994.7    44.6  4164.7    41.6  4194.7   42.83  4239.7   51.61
  4399.5   51.78  4451.5   42.24  4481.5    41.5  4800.8   39.97    4946   42.82
  4992.7   31.23  5007.7   31.14    5035   42.18  5202.4   40.39  5256.9   43.54
    5400   42.76  5799.5   44.04  7335.3   43.84  7395.3   45.74  7505.3   43.37
    8460    46.6    9615   43.04    9645   45.37   10085   46.45 10350.6   43.26
 11745.2   47.43 14705.2   42.17 15175.2    44.6 15455.2   43.07 16005.2   47.25
BR U #Mann= 6
  1934.7     .99  4399.5      .1    4946    .035    5035      .1    5400      .2
  5799.5     .99
BR U Banks=4946,5035
BR D #Sta/Elev= 30
  1934.7   47.73  3994.7    44.5  4164.7    41.5  4194.7   42.73  4239.7   51.51
  4399.5   51.68  4451.5   42.14  4481.5    41.4  4800.8   39.87    4946   42.72
  4992.7   31.13  5007.7   31.04    5035   42.08  5202.4   40.29  5256.9   43.44
    5400   42.66  5799.5   43.94  7335.3   43.74  7395.3   45.64  7505.3   43.27
    8460    46.5    9615   42.94    9645   45.27   10085   46.35 10350.6   43.16
 11745.2   47.33 14705.2   42.07 15175.2    44.5 15455.2   42.97 16005.2   47.15
BR D #Mann= 6
  1934.7     .99  4399.5      .1    4946    .035    5035      .1    5400      .2
  5799.5     .99
BR D Banks=4946,5035
BC Design=,, 0 ,, 0 ,,,,,,
BC HTab HWMax=51.79
BC Use User HTab Curves=0
BC User HTab FreeFlow(D)= 0