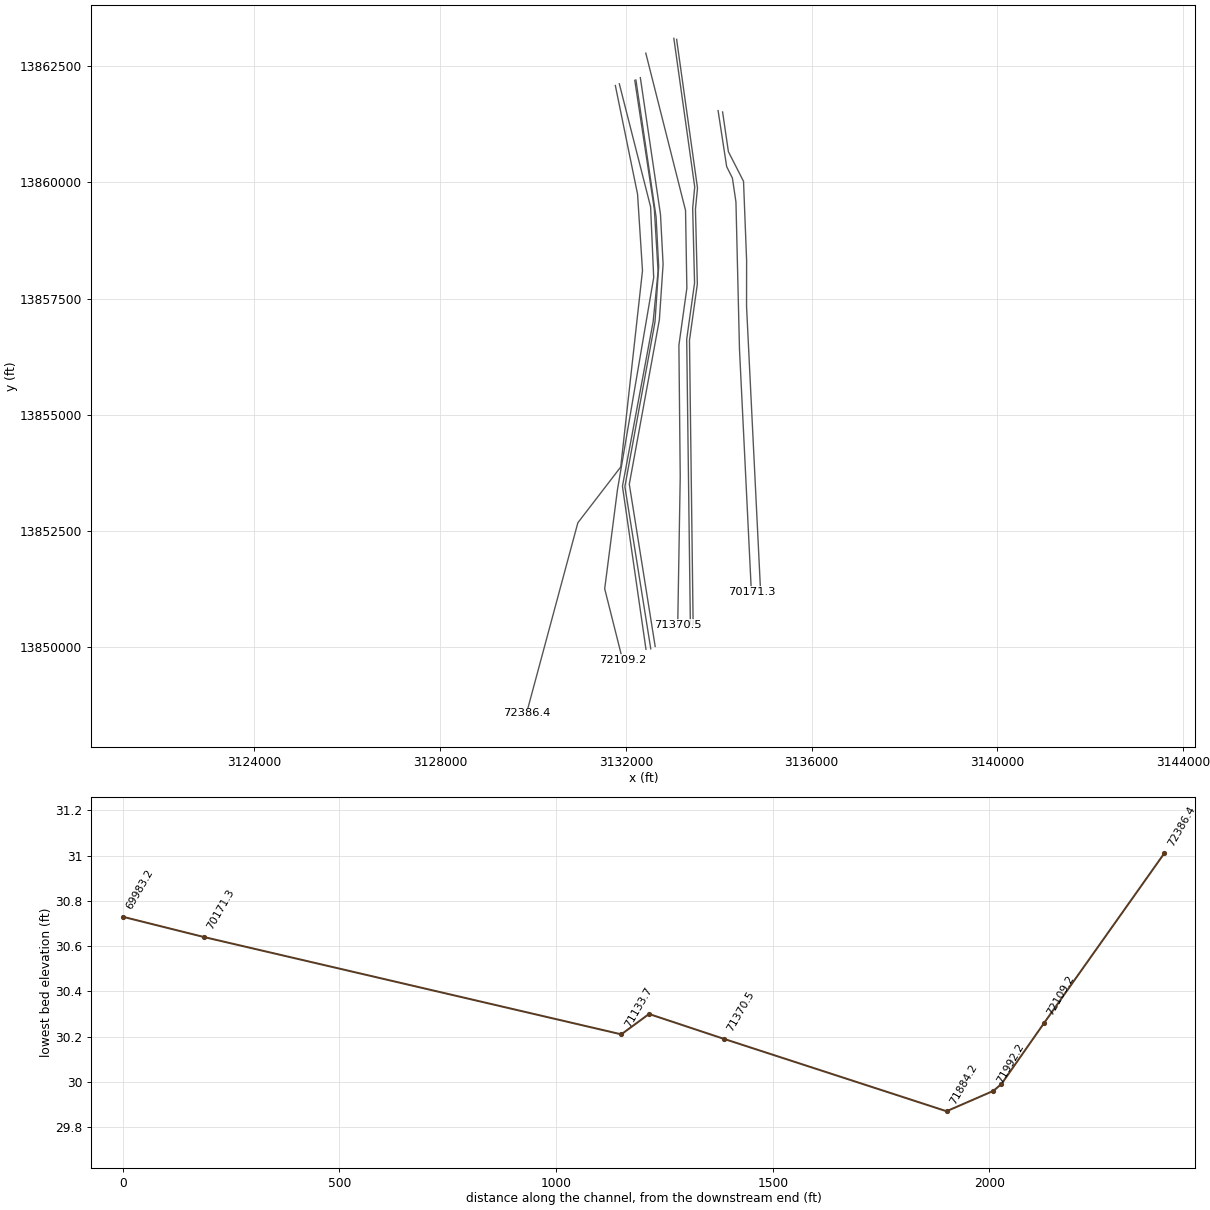
HEC-RAS study H100-00-00.prj: H100-00-00

--- H100-00-00.g01 (geometry) --- (continued)

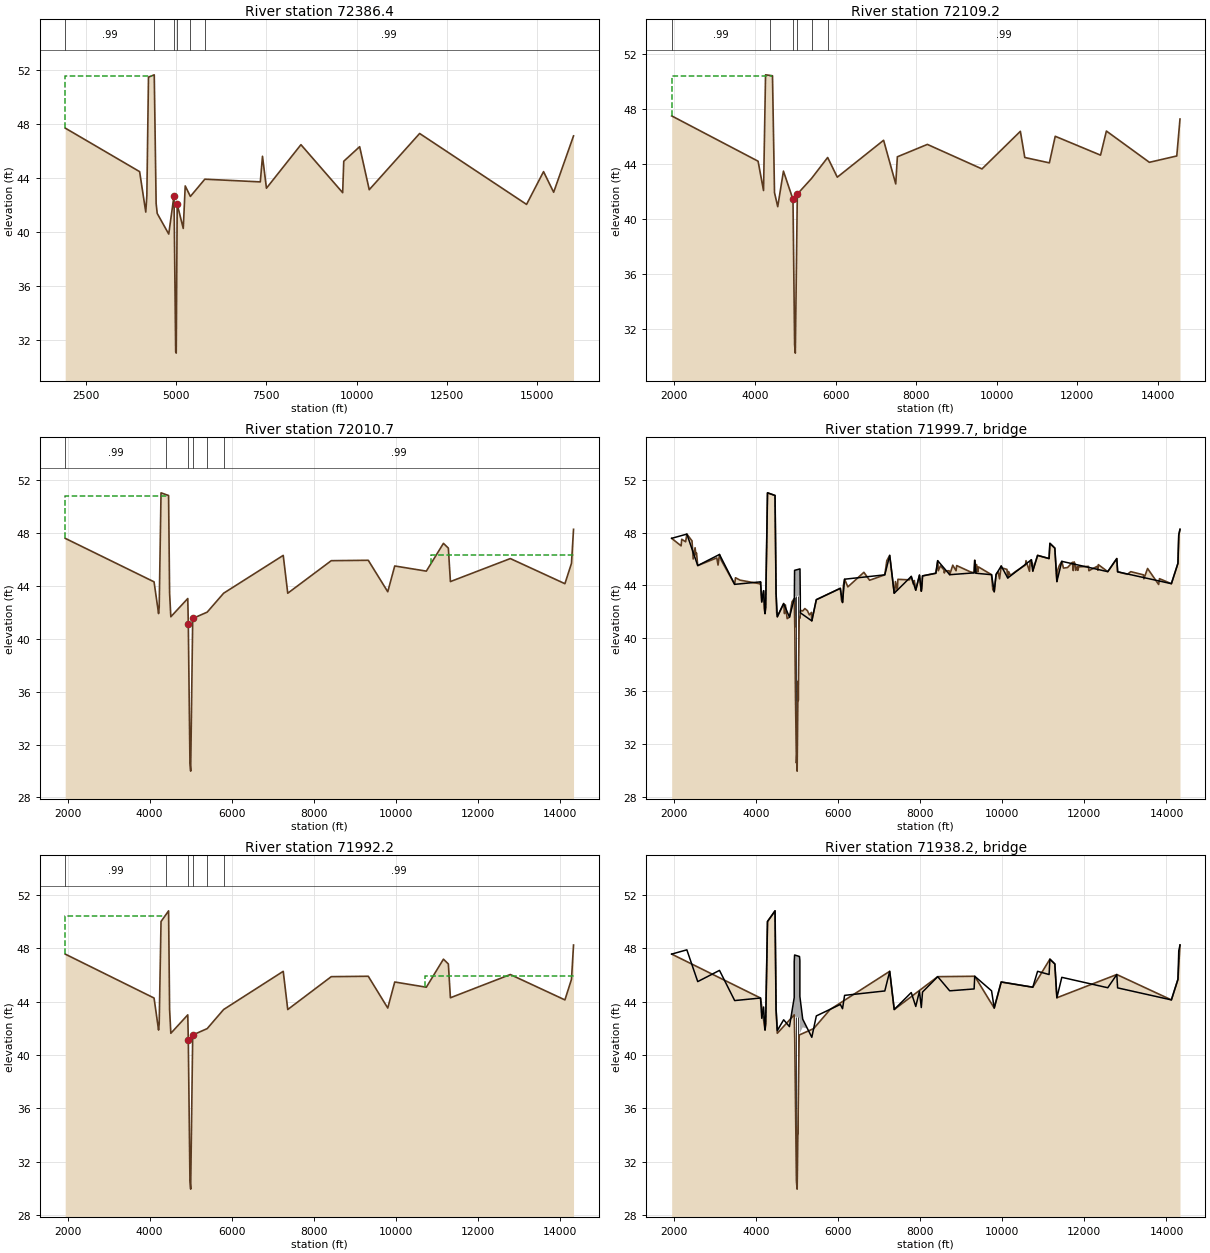
Type RM Length L Ch R = 1 ,72386.4 ,277.2,277.2,277.2
BEGIN DESCRIPTION:
Downstream Section of Bridge/Culvert/Weir
END DESCRIPTION:
XS GIS Cut Line= 6
      3131773.65     13862087.62      3132251.59      13859749.9
      3132358.14     13858101.73      3131889.97     13853875.89
      3130966.48     13852674.04      3129860.98     13848570.72
#Sta/Elev= 30
  1934.7    47.7  3994.7   44.47  4164.7   41.47  4194.7    42.7  4239.7   51.48
  4399.5   51.65  4451.5   42.11  4481.5   41.37  4800.8   39.84    4946   42.69
  4992.7    31.1  5007.7   31.01    5035   42.05  5202.4   40.26  5256.9   43.41
    5400   42.63  5799.5   43.91  7335.3   43.71  7395.3   45.61  7505.3   43.24
    8460   46.47    9615   42.91    9645   45.24   10085   46.32 10350.6   43.13
 11745.2    47.3 14705.2   42.04 15175.2   44.47 15455.2   42.94 16005.2   47.12
#Mann= 6 , 1 , 0
  1934.7     .99       0  4399.5      .1       0    4946    .035       0
    5035      .1       0    5400      .2       0  5799.5     .99       0
#XS Ineff= 2 , 0
       0    4328    51.6   11506       0      46
Permanent Ineff=
       F       F
Bank Sta=4946,5035
XS Rating Curve= 0 ,0
Exp/Cntr=0.5,0.3

Type RM Length L Ch R = 1 ,72109.2 ,97.6,98.5,132.5
BEGIN DESCRIPTION:
Cross Section 72109.2
END DESCRIPTION:
XS GIS Cut Line= 6
       3131859.4     13862123.88      3132532.62     13859475.76
      3132599.27     13857952.44      3131818.57     13853382.48
      3131544.41     13851253.21      3131927.91     13849729.89
#Sta/Elev= 30
  1931.8   47.48  4076.8   44.19  4211.8   42.06  4261.8   50.46  4369.6   50.42
  4434.1   50.39  4484.1   41.91  4564.1   40.89  4706.1   43.47 4942.97   41.42
 4983.27   30.87 5000.77   30.26 5050.27    41.8  5403.6   42.94  5803.6   44.46
  6042.4   43.03  7191.8   45.71  7493.3   42.54  7533.3   44.51  8278.3   45.41
  9633.6   43.63 10586.3   46.36 10696.3   44.46 11306.6   44.07 11451.6      46
 12576.6   44.63 12721.6   46.38 13788.4   44.11 14468.4   44.57 14548.4   47.25
#Mann= 6 , 1 , 0
  1931.8     .99       0  4369.6      .1       0 4942.97    .035       0
 5050.27      .1       0  5403.6      .2       0  5803.6     .99       0
#XS Ineff= 2 , 0
       0    4420    50.4   10550       0    45.7
Permanent Ineff=
       F       F
Bank Sta=4942.97,5050.27
XS Rating Curve= 0 ,0
Exp/Cntr=0.5,0.3

Type RM Length L Ch R = 1 ,72010.7 ,18.5,18.5,18.5
BEGIN DESCRIPTION:
Upstream Section of Bridge/Culvert/Weir
END DESCRIPTION:
XS GIS Cut Line= 6
      3132192.22     13862199.15      3132613.47     13859422.11
       3132693.8     13858085.59      3132587.35     13857002.69
      3131926.72     13853460.94      3132432.77     13849951.08
#Sta/Elev= 30
  1943.6   47.59  4108.6    44.3  4218.6    41.9  4233.6   42.38  4278.6   51.03
  4403.6   50.89  4462.4   50.83  4487.4   43.44  4517.4   41.66 4930.27   43.04
 4942.97   41.15 4983.27    30.6 5000.77   29.99 5050.27   41.53  5403.6   42.01
  5803.6   43.44  7256.2    46.3  7366.2   43.44  8426.2    45.9  9328.1   45.93
  9803.1   43.55  9973.1    45.5 10743.1   45.11 11159.7   47.21 11279.7   46.85
 11329.7   44.32 12789.7   46.06 14119.7   44.16 14279.7    45.7 14329.7   48.27
#Mann= 6 , 1 , 0
  1943.6     .99       0  4403.6      .1       0 4942.97    .035       0
 5050.27      .1       0  5403.6      .2       0  5803.6     .99       0
#XS Ineff= 2 , 0
       0    4458    50.8   10848       0   46.36
Permanent Ineff=
       F       F
Bank Sta=4942.97,5050.27
XS Rating Curve= 0 ,0
Exp/Cntr=0.5,0.3

Type RM Length L Ch R = 3 ,71999.7 ,,,
BEGIN DESCRIPTION:
Pipeline
END DESCRIPTION:
Bridge Culvert--1,0,-1,-1, 0
Deck Dist Width WeirC Skew NumUp NumDn MinLoCord MaxHiCord MaxSubmerge Is_Ogee
10,2,2.6,0, 60, 60, , , 0.95, 0, 1,1,,
  1943.6  2313.6  2578.6  3108.6  3478.6  4108.6  4138.6  4183.6  4218.6  4233.6
  4278.6  4462.4  4487.4  4517.4  4672.4 4814.37 4932.57 4938.07 5070.47 5077.67
 5077.77  5358.1  5468.1  6053.1  6106.9  6156.9  7136.9  7256.2  7366.2  7781.2
  7891.2  7981.2  8026.2  8056.2  8381.2  8426.2  8718.1  9313.1  9328.1  9358.1
  9738.1  9803.1  9848.1  9973.1 10133.1 10708.1 10743.1 10859.7 11139.7 11159.7
 11279.7 11329.7 11449.7 12569.7 12789.7 12809.7 14119.7 14279.7 14299.7 14329.7
   47.56   47.88    45.5   46.34   44.08   44.27   42.75    43.6   41.87   42.35
      51    50.8   43.41   41.63   42.63    41.6   43.03   45.14   45.25   43.17
   41.93   41.32   42.92   43.78   42.71   44.47    44.8   46.27   43.41   44.68
   43.64   44.78   43.56   44.72   44.92   45.87   44.81   44.95    45.9   44.92
   44.81   43.52   44.83   45.47   44.56   45.94   45.08   46.27   46.03   47.18
   46.82   44.29   45.82   45.04   46.03   45.03   44.13   45.67   47.81   48.24
   47.56   47.88    45.5   46.34   44.08   44.27   42.75    43.6   41.87   42.35
      51    50.8   43.41   41.63   42.63    41.6   42.67   43.14   43.25   41.93
   41.93   41.32   42.92   43.78   42.71   44.47    44.8   46.27   43.41   44.68
   43.64   44.78   43.56   44.72   44.92   45.87   44.81   44.95    45.9   44.92
   44.81   43.52   44.83   45.47   44.56   45.94   45.08   46.27   46.03   47.18
   46.82   44.29   45.82   45.04   46.03   45.03   44.13   45.67   47.81   48.24
  1943.6  2313.6  2578.6  3108.6  3478.6  4108.6  4138.6  4183.6  4218.6  4233.6
  4278.6  4462.4  4487.4  4517.4  4672.4 4814.37 4932.57 4938.07 5070.47 5077.67
 5077.77  5358.1  5468.1  6053.1  6106.9  6156.9  7136.9  7256.2  7366.2  7781.2
  7891.2  7981.2  8026.2  8056.2  8381.2  8426.2  8718.1  9313.1  9328.1  9358.1
  9738.1  9803.1  9848.1  9973.1 10133.1 10708.1 10743.1 10859.7 11139.7 11159.7
 11279.7 11329.7 11449.7 12569.7 12789.7 12809.7 14119.7 14279.7 14299.7 14329.7
   47.56   47.88    45.5   46.34   44.08   44.27   42.75    43.6   41.87   42.35
      51    50.8   43.41   41.63   42.63    41.6   43.03   45.14   45.25   43.17
   41.93   41.32   42.92   43.78   42.71   44.47    44.8   46.27   43.41   44.68
   43.64   44.78   43.56   44.72   44.92   45.87   44.81   44.95    45.9   44.92
   44.81   43.52   44.83   45.47   44.56   45.94   45.08   46.27   46.03   47.18
   46.82   44.29   45.82   45.04   46.03   45.03   44.13   45.67   47.81   48.24
   47.56   47.88    45.5   46.34   44.08   44.27   42.75    43.6   41.87   42.35
      51    50.8   43.41   41.63   42.63    41.6   42.67   43.14   43.25   41.93
   41.93   41.32   42.92   43.78   42.71   44.47    44.8   46.27   43.41   44.68
   43.64   44.78   43.56   44.72   44.92   45.87   44.81   44.95    45.9   44.92
   44.81   43.52   44.83   45.47   44.56   45.94   45.08   46.27   46.03   47.18
   46.82   44.29   45.82   45.04   46.03   45.03   44.13   45.67   47.81   48.24
Pier Skew, UpSta & Num, DnSta & Num=  ,4943.8, 2 ,4943.8, 2 , 0 , 0 , 0 ,,
     1.4     1.4
   39.63   44.14
     1.4     1.4
   39.63   44.14
Pier Skew, UpSta & Num, DnSta & Num=  ,4983.3, 2 ,4983.3, 2 , 0 , 0 , 0 ,,
     1.4     1.4
   29.62   44.18
     1.4     1.4
   29.62   44.18
Pier Skew, UpSta & Num, DnSta & Num=  ,5023.8, 2 ,5023.8, 2 , 0 , 0 , 0 ,,
     1.4     1.4
   35.53   44.21
     1.4     1.4
   35.53   44.21
Pier Skew, UpSta & Num, DnSta & Num=  ,5063.6, 2 ,5063.6, 2 , 0 , 0 , 0 ,,
     1.4     1.4
   40.54   44.24
     1.4     1.4
   40.54   44.24
BR Coef= 1 , 1 , 0 ,1.25, 0 ,,,0.8,0,2,0,
WSPro=,,,, 1 ,,,, 0 ,,,, 0 ,,,,-1 ,-1 ,-1 , 0 , 0 , 0 , 0 , 0
BR U #Sta/Elev= 182
  1943.6   47.56  2173.6   46.99  2188.6   47.49  2283.6    47.3  2313.6   47.88
  2438.6   47.37  2468.6      46  2513.6   46.85  2533.6   46.31  2548.6   46.45
  2578.6    45.5  3043.6   46.08  3073.6   45.54  3108.6   46.34  3153.6   45.89
  3478.6   44.08  3498.6   44.58  3608.6    44.4  4098.6   44.12  4108.6   44.27
  4138.6   42.75  4183.6    43.6  4198.6   42.24  4218.6   41.87  4233.6   42.35
  4248.6   45.32  4278.6      51  4403.6   50.86  4462.4    50.8  4482.4   44.27
  4487.4   43.41  4502.4   41.92  4517.4   41.63  4672.4   42.63 4693.37   41.87
 4713.67   42.53 4758.07   41.49 4814.37    41.6 4877.87   42.77 4930.27   43.01
 4932.57   42.67 4932.68   42.65 4932.77   42.64 4938.07   41.85 4942.97   41.12
 4943.77   40.85 4960.47   35.66 4979.27   31.83 4983.27   30.57 4995.77    31.4
 4998.07   30.38 5000.77   29.96 5002.97   30.39 5004.27   31.17 5018.57   35.29
 5023.77   36.75 5028.37    35.3 5050.27    41.5 5063.57   41.54 5070.47   41.73
 5077.56   41.93 5077.67   41.93 5077.77   41.93 5084.17   42.11 5136.47   42.07
 5189.37   42.25 5250.97   42.09 5299.37   41.77 5349.77   41.96 5351.77   41.64
  5358.1   41.32  5403.6   41.98  5468.1   42.92  5803.6   43.41  6053.1   43.78
  6083.1   42.86  6091.9   42.87  6106.9   42.71  6111.9   42.82  6126.9   43.98
  6156.9   44.47  6236.9   43.89  6626.9   44.99  6766.9   44.39  7136.9    44.8
  7186.2   45.87  7256.2   46.27  7366.2   43.41  7381.2    43.6  7396.2   44.29
  7441.2   43.64  7456.2   44.46  7736.2   44.42  7781.2   44.68  7831.2    44.1
  7856.2   44.37  7891.2   43.64  7981.2   44.78  8026.2   43.56  8041.2   43.83
  8056.2   44.72  8381.2   44.92  8426.2   45.87  8441.2   45.11  8491.2   45.48
  8581.2   45.17  8583.1   45.11  8588.1   44.94  8598.1    45.1  8703.1   45.11
  8718.1   44.81  8793.1   45.53  8873.1   45.11  8888.1    45.5  9218.1   45.03
  9313.1   44.95  9328.1    45.9  9343.1   45.06  9358.1   44.92  9373.1   45.58
  9403.1   45.03  9418.1    45.4  9738.1   44.81  9768.1   43.69  9803.1   43.52
  9848.1   44.83  9898.1   45.04  9933.1    44.5  9973.1   45.47  9983.1   45.33
 10113.1   45.21 10133.1   44.56 10143.1   44.62 10153.1   45.05 10198.1   44.76
 10323.1   45.05 10563.1   45.54 10578.1   45.87 10663.1   45.07 10678.1    45.8
 10708.1   45.94 10723.1   45.47 10733.1   45.67 10743.1   45.08 10758.1   45.28
 10859.7   46.27 11139.7   46.03 11159.7   47.18 11279.7   46.82 11329.7   44.29
 11349.7   45.16 11389.7   45.51 11449.7   45.82 11489.7   45.31 11589.7   45.35
 11709.7   45.75 11729.7   45.12 11749.7   45.78 11779.7   45.56 11789.7   45.14
 11829.7   45.42 11839.7   45.14 11859.7    45.4 12099.7   45.44 12109.7   45.11
 12309.7   45.44 12329.7   45.15 12339.7   45.57 12569.7   45.04 12789.7   46.03
 12809.7   45.03 13049.7   44.84 13129.7   45.04 13439.7    44.8 13449.7    44.5
 13539.7   45.28 13809.7   44.07 13829.7   44.51 14119.7   44.13 14279.7   45.67
 14299.7   47.81 14329.7   48.24
BR U #Mann= 6
  1943.6     .99  4403.6      .1 4942.97    .035 5050.27      .1  5403.6      .2
  5803.6     .99
BR U Banks=4942.97,5050.27
BR D #Sta/Elev= 182
  1943.6   47.56  2173.6   46.99  2188.6   47.49  2283.6    47.3  2313.6   47.88
  2438.6   47.37  2468.6      46  2513.6   46.85  2533.6   46.31  2548.6   46.45
  2578.6    45.5  3043.6   46.08  3073.6   45.54  3108.6   46.34  3153.6   45.89
  3478.6   44.08  3498.6   44.58  3608.6    44.4  4098.6   44.12  4108.6   44.27
  4138.6   42.75  4183.6    43.6  4198.6   42.24  4218.6   41.87  4233.6   42.35
  4248.6   45.32  4278.6      51  4403.6   50.86  4462.4    50.8  4482.4   44.27
  4487.4   43.41  4502.4   41.92  4517.4   41.63  4672.4   42.63 4693.37   41.87
 4713.67   42.53 4758.07   41.49 4814.37    41.6 4877.87   42.77 4930.27   43.01
 4932.57   42.67 4932.68   42.65 4932.77   42.64 4938.07   41.85 4942.97   41.12
 4943.77   40.85 4960.47   35.66 4979.27   31.83 4983.27   30.57 4995.77    31.4
 4998.07   30.38 5000.77   29.96 5002.97   30.39 5004.27   31.17 5018.57   35.29
 5023.77   36.75 5028.37    35.3 5050.27    41.5 5063.57   41.54 5070.47   41.73
 5077.56   41.93 5077.67   41.93 5077.77   41.93 5084.17   42.11 5136.47   42.07
 5189.37   42.25 5250.97   42.09 5299.37   41.77 5349.77   41.96 5351.77   41.64
  5358.1   41.32  5403.6   41.98  5468.1   42.92  5803.6   43.41  6053.1   43.78
  6083.1   42.86  6091.9   42.87  6106.9   42.71  6111.9   42.82  6126.9   43.98
  6156.9   44.47  6236.9   43.89  6626.9   44.99  6766.9   44.39  7136.9    44.8
  7186.2   45.87  7256.2   46.27  7366.2   43.41  7381.2    43.6  7396.2   44.29
  7441.2   43.64  7456.2   44.46  7736.2   44.42  7781.2   44.68  7831.2    44.1
  7856.2   44.37  7891.2   43.64  7981.2   44.78  8026.2   43.56  8041.2   43.83
  8056.2   44.72  8381.2   44.92  8426.2   45.87  8441.2   45.11  8491.2   45.48
  8581.2   45.17  8583.1   45.11  8588.1   44.94  8598.1    45.1  8703.1   45.11
  8718.1   44.81  8793.1   45.53  8873.1   45.11  8888.1    45.5  9218.1   45.03
  9313.1   44.95  9328.1    45.9  9343.1   45.06  9358.1   44.92  9373.1   45.58
  9403.1   45.03  9418.1    45.4  9738.1   44.81  9768.1   43.69  9803.1   43.52
  9848.1   44.83  9898.1   45.04  9933.1    44.5  9973.1   45.47  9983.1   45.33
 10113.1   45.21 10133.1   44.56 10143.1   44.62 10153.1   45.05 10198.1   44.76
 10323.1   45.05 10563.1   45.54 10578.1   45.87 10663.1   45.07 10678.1    45.8
 10708.1   45.94 10723.1   45.47 10733.1   45.67 10743.1   45.08 10758.1   45.28
 10859.7   46.27 11139.7   46.03 11159.7   47.18 11279.7   46.82 11329.7   44.29
 11349.7   45.16 11389.7   45.51 11449.7   45.82 11489.7   45.31 11589.7   45.35
 11709.7   45.75 11729.7   45.12 11749.7   45.78 11779.7   45.56 11789.7   45.14
 11829.7   45.42 11839.7   45.14 11859.7    45.4 12099.7   45.44 12109.7   45.11
 12309.7   45.44 12329.7   45.15 12339.7   45.57 12569.7   45.04 12789.7   46.03
 12809.7   45.03 13049.7   44.84 13129.7   45.04 13439.7    44.8 13449.7    44.5
 13539.7   45.28 13809.7   44.07 13829.7   44.51 14119.7   44.13 14279.7   45.67
 14299.7   47.81 14329.7   48.24
BR D #Mann= 6
  1943.6     .99  4403.6      .1 4942.97    .035 5050.27      .1  5403.6      .2
  5803.6     .99
BR D Banks=4942.97,5050.27
BC Design=,, 0 ,, 0 ,,,,,,
BC HTab HWMax=51.03
BC Use User HTab Curves=0
BC User HTab FreeFlow(D)= 0

Type RM Length L Ch R = 1 ,71992.2 ,108,108,108
BEGIN DESCRIPTION:
Upstream Section of Bridge/Culvert/Weir
END DESCRIPTION:
XS GIS Cut Line= 6
      3132216.56     13862206.77      3132650.71      13859258.8
      3132706.67     13858189.21      3132626.77     13856995.15
      3131979.08     13853452.19      3132536.28     13849960.29
#Sta/Elev= 30
  1943.6   47.56  4108.6   44.27  4218.6   41.87  4233.6   42.35  4278.6      50
  4403.6   50.54  4462.4    50.8  4487.4   43.41  4517.4   41.63  4930.3   43.01
    4943   41.12  4983.3   30.57  5000.8   29.96  5050.3    41.5  5403.6   41.98
  5803.6   43.41  7256.2   46.27  7366.2   43.41  8426.2   45.87  9328.1    45.9
  9803.1   43.52  9973.1   45.47 10743.1   45.08 11159.7   47.18 11279.7   46.82
 11329.7   44.29 12789.7   46.03 14119.7   44.13 14279.7   45.67 14329.7   48.24
#Mann= 6 , 1 , 0
  1943.6     .99       0  4403.6      .1       0    4943    .035       0
  5050.3      .1       0  5403.6      .2       0  5803.6     .99       0
#XS Ineff= 2 , 0
       0    4375    50.4   10717       0    45.9
Permanent Ineff=
       F       F
Bank Sta=4943,5050.3
XS Rating Curve= 0 ,0
Exp/Cntr=0.5,0.3

Type RM Length L Ch R = 3 ,71938.2 ,,,
BEGIN DESCRIPTION:
HIRSCH STREET
Structure ID: H00-64
END DESCRIPTION:
Bridge Culvert--1,0,-1,-1, 0
Deck Dist Width WeirC Skew NumUp NumDn MinLoCord MaxHiCord MaxSubmerge Is_Ogee
10,88,2.6,0, 60, 60, , , 0.95, 0, 1,1,,
  1943.6  2313.6  2578.6  3108.6  3478.6  4108.6  4138.6  4183.6  4218.6  4233.6
  4278.6  4462.4  4487.4  4517.4  4672.4  4813.4 4929.69  4929.8 4938.31  4938.4
    4943 5058.09  5058.3  5067.4 5067.51  5136.4  5358.1  5468.1  6053.1  6106.9
  6156.9  7136.9  7256.2  7366.2  7781.2  7891.2  7981.2  8026.2  8056.2  8426.2
  8718.1  9313.1  9328.1  9738.1  9803.1  9973.1 10743.1 10859.7 11139.7 11159.7
 11279.7 11329.7 11449.7 12569.7 12789.7 12809.7 14119.7 14279.7 14299.7 14329.7
   47.56   47.88    45.5   46.34   44.08   44.27   42.75    43.6   41.87   42.35
      50    50.8   43.42   41.84   42.64   42.13   44.31   47.01   47.49   47.49
   47.49   47.38   47.38   47.09   44.39   42.69   41.33   42.93   43.79   43.47
   44.47    44.8   46.27   43.41   44.68   43.64   44.78   43.56   44.72   45.87
   44.81   44.95    45.9   44.81   43.52   45.47   45.08   46.27   46.03   47.18
   46.82   44.29   45.82   45.04   46.03   45.03   44.13   45.67   47.81   48.24
   47.56   47.88    45.5   46.34   44.08   44.27   42.75    43.6   41.87   42.35
      50    50.8   43.41   41.63   42.63    41.6   43.01   43.01   41.82   42.89
   42.89   42.78   41.52   41.65   41.65   42.07   41.32   42.92   43.78   42.71
   44.47    44.8   46.27   43.41   44.68   43.64   44.78   43.56   44.72   45.87
   44.81   44.95    45.9   44.81   43.52   45.47   45.08   46.27   46.03   47.18
   46.82   44.29   45.82   45.04   46.03   45.03   44.13   45.67   47.81   48.24
  1943.6  2313.6  2578.6  3108.6  3478.6  4108.6  4138.6  4183.6  4218.6  4233.6
  4278.6  4462.4  4487.4  4517.4  4672.4  4813.4 4929.69  4929.8 4938.31  4938.4
    4943 5058.09  5058.3  5067.4 5067.51  5136.4  5358.1  5468.1  6053.1  6106.9
  6156.9  7136.9  7256.2  7366.2  7781.2  7891.2  7981.2  8026.2  8056.2  8426.2
  8718.1  9313.1  9328.1  9738.1  9803.1  9973.1 10743.1 10859.7 11139.7 11159.7
 11279.7 11329.7 11449.7 12569.7 12789.7 12809.7 14119.7 14279.7 14299.7 14329.7
   47.56   47.88    45.5   46.34   44.08   44.27   42.75    43.6   41.87   42.35
      50    50.8   43.42   41.84   42.64   42.13   44.31   47.01   47.49   47.49
   47.49   47.38   47.38   47.09   44.39   42.69   41.33   42.93   43.79   43.47
   44.47    44.8   46.27   43.41   44.68   43.64   44.78   43.56   44.72   45.87
   44.81   44.95    45.9   44.81   43.52   45.47   45.08   46.27   46.03   47.18
   46.82   44.29   45.82   45.04   46.03   45.03   44.13   45.67   47.81   48.24
   47.46   47.78    45.4   46.24   43.98   44.17   42.65    43.5   41.77   42.25
    49.9    50.7   43.31   41.53   42.53    41.5   42.91   42.91   41.72   42.79
   42.79   42.68   41.42   41.55   41.55   41.97   41.22   42.82   43.68   42.61
   44.37    44.7   46.17   43.31   44.58   43.54   44.68   43.46   44.62   45.77
   44.71   44.85    45.8   44.71   43.42   45.37   44.98   46.17   45.93   47.08
   46.72   44.19   45.72   44.94   45.93   44.93   44.03   45.57   47.71   48.14
Pier Skew, UpSta & Num, DnSta & Num=  ,4979.3, 2 ,4979.3, 2 , 0 , 0 , 0 ,,
     1.4     1.4
   30.61   43.85
     1.4     1.4
   30.51   43.75
Pier Skew, UpSta & Num, DnSta & Num=  ,5018.6, 2 ,5018.6, 2 , 0 , 0 , 0 ,,
     1.4     1.4
   34.09   43.82
     1.4     1.4
   33.99   43.72
BR Coef= 1 , 1 , 0 ,1.25, 0 ,,,0.8,0,2,0,
WSPro=,,,, 1 ,,,, 0 ,,,, 0 ,,,,-1 ,-1 ,-1 , 0 , 0 , 0 , 0 , 0
BR U #Sta/Elev= 30
  1943.6   47.56  4108.6   44.27  4218.6   41.87  4233.6   42.35  4278.6      50
  4403.6   50.54  4462.4    50.8  4487.4   43.41  4517.4   41.63  4930.3   43.01
    4943   41.12  4983.3   30.57  5000.8   29.96  5050.3    41.5  5403.6   41.98
  5803.6   43.41  7256.2   46.27  7366.2   43.41  8426.2   45.87  9328.1    45.9
  9803.1   43.52  9973.1   45.47 10743.1   45.08 11159.7   47.18 11279.7   46.82
 11329.7   44.29 12789.7   46.03 14119.7   44.13 14279.7   45.67 14329.7   48.24
BR U #Mann= 6
  1943.6     .99  4403.6      .1    4943    .035  5050.3      .1  5403.6      .2
  5803.6     .99
BR U Banks=4943,5050.3
BR D #Sta/Elev= 30
  1943.6   47.46  4108.6   44.17  4218.6   41.77  4233.6   42.25  4278.6    49.9
  4403.6   50.44  4462.4    50.7  4487.4   43.31  4517.4   41.53  4930.3   42.91
    4943   41.02  4983.3   30.47  5000.8   29.86  5050.3    41.4  5403.6   41.88
  5803.6   43.31  7256.2   46.17  7366.2   43.31  8426.2   45.77  9328.1    45.8
  9803.1   43.42  9973.1   45.37 10743.1   44.98 11159.7   47.08 11279.7   46.72
 11329.7   44.19 12789.7   45.93 14119.7   44.03 14279.7   45.57 14329.7   48.14
BR D #Mann= 6
  1943.6     .99  4403.6      .1    4943    .035  5050.3      .1  5403.6      .2
  5803.6     .99
BR D Banks=4943,5050.3
BC Design=,, 0 ,, 0 ,,,,,,
BC HTab HWMax=50.8
BC Use User HTab Curves=0
BC User HTab FreeFlow(D)= 0

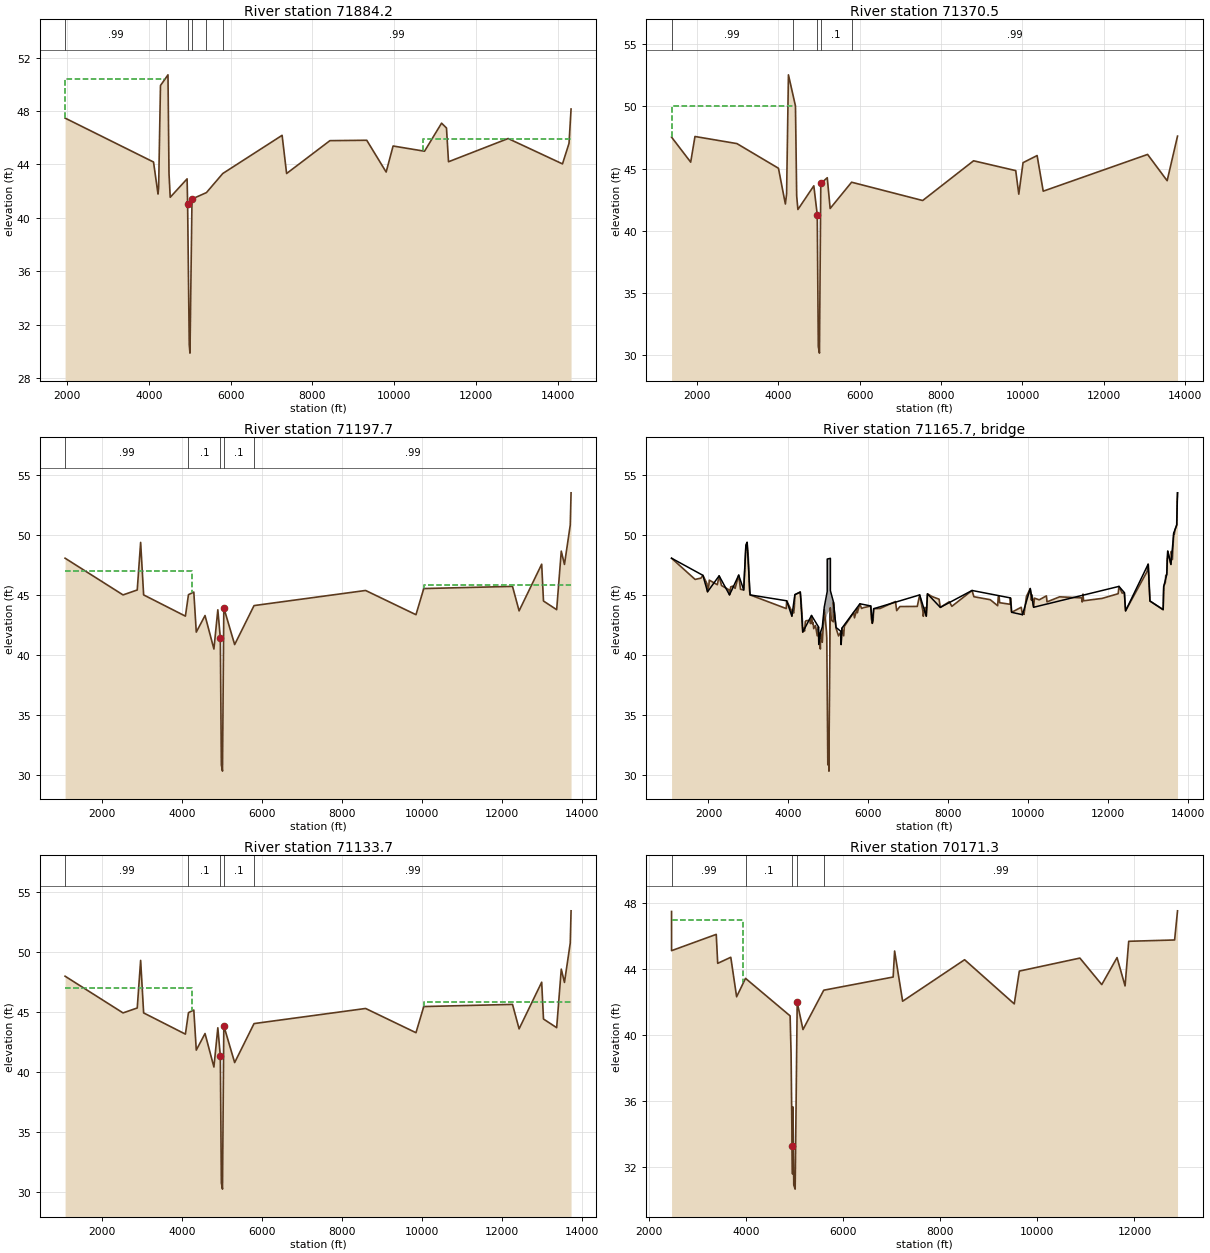
Type RM Length L Ch R = 1 ,71884.2 ,513.7,513.7,513.7
BEGIN DESCRIPTION:
Downstream Section of Bridge/Culvert/Weir
END DESCRIPTION:
XS GIS Cut Line= 6
      3132311.64     13862257.99      3132745.79     13859310.02
      3132801.75     13858240.43      3132721.85     13857046.37
      3132074.16     13853503.41      3132631.36     13850011.51
#Sta/Elev= 30
  1943.6   47.47  4108.6   44.18  4218.6   41.78  4233.6   42.26  4278.6   49.91
  4403.6   50.45  4462.4   50.71  4487.4   43.32  4517.4   41.54  4930.3   42.92
    4943   41.03  4983.3   30.48  5000.8   29.87  5050.3   41.41  5403.6   41.89
  5803.6   43.32  7256.2   46.18  7366.2   43.32  8426.2   45.78  9328.1   45.81
  9803.1   43.43  9973.1   45.38 10743.1   44.99 11159.7   47.09 11279.7   46.73
 11329.7    44.2 12789.7   45.94 14119.7   44.04 14279.7   45.58 14329.7   48.15
#Mann= 6 , 1 , 0
  1943.6     .99       0  4403.6      .1       0    4943    .035       0
  5050.3      .1       0  5403.6      .2       0  5803.6     .99       0
#XS Ineff= 2 , 0
       0    4375    50.4   10717       0    45.9
Permanent Ineff=
       F       F
Bank Sta=4943,5050.3
XS Rating Curve= 0 ,0
Exp/Cntr=0.5,0.3

Type RM Length L Ch R = 1 ,71370.5 ,177.6,172.8,123
BEGIN DESCRIPTION:
Cross Section 71370.5
END DESCRIPTION:
XS GIS Cut Line= 6
      3132429.16     13862784.81      3133284.76     13859399.59
      3133313.32     13857723.94      3133141.95     13856495.76
      3133170.51      13853668.1      3133116.99     13850483.54
#Sta/Elev= 30
  1382.4   47.53  1852.4   45.52  1957.4   47.58  2987.4   47.01  4007.4   45.03
  4177.4   42.16  4207.4   42.97  4252.4   52.53  4363.1   50.93  4425.1   50.03
  4455.1   42.81  4485.1   41.72  4875.9   43.62    4960    41.3  4985.9   30.71
  5014.3   30.19  5047.4   43.81  5205.9   44.27  5276.8    41.8  5803.7   43.91
  7548.8   42.44  8798.9   45.63  9833.9   44.84  9908.9   42.95 10013.9   45.48
 10358.9   46.05 10508.9   43.19   13072   46.14   13552   44.03   13807   47.61
#Mann= 5 , 1 , 0
  1382.4     .99       0  4363.1      .1       0    4960    .035       0
  5047.4      .1       0  5803.7     .99       0
#XS Ineff= 2 , 0
       0    4423      50   10183       0    45.7
Permanent Ineff=
       F       F
Bank Sta=4960,5047.4
XS Rating Curve= 0 ,0
Exp/Cntr=0.5,0.3

Type RM Length L Ch R = 1 ,71197.7 ,64,64,64
BEGIN DESCRIPTION:
Upstream Section of Bridge/Culvert/Weir
END DESCRIPTION:
XS GIS Cut Line= 6
      3133033.07      13863103.6      3133482.58      13859903.6
      3133438.42     13859445.67      3133479.13     13857835.47
      3133309.86     13856624.53      3133388.63     13850492.22
#Sta/Elev= 30
  1076.5   48.05  2526.5   44.99  2881.5    45.4  2966.5   49.37  3041.5   44.99
  4086.5   43.22  4163.1   45.01  4296.5   45.23  4358.5   41.89  4577.7   43.27
  4799.6   40.48  4897.7   43.75    4960   41.41  4985.9   30.82  5014.3    30.3
  5047.4   43.92  5318.7   40.85  5803.7    44.1  8594.6   45.36  9854.6   43.34
 10049.6   45.52 12269.6    45.7 12434.6   43.66 12999.6   47.55 13044.6   44.48
 13374.6   43.76 13489.6   48.64 13569.6   47.53 13714.6   50.82 13734.6    53.5
#Mann= 5 , 1 , 0
  1076.5     .99       0  4163.1      .1       0    4960    .035       0
  5047.4      .1       0  5803.7     .99       0
#XS Ineff= 2 , 0
       0    4260      47   10052       0    45.8
Permanent Ineff=
       F       F
Bank Sta=4960,5047.4
XS Rating Curve= 0 ,0
Exp/Cntr=0.5,0.3

Type RM Length L Ch R = 3 ,71165.7 ,,,
BEGIN DESCRIPTION:
WAYNE STREET
Structure ID: H00-62
END DESCRIPTION:
Bridge Culvert--1,0,-1,-1, 0
Deck Dist Width WeirC Skew NumUp NumDn MinLoCord MaxHiCord MaxSubmerge Is_Ogee
10,44,2.6,0, 60, 60, , , 0.95, 0, 1,1,,
  1076.5  1861.5  1976.5  2266.5  2526.5  2756.5  2881.5  2936.5  2966.5  3041.5
  3956.5  4086.5  4161.5  4296.5  4358.5  4577.7  4751.4    4761  4800.5  4847.3
  4897.7 4950.71  4950.8 4970.99  4971.1  5050.5 5050.61  5123.5    5126  5190.8
    5316  5318.7  5338.3  5788.3  6059.8  6098.8  6133.8  7283.8  7448.8  7478.8
  7799.6  8594.6  9554.6  9584.6  9854.6 10049.6 10134.6 12269.6 12404.6 12434.6
 12999.6 13044.6 13374.6 13389.6 13464.6 13489.6 13569.6 13639.6 13714.6 13734.6
   48.06   46.63   45.26   46.59      45   46.65   45.41   49.13   49.38      45
   44.51   43.23   45.02   45.24    41.9   43.29   42.34   40.88   41.87   42.32
      44   44.94   44.94   45.29   47.99   48.05   45.35   44.45   44.42   42.29
   41.95   40.87   42.23   44.26   44.08   42.63   43.85      45   43.23   45.09
   43.96   45.37   44.75   43.55   43.35   45.53   43.97   45.71   45.19   43.67
   47.56   44.49   43.77   45.71   46.69   48.65   47.54   50.15   50.83   53.51
   48.06   46.63   45.26   46.59      45   46.65   45.41   49.13   49.38      45
   44.51   43.23   45.02   45.24    41.9   43.28   42.33   40.87   41.86   41.05
   43.76   42.01   43.04   43.39   43.39    43.8    43.8   42.76   44.38   42.23
   41.94   40.86   42.22   44.25   44.07   42.63   43.85      45   43.23   45.09
   43.96   45.37   44.75   43.55   43.35   45.53   43.97   45.71   45.19   43.67
   47.56   44.49   43.77   45.71   46.69   48.65   47.54   50.15   50.83   53.51
  1076.5  1861.5  1976.5  2266.5  2526.5  2756.5  2881.5  2936.5  2966.5  3041.5
  3956.5  4086.5  4161.5  4296.5  4358.5  4577.7  4751.4    4761  4800.5  4847.3
  4897.7 4950.71  4950.8 4970.99  4971.1  5050.5 5050.61  5123.5    5126  5190.8
    5316  5318.7  5338.3  5788.3  6059.8  6098.8  6133.8  7283.8  7448.8  7478.8
  7799.6  8594.6  9554.6  9584.6  9854.6 10049.6 10134.6 12269.6 12404.6 12434.6
 12999.6 13044.6 13374.6 13389.6 13464.6 13489.6 13569.6 13639.6 13714.6 13734.6
   48.06   46.63   45.26   46.59      45   46.65   45.41   49.13   49.38      45
   44.51   43.23   45.02   45.24    41.9   43.29   42.34   40.88   41.87   42.32
      44   44.94   44.94   45.29   47.99   48.05   45.35   44.45   44.42   42.29
   41.95   40.87   42.23   44.26   44.08   42.63   43.85      45   43.23   45.09
   43.96   45.37   44.75   43.55   43.35   45.53   43.97   45.71   45.19   43.67
   47.56   44.49   43.77   45.71   46.69   48.65   47.54   50.15   50.83   53.51
   47.96   46.53   45.16   46.49    44.9   46.55   45.31   49.03   49.28    44.9
   44.41   43.13   44.92   45.14    41.8   43.18   42.23   40.77   41.76   40.95
   43.66   41.91   42.94   43.29   43.29    43.7    43.7   42.66   44.28   42.13
   41.84   40.76   42.12   44.15   43.97   42.53   43.75    44.9   43.13   44.99
   43.86   45.27   44.65   43.45   43.25   45.43   43.87   45.61   45.09   43.57
   47.46   44.39   43.67   45.61   46.59   48.55   47.44   50.05   50.73   53.41
Pier Skew, UpSta & Num, DnSta & Num=  ,5010.6, 2 ,5010.6, 2 , 0 , 0 , 0 ,,
     1.4     1.4
   30.59   44.42
     1.4     1.4
   30.49   44.32
BR Coef= 1 , 1 , 0 ,1.25, 0 ,,,0.8,0,2,0,
WSPro=,,,, 1 ,,,, 0 ,,,, 0 ,,,,-1 ,-1 ,-1 , 0 , 0 , 0 , 0 , 0
BR U #Sta/Elev= 196
  1076.5   48.06  1666.5   46.29  1811.5    46.4  1861.5   46.63  1961.5   45.94
  1976.5   45.26  2011.5   45.86  2021.5   46.23  2221.5   45.85  2266.5   46.59
  2326.5   45.78  2511.5   45.43  2526.5      45  2556.5   45.67  2616.5   45.74
  2666.5   45.55  2756.5   46.65  2801.5   45.47  2881.5   45.41  2936.5   49.13
  2966.5   49.38  2996.5   48.11  3026.5   45.38  3041.5      45  3946.5   43.86
  3956.5   44.51  4071.5   43.72  4086.5   43.23  4101.5   43.68  4131.5   43.49
  4146.5   43.93  4161.5   45.02  4163.1   45.02  4296.5   45.24  4318.5   44.47
  4348.5   42.91  4358.5    41.9  4363.1   41.97  4378.5   42.22  4403.5   41.98
  4423.5   42.78  4442.7   42.85  4542.7   42.88  4552.7   42.61  4577.7   43.28
  4602.7   42.57  4617.7    42.7  4632.7   42.19  4676.4   42.45  4721.4   41.59
  4751.4   42.33    4761   40.87  4763.2   41.65  4763.3   41.65  4799.6   40.49
  4800.5   41.86  4801.1   41.85  4847.3   41.05  4847.4   41.06  4897.5   43.75
  4897.7   43.76  4948.1   42.17 4950.71   42.01  4950.8      42  4950.9   41.99
    4960   41.42  4970.8   37.18 4970.99    37.1  4971.1   37.06 4971.21   37.02
  4972.4   36.55  4985.3   32.16  4985.9   30.83  5010.6   31.68  5011.1   31.67
  5014.3   30.31  5014.7   31.88  5030.4   37.47    5046   43.45  5047.4   43.93
 5050.39   43.81  5050.5    43.8 5050.61    43.8    5051   43.78  5051.1   43.78
 5051.19   43.77  5051.3   43.77  5072.1    42.9  5073.9    42.9  5123.5   42.76
    5126   44.38  5127.5   44.33  5190.8   42.23  5191.8   42.22  5254.7   41.58
  5254.8   41.58  5313.1   41.92    5316   41.94  5318.7   40.86  5338.3   42.22
  5351.2   42.04  5383.3   41.59  5391.2      42  5398.3   42.37  5436.2   42.56
  5633.3   43.53  5653.3   43.09  5713.3   43.85  5723.3   43.51  5788.3   44.25
  5803.7   44.11  5829.8   43.87  5879.8   43.94  5951.2   43.99  6059.8   44.07
  6073.7   43.09  6074.8   43.01  6098.8   42.63  6118.8   42.84  6133.8   43.85
  6293.8   43.87  6678.8   44.45  6708.8   43.69  6788.8   44.03  7223.8   44.04
  7283.8      45  7363.8   43.67  7373.8   43.22  7418.8   43.96  7448.8   43.23
  7478.8   45.09  7589.6   44.87  7769.6   44.64  7799.6   43.96  8024.6   44.43
  8089.6   44.05  8594.6   45.37  8639.6   44.85  9049.6    44.6  9234.6    44.1
  9249.6   44.85  9269.6    44.9  9284.6   44.35  9544.6   44.22  9554.6   44.75
  9574.6   44.07  9579.6   43.64  9584.6   43.55  9824.6   43.97  9854.6   43.35
  9884.6   43.66  9894.6   43.38  9954.6   44.87 10049.6   45.53 10079.6   44.56
 10094.6      45 10134.6   43.97 10154.6   44.73 10274.6   44.59 10454.6   44.92
 10469.6   44.42 10784.6   44.84 11339.6   44.75 11349.6   44.41 11369.6   45.07
 11384.6   44.51 11849.6   44.71 12249.6    45.1 12269.6   45.71 12349.6   45.15
 12404.6   45.19 12434.6   43.67 12974.6   46.96 12999.6   47.56 13004.6    47.5
 13044.6   44.49 13374.6   43.77 13379.6   44.23 13384.6    45.3 13389.6   45.71
 13429.6   46.03 13439.6   46.63 13464.6   46.69 13469.6    47.1 13474.6   47.97
 13484.6   48.21 13489.6   48.65 13569.6   47.54 13579.6   48.63 13604.6   47.95
 13639.6   50.15 13654.6   50.07 13669.6   50.41 13714.6   50.83 13724.6   52.84
 13734.6   53.51
BR U #Mann= 5
  1076.5     .99  4163.1      .1    4960    .035  5047.4      .1  5803.7     .99
BR U Banks=4960,5047.4
BR D #Sta/Elev= 196
  1076.5   47.96  1666.5   46.19  1811.5    46.3  1861.5   46.53  1961.5   45.84
  1976.5   45.16  2011.5   45.76  2021.5   46.13  2221.5   45.75  2266.5   46.49
  2326.5   45.68  2511.5   45.33  2526.5    44.9  2556.5   45.57  2616.5   45.64
  2666.5   45.45  2756.5   46.55  2801.5   45.37  2881.5   45.31  2936.5   49.03
  2966.5   49.28  2996.5   48.01  3026.5   45.28  3041.5    44.9  3946.5   43.76
  3956.5   44.41  4071.5   43.62  4086.5   43.13  4101.5   43.58  4131.5   43.39
  4146.5   43.83  4161.5   44.92  4163.1   44.92  4296.5   45.14  4318.5   44.37
  4348.5   42.81  4358.5    41.8  4363.1   41.87  4378.5   42.12  4403.5   41.88
  4423.5   42.68  4442.7   42.75  4542.7   42.78  4552.7   42.51  4577.7   43.18
  4602.7   42.47  4617.7    42.6  4632.7   42.09  4676.4   42.35  4721.4   41.49
  4751.4   42.23    4761   40.77  4763.2   41.55  4763.3   41.55  4799.6   40.39
  4800.5   41.76  4801.1   41.75  4847.3   40.95  4847.4   40.96  4897.5   43.65
  4897.7   43.66  4948.1   42.07 4950.71   41.91  4950.8    41.9  4950.9   41.89
    4960   41.32  4970.8   37.08 4970.99      37  4971.1   36.96 4971.21   36.92
  4972.4   36.45  4985.3   32.06  4985.9   30.73  5010.6   31.58  5011.1   31.57
  5014.3   30.21  5014.7   31.78  5030.4   37.37    5046   43.35  5047.4   43.83
 5050.39   43.71  5050.5    43.7 5050.61    43.7    5051   43.68  5051.1   43.68
 5051.19   43.67  5051.3   43.67  5072.1    42.8  5073.9    42.8  5123.5   42.66
    5126   44.28  5127.5   44.23  5190.8   42.13  5191.8   42.12  5254.7   41.48
  5254.8   41.48  5313.1   41.82    5316   41.84  5318.7   40.76  5338.3   42.12
  5351.2   41.94  5383.3   41.49  5391.2    41.9  5398.3   42.27  5436.2   42.46
  5633.3   43.43  5653.3   42.99  5713.3   43.75  5723.3   43.41  5788.3   44.15
  5803.7   44.01  5829.8   43.77  5879.8   43.84  5951.2   43.89  6059.8   43.97
  6073.7   42.99  6074.8   42.91  6098.8   42.53  6118.8   42.74  6133.8   43.75
  6293.8   43.77  6678.8   44.35  6708.8   43.59  6788.8   43.93  7223.8   43.94
  7283.8    44.9  7363.8   43.57  7373.8   43.12  7418.8   43.86  7448.8   43.13
  7478.8   44.99  7589.6   44.77  7769.6   44.54  7799.6   43.86  8024.6   44.33
  8089.6   43.95  8594.6   45.27  8639.6   44.75  9049.6    44.5  9234.6      44
  9249.6   44.75  9269.6    44.8  9284.6   44.25  9544.6   44.12  9554.6   44.65
  9574.6   43.97  9579.6   43.54  9584.6   43.45  9824.6   43.87  9854.6   43.25
  9884.6   43.56  9894.6   43.28  9954.6   44.77 10049.6   45.43 10079.6   44.46
 10094.6    44.9 10134.6   43.87 10154.6   44.63 10274.6   44.49 10454.6   44.82
 10469.6   44.32 10784.6   44.74 11339.6   44.65 11349.6   44.31 11369.6   44.97
 11384.6   44.41 11849.6   44.61 12249.6      45 12269.6   45.61 12349.6   45.05
 12404.6   45.09 12434.6   43.57 12974.6   46.86 12999.6   47.46 13004.6    47.4
 13044.6   44.39 13374.6   43.67 13379.6   44.13 13384.6    45.2 13389.6   45.61
 13429.6   45.93 13439.6   46.53 13464.6   46.59 13469.6      47 13474.6   47.87
 13484.6   48.11 13489.6   48.55 13569.6   47.44 13579.6   48.53 13604.6   47.85
 13639.6   50.05 13654.6   49.97 13669.6   50.31 13714.6   50.73 13724.6   52.74
 13734.6   53.41
BR D #Mann= 5
  1076.5     .99  4163.1      .1    4960    .035  5047.4      .1  5803.7     .99
BR D Banks=4960,5047.4
BC Design=,, 0 ,, 0 ,,,,,,
BC HTab HWMax=53.5
BC Use User HTab Curves=0
BC User HTab FreeFlow(D)= 0

Type RM Length L Ch R = 1 ,71133.7 ,962.4,962.4,962.4
BEGIN DESCRIPTION:
Downstream Section of Bridge/Culvert/Weir
END DESCRIPTION:
XS GIS Cut Line= 6
      3133092.96     13863081.02      3133542.46     13859881.02
       3133498.3     13859423.09      3133539.01     13857812.89
      3133369.74     13856601.95      3133448.51     13850469.64
#Sta/Elev= 30
  1076.5   47.96  2526.5    44.9  2881.5   45.31  2966.5   49.28  3041.5    44.9
  4086.5   43.13  4163.1   44.92  4296.5   45.14  4358.5    41.8  4577.7   43.18
  4799.6   40.39  4897.7   43.66    4960   41.32  4985.9   30.73  5014.3   30.21
  5047.4   43.83  5318.7   40.76  5803.7   44.01  8594.6   45.27  9854.6   43.25
 10049.6   45.43 12269.6   45.61 12434.6   43.57 12999.6   47.46 13044.6   44.39
 13374.6   43.67 13489.6   48.55 13569.6   47.44 13714.6   50.73 13734.6   53.41
#Mann= 5 , 1 , 0
  1076.5     .99       0  4163.1      .1       0    4960    .035       0
  5047.4      .1       0  5803.7     .99       0
#XS Ineff= 2 , 0
       0    4260      47   10052       0    45.8
Permanent Ineff=
       F       F
Bank Sta=4960,5047.4
XS Rating Curve= 0 ,0
Exp/Cntr=0.5,0.3

Type RM Length L Ch R = 1 ,70171.3 ,200.8,188.1,144.2
BEGIN DESCRIPTION:
Cross Section 70171.3
END DESCRIPTION:
XS GIS Cut Line= 6
      3133985.53     13861547.49      3134170.19     13860342.14
      3134293.96      13860094.6      3134370.13     13859580.48
      3134446.29     13856410.07      3134701.94     13851188.49
#Sta/Elev= 30
  2469.6    47.5  2469.7   45.12  3389.7   46.11  3419.7   44.35    3689   44.72
    3809   42.32  3992.2   43.44  4910.5   41.16  4930.5   38.82  4950.5   33.26
  4960.5   31.56  4969.7   35.63  4985.8   30.89  5014.2   30.64  5056.3   41.98
  5175.5   40.33  5602.9   42.72  7031.6   43.52  7061.6    45.1  7226.6   42.05
  8502.6   44.57  9524.6   41.89  9629.6   43.88 10876.1   44.67 11326.1   43.06
 11641.1    44.7 11806.1   42.98 11881.1   45.69 12826.1   45.77 12886.1   47.54
#Mann= 5 , 1 , 0
  2469.6     .99       0  3992.2      .1       0  4950.5    .035       0
  5056.3      .1       0  5602.9     .99       0
#XS Ineff= 2 , 0
       0    3944      47               0
Permanent Ineff=
       F       F
Bank Sta=4950.5,5056.3
XS Rating Curve= 0 ,0
Exp/Cntr=0.5,0.3

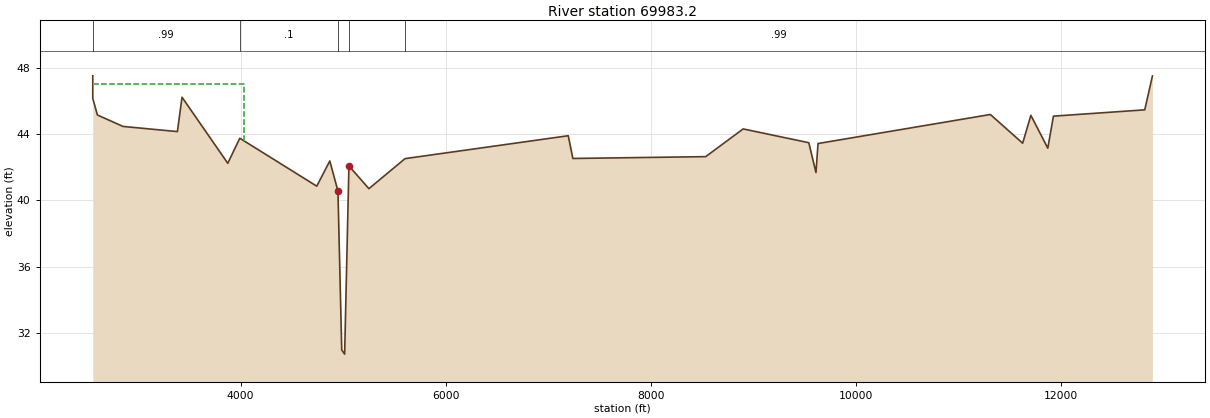
Type RM Length L Ch R = 1 ,69983.2 ,66,66,66
BEGIN DESCRIPTION:
Upstream Section of Bridge/Culvert/Weir
END DESCRIPTION:
XS GIS Cut Line= 6
      3134082.77     13861518.83      3134207.72      13860663.2
      3134533.24     13860025.18      3134599.76     13858318.94
      3134598.34     13857329.87      3134896.21     13851284.87
#Sta/Elev= 30
  2558.8    47.5  2558.9   46.14  2603.9   45.14  2853.9   44.45  3383.9   44.14
  3428.9   46.21  3874.9   42.23  3992.2   43.74  4742.4   40.85  4869.5   42.37
  4948.9   40.56  4985.8   30.98  5014.2   30.73    5056   42.07  5250.8    40.7
  5602.9   42.51    7194   43.89    7239   42.52    8534   42.63    8899    44.3
    9539   43.47    9609   41.67    9629   43.42   11309   45.17   11624   43.44
   11704   45.12   11869   43.14   11924   45.07   12814   45.45   12889   47.49
#Mann= 5 , 1 , 0
  2558.8     .99       0  3992.2      .1       0  4948.9    .035       0
    5056      .1       0  5602.9     .99       0
#XS Ineff= 2 , 0
       0    4033      47    5056       0      42
Permanent Ineff=
       F       F
Bank Sta=4948.9,5056
XS Rating Curve= 0 ,0
Exp/Cntr=0.5,0.3