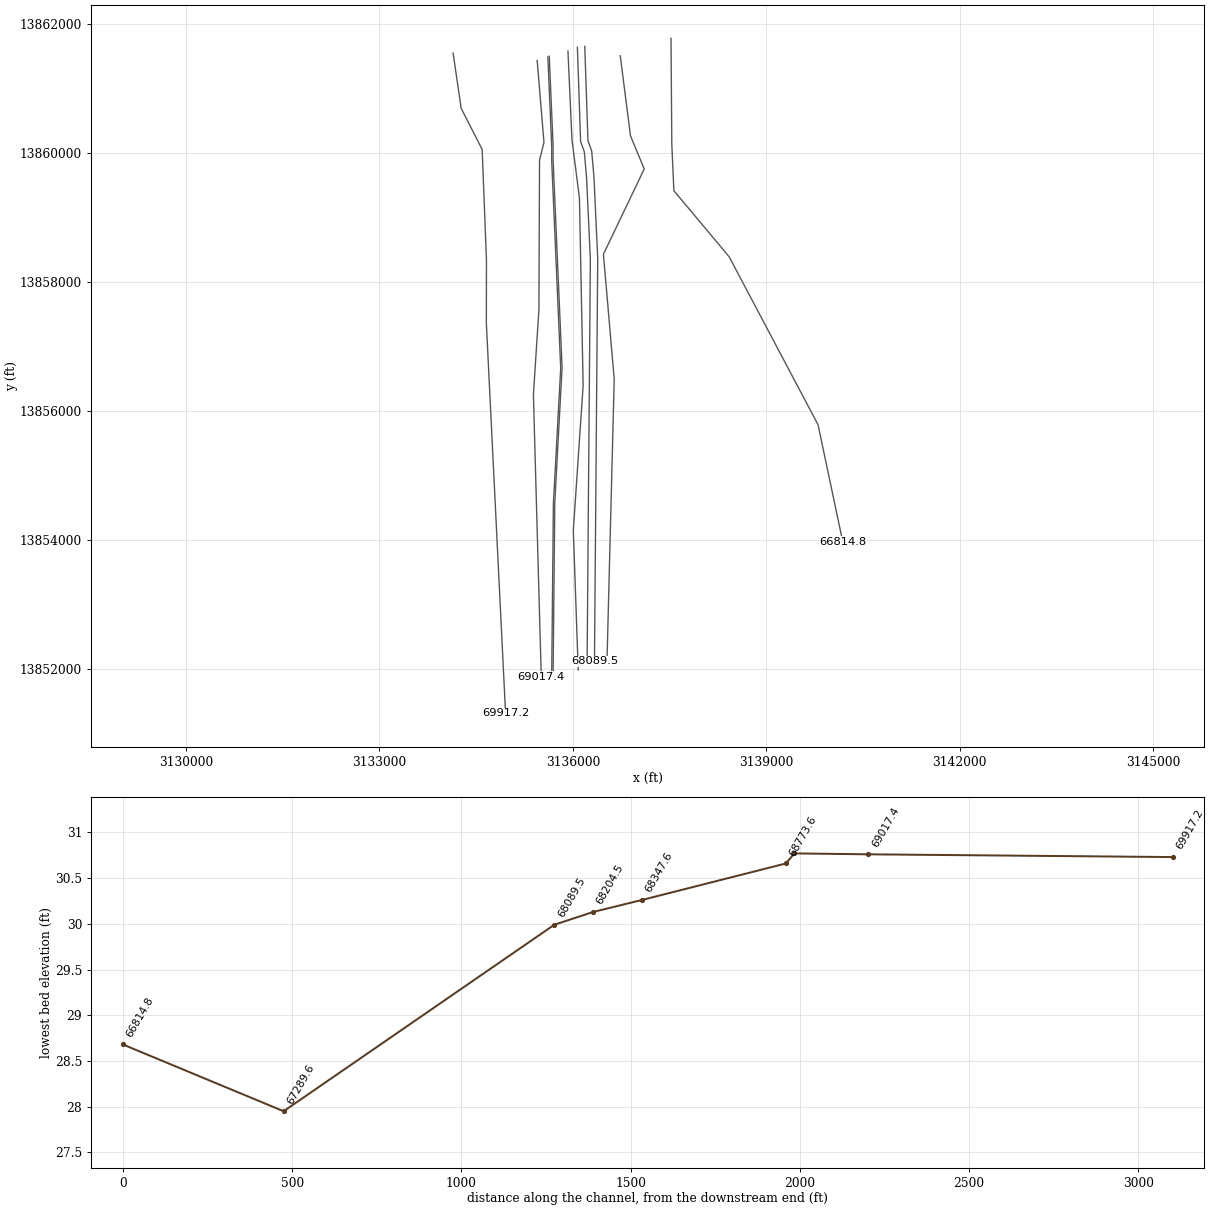
HEC-RAS study H100-00-00.prj: H100-00-00

--- H100-00-00.g01 (geometry) --- (continued)

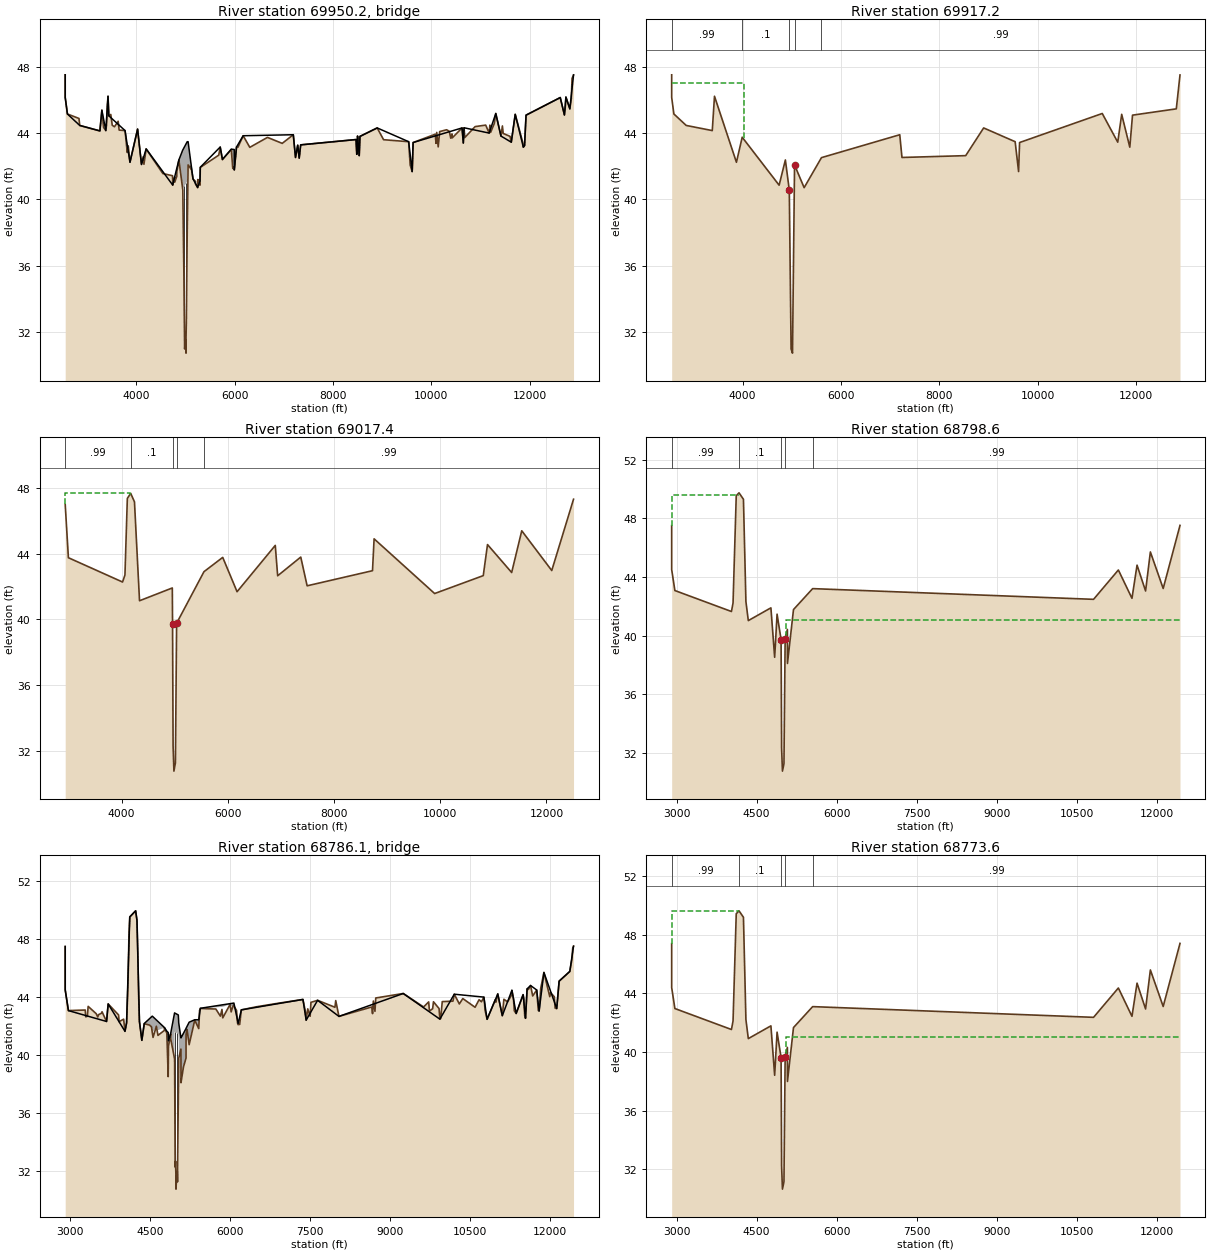
Type RM Length L Ch R = 3 ,69950.2 ,,,
BEGIN DESCRIPTION:
WHIPPRECHIT ROAD
Structure ID: H00-61
END DESCRIPTION:
Bridge Culvert--1,0,-1,-1, 0
Deck Dist Width WeirC Skew NumUp NumDn MinLoCord MaxHiCord MaxSubmerge Is_Ogee
10,46,2.6,0, 60, 60, , , 0.95, 0, 1,1,,
  2558.8  2558.9  2603.9  2853.9  3263.9  3303.9  3383.9  3428.9  3444.9  3774.9
  3874.9  4029.9  4108.8  4203.8  4742.4  4869.5 4946.21  5038.2  5056.2  5156.1
  5250.8  5298.2    5304    5709    5754    5934  5993.9  5995.3  6040.3  6175.3
    7194    7239    7284    7314    7344    8469    8484    8499    8534    8549
    8899    9539    9609    9629   10624   10649   10664   11174   11309   11414
   11624   11704   11869   11894   11924   12619   12704   12734   12814   12889
    47.5   46.14   45.14   44.45   44.12   45.37   44.14   46.21   45.03   44.14
   42.23   44.23    42.1   43.04   40.86   42.38   42.96   43.47   43.47   41.23
   40.71   41.13   41.93   43.15    42.4   43.02      43   41.77   43.15   43.83
   43.89   42.52   43.26   42.48   43.28    43.6   42.71   43.81   42.63   43.79
    44.3   43.47   41.67   43.42    44.3   43.39   44.31   43.99   45.17   43.81
   43.44   45.12   43.14   43.24   45.07   46.13   45.08   46.16   45.45   47.49
    47.5   46.14   45.14   44.45   44.12   45.37   44.14   46.21   45.03   44.14
   42.23   44.23    42.1   43.03   40.85   42.37   40.62   41.07   42.07   41.22
    40.7   40.85   41.92   43.14   42.39   43.01   41.78   41.77   43.15   43.83
   43.89   42.52   43.26   42.48   43.28    43.6   42.71   43.81   42.63   43.79
    44.3   43.47   41.67   43.42    44.3   43.39   44.31   43.99   45.17   43.81
   43.44   45.12   43.14   43.24   45.07   46.13   45.08   46.16   45.45   47.49
  2558.8  2558.9  2603.9  2853.9  3263.9  3303.9  3383.9  3428.9  3444.9  3774.9
  3874.9  4029.9  4108.8  4203.8  4742.4  4869.5 4946.21  5038.2  5056.2  5156.1
  5250.8  5298.2    5304    5709    5754    5934  5993.9  5995.3  6040.3  6175.3
    7194    7239    7284    7314    7344    8469    8484    8499    8534    8549
    8899    9539    9609    9629   10624   10649   10664   11174   11309   11414
   11624   11704   11869   11894   11924   12619   12704   12734   12814   12889
    47.5   46.14   45.14   44.45   44.12   45.37   44.14   46.21   45.03   44.14
   42.23   44.23    42.1   43.04   40.86   42.38   42.96   43.47   43.47   41.23
   40.71   41.13   41.93   43.15    42.4   43.02      43   41.77   43.15   43.83
   43.89   42.52   43.26   42.48   43.28    43.6   42.71   43.81   42.63   43.79
    44.3   43.47   41.67   43.42    44.3   43.39   44.31   43.99   45.17   43.81
   43.44   45.12   43.14   43.24   45.07   46.13   45.08   46.16   45.45   47.49
    47.5   46.14   45.14   44.45   44.12   45.37   44.14   46.21   45.03   44.14
   42.23   44.23    42.1   43.03   40.85   42.37   40.62   41.07   42.07   41.22
    40.7   40.85   41.92   43.14   42.39   43.01   41.78   41.77   43.15   43.83
   43.89   42.52   43.26   42.48   43.28    43.6   42.71   43.81   42.63   43.79
    44.3   43.47   41.67   43.42    44.3   43.39   44.31   43.99   45.17   43.81
   43.44   45.12   43.14   43.24   45.07   46.13   45.08   46.16   45.45   47.49
Pier Skew, UpSta & Num, DnSta & Num=  ,4980.3, 2 ,4980.3, 2 , 0 , 0 , 0 ,,
     1.4     1.4
   31.45   42.06
     1.4     1.4
   31.45   42.06
Pier Skew, UpSta & Num, DnSta & Num=  ,5020.6, 2 ,5020.6, 2 , 0 , 0 , 0 ,,
     1.4     1.4
   31.52   42.07
     1.4     1.4
   31.52   42.07
BR Coef= 1 , 1 , 0 ,1.25, 0 ,,,0.8,0,2,0,
WSPro=,,,, 1 ,,,, 0 ,,,, 0 ,,,,-1 ,-1 ,-1 , 0 , 0 , 0 , 0 , 0
BR U #Sta/Elev= 158
  2558.8    47.5  2558.9   46.14  2603.9   45.14  2838.9   44.87  2853.9   44.45
  3263.9   44.12  3303.9   45.37  3338.9   44.33  3383.9   44.14  3398.9   44.47
  3413.9    45.6  3428.9   46.21  3434.9   45.75  3444.9   45.03  3484.9   45.11
  3514.9   44.46  3559.9   44.37  3634.9    44.7  3654.9   44.17  3774.9   44.14
  3819.9   42.82  3839.9   43.22  3874.9   42.23  3992.2   43.74  4029.9   44.23
  4108.8    42.1  4143.8   42.56  4158.8   42.11  4192.2   42.79  4203.8   43.03
    4544   41.55  4739.4   41.42  4741.9    41.2  4742.3   41.16  4742.4   40.85
  4784.3   41.35  4784.5   41.35  4784.7   41.03  4826.7   41.39  4826.9   41.39
  4827.2   41.66  4869.5   42.37  4870.6   42.33  4871.8    42.3 4946.21   40.62
  4946.3   40.62  4946.4   40.62  4946.5   40.61 4946.59   40.61  4946.7   40.61
 4946.81   40.61  4948.9   40.56  4969.7   35.72  4980.3   32.59  4985.1   31.62
  4985.8   30.98  5000.5   31.57  5014.2   30.73  5014.8   31.72  5020.6   32.63
  5038.2   37.99    5056   42.07 5056.09   42.07  5056.2   42.07 5056.31   42.07
  5056.4   42.07 5056.49   42.07  5056.6   42.07  5056.7   42.07    5113   41.84
  5114.1   41.99  5114.2      42  5156.1   41.22  5156.9   41.22  5205.2   41.08
  5205.6   40.93    5206   40.93  5249.8   40.71  5250.8    40.7  5252.4   41.19
  5280.3   41.14  5298.2   40.85  5299.1   41.02    5304   41.92  5602.9   42.51
    5679   42.66    5709   43.14    5754   42.39    5934   43.01    5964   41.86
  5970.3   41.94  5993.9   41.78  5995.3   41.77  6040.3   43.15  6070.3   43.14
  6175.3   43.83  6310.3   43.13    6669   43.73    6969   43.37    7194   43.89
    7239   42.52    7284   43.26    7314   42.48    7344   43.28    8469    43.6
    8484   42.71    8489   42.83    8499   43.81    8519   43.65    8529   42.77
    8534   42.63    8549   43.79    8899    44.3    9029   43.59    9539   43.47
    9569   42.07    9609   41.67    9614   41.82    9629   43.42   10079   43.92
   10094   43.37   10109   44.03   10139   43.16   10169   44.08   10309   44.19
   10364    44.1   10394   43.68   10419   43.94   10424    43.7   10624    44.3
   10649   43.39   10664   44.31   10679   43.72   10889   44.38   11104   44.47
   11174   43.99   11189   44.47   11204   44.03   11279   44.57   11309   45.17
   11414   43.81   11444   44.42   11459   43.97   11599   43.79   11624   43.44
   11704   45.12   11854   43.46   11869   43.14   11894   43.24   11924   45.07
   12619   46.13   12704   45.08   12724   45.62   12734   46.16   12814   45.45
   12844   46.07   12859   47.28   12889   47.49
BR U #Mann= 5
  2558.8     .99  3992.2      .1  4948.9    .035    5056      .1  5602.9     .99
BR U Banks=4948.9,5056
BR D #Sta/Elev= 158
  2558.8    47.5  2558.9   46.14  2603.9   45.14  2838.9   44.87  2853.9   44.45
  3263.9   44.12  3303.9   45.37  3338.9   44.33  3383.9   44.14  3398.9   44.47
  3413.9    45.6  3428.9   46.21  3434.9   45.75  3444.9   45.03  3484.9   45.11
  3514.9   44.46  3559.9   44.37  3634.9    44.7  3654.9   44.17  3774.9   44.14
  3819.9   42.82  3839.9   43.22  3874.9   42.23  3992.2   43.74  4029.9   44.23
  4108.8    42.1  4143.8   42.56  4158.8   42.11  4192.2   42.79  4203.8   43.03
    4544   41.55  4739.4   41.42  4741.9    41.2  4742.3   41.16  4742.4   40.85
  4784.3   41.35  4784.5   41.35  4784.7   41.03  4826.7   41.39  4826.9   41.39
  4827.2   41.66  4869.5   42.37  4870.6   42.33  4871.8    42.3 4946.21   40.62
  4946.3   40.62  4946.4   40.62  4946.5   40.61 4946.59   40.61  4946.7   40.61
 4946.81   40.61  4948.9   40.56  4969.7   35.72  4980.3   32.59  4985.1   31.62
  4985.8   30.98  5000.5   31.57  5014.2   30.73  5014.8   31.72  5020.6   32.63
  5038.2   37.99    5056   42.07 5056.09   42.07  5056.2   42.07 5056.31   42.07
  5056.4   42.07 5056.49   42.07  5056.6   42.07  5056.7   42.07    5113   41.84
  5114.1   41.99  5114.2      42  5156.1   41.22  5156.9   41.22  5205.2   41.08
  5205.6   40.93    5206   40.93  5249.8   40.71  5250.8    40.7  5252.4   41.19
  5280.3   41.14  5298.2   40.85  5299.1   41.02    5304   41.92  5602.9   42.51
    5679   42.66    5709   43.14    5754   42.39    5934   43.01    5964   41.86
  5970.3   41.94  5993.9   41.78  5995.3   41.77  6040.3   43.15  6070.3   43.14
  6175.3   43.83  6310.3   43.13    6669   43.73    6969   43.37    7194   43.89
    7239   42.52    7284   43.26    7314   42.48    7344   43.28    8469    43.6
    8484   42.71    8489   42.83    8499   43.81    8519   43.65    8529   42.77
    8534   42.63    8549   43.79    8899    44.3    9029   43.59    9539   43.47
    9569   42.07    9609   41.67    9614   41.82    9629   43.42   10079   43.92
   10094   43.37   10109   44.03   10139   43.16   10169   44.08   10309   44.19
   10364    44.1   10394   43.68   10419   43.94   10424    43.7   10624    44.3
   10649   43.39   10664   44.31   10679   43.72   10889   44.38   11104   44.47
   11174   43.99   11189   44.47   11204   44.03   11279   44.57   11309   45.17
   11414   43.81   11444   44.42   11459   43.97   11599   43.79   11624   43.44
   11704   45.12   11854   43.46   11869   43.14   11894   43.24   11924   45.07
   12619   46.13   12704   45.08   12724   45.62   12734   46.16   12814   45.45
   12844   46.07   12859   47.28   12889   47.49
BR D #Mann= 5
  2558.8     .99  3992.2      .1  4948.9    .035    5056      .1  5602.9     .99
BR D Banks=4948.9,5056
BC Design=,, 0 ,, 0 ,,,,,,
BC HTab HWMax=47.5
BC Use User HTab Curves=0
BC User HTab FreeFlow(D)= 0

Type RM Length L Ch R = 1 ,69917.2 ,899.8,899.8,899.8
BEGIN DESCRIPTION:
Downstream Section of Bridge/Culvert/Weir
END DESCRIPTION:
XS GIS Cut Line= 6
      3134143.82     13861543.92      3134268.76     13860688.28
      3134594.28     13860050.26       3134660.8     13858344.02
      3134659.38     13857354.95      3134957.25     13851309.96
#Sta/Elev= 30
  2558.8    47.5  2558.9   46.14  2603.9   45.14  2853.9   44.45  3383.9   44.14
  3428.9   46.21  3874.9   42.23  3992.2   43.74  4742.4   40.85  4869.5   42.37
  4948.9   40.56  4985.8   30.98  5014.2   30.73    5056   42.07  5250.8    40.7
  5602.9   42.51    7194   43.89    7239   42.52    8534   42.63    8899    44.3
    9539   43.47    9609   41.67    9629   43.42   11309   45.17   11624   43.44
   11704   45.12   11869   43.14   11924   45.07   12814   45.45   12889   47.49
#Mann= 5 , 1 , 0
  2558.8     .99       0  3992.2      .1       0  4948.9    .035       0
    5056      .1       0  5602.9     .99       0
#XS Ineff= 2 , 0
       0    4033      47    5056       0      42
Permanent Ineff=
       F       F
Bank Sta=4948.9,5056
XS Rating Curve= 0 ,0
Exp/Cntr=0.5,0.3

Type RM Length L Ch R = 1 ,69017.4 ,172.3,218.8,299.7
BEGIN DESCRIPTION:
Cross Section 69017.4
END DESCRIPTION:
XS GIS Cut Line= 6
      3135447.43     13861429.43      3135552.57     13860159.21
      3135484.05     13859885.15      3135474.53     13857571.61
      3135388.85     13856248.22      3135510.86      13851874.4
#Sta/Elev= 30
  2937.6      47  2997.7   43.75  4017.7   42.27  4062.7    42.7  4107.7   47.36
  4170.7   47.67  4242.1   47.15  4337.1   41.13  4954.6   41.91  4959.1   39.73
  4969.4   32.28  4984.9   30.76  5013.1   31.26  5035.5   39.76  5550.8    42.9
    5904   43.77    6174   41.68  6893.4    44.5  6938.4   42.65  7373.4   43.79
  7493.4   42.04  8724.5   42.96  8754.5    44.9  9894.5   41.57 10810.1   42.66
 10890.1   44.55 11345.1   42.85 11535.1   45.39 12100.1   42.97 12510.1   47.31
#Mann= 5 , 1 , 0
  2937.6     .99       0  4170.7      .1       0  4959.1    .035       0
  5035.5      .1       0  5550.8     .99       0
#XS Ineff= 2 , 0
       0    4156    47.7               0
Permanent Ineff=
       F       F
Bank Sta=4959.1,5035.5
XS Rating Curve= 0 ,0
Exp/Cntr=0.5,0.3

Type RM Length L Ch R = 1 ,68798.6 ,25,25,25
BEGIN DESCRIPTION:
Upstream Section of Bridge/Culvert/Weir
END DESCRIPTION:
XS GIS Cut Line= 6
      3135613.22     13861483.19      3135672.76      13860095.2
      3135672.65     13859874.57      3135812.28     13856659.36
      3135698.82     13854562.63      3135673.47     13851964.41
#Sta/Elev= 30
  2908.8    47.5  2908.9   44.51  2968.9   43.08  4028.9   41.65  4058.9   42.23
  4118.9   49.54  4170.7   49.74  4253.9    49.3  4300.1   42.33  4345.1   41.03
  4768.5    41.9  4838.9   38.53    4884   41.47  4959.1   39.74  4969.4   32.29
  4984.9   30.77  5013.1   31.27  5035.5   39.77  5077.5   40.43  5078.9   38.11
  5191.6   41.78  5550.8   43.21 10815.1   42.48 11280.1   44.48 11535.1   42.55
 11630.1   44.81 11790.1   43.05 11880.1   45.71 12120.1   43.22 12435.1   47.52
#Mann= 5 , 1 , 0
  2908.8     .99       0  4170.7      .1       0  4959.1    .035       0
  5035.5      .1       0  5550.8     .99       0
#XS Ineff= 2 , 0
       0    4172    49.6    5046       0   41.06
Permanent Ineff=
       F       F
Bank Sta=4959.1,5035.5
XS Rating Curve= 0 ,0
Exp/Cntr=0.5,0.3

Type RM Length L Ch R = 3 ,68786.1 ,,,
BEGIN DESCRIPTION:
PICK FAIR-FOOT BRIDGE
Structure ID: H00-60
END DESCRIPTION:
Bridge Culvert--1,0,-1,-1, 0
Deck Dist Width WeirC Skew NumUp NumDn MinLoCord MaxHiCord MaxSubmerge Is_Ogee
10,5,2.6,0, 60, 60, , , 0.95, 0, 1,1,,
  2908.8  2908.9  2968.9  3683.9  3713.9  4028.9  4058.9  4118.9  4228.9  4253.9
  4300.1  4345.1  4390.1  4540.7  4768.5  4813.4  4838.9  4843.8    4884 4958.01
  4958.1  5028.5 5036.39  5036.5  5077.5  5078.9  5173.4  5173.5  5191.6  5231.6
  5336.6  5411.6  5441.6  6070.1  6150.1  6209.2  7364.2  7424.2  7638.7  8038.7
  9243.7  9930.1 10200.1 10755.1 10815.1 11015.1 11100.1 11280.1 11360.1 11490.1
 11535.1 11565.1 11630.1 11745.1 11790.1 11880.1 12120.1 12165.1 12365.1 12435.1
    47.5   44.51   43.08   42.33   43.54   41.65   42.23   49.54   49.96    49.3
   42.33   41.03   42.19    42.7   41.91   41.66   41.57      41   41.48   42.92
   42.92   42.78   42.23   42.22    41.2    41.2   41.85   41.85   41.99   42.28
   42.45   42.45   43.24    43.6    42.2   43.13   43.85   42.42   43.79   42.68
   44.26   42.49   44.21   44.01   42.48   44.23   42.73   44.48   42.88   44.18
   42.55   44.58   44.81    44.5   43.05   45.71   43.22   45.11   45.78   47.52
    47.5   44.51   43.08   42.33   43.54   41.65   42.23   49.54   49.96    49.3
   42.33   41.03   42.18   41.58    41.9   41.52   38.53   40.61   41.47   39.76
   41.62   41.48   40.93   39.79   40.43   38.11   39.81   41.39   41.78   40.73
   42.42   41.84   43.23   43.39   42.11   43.13   43.85   42.42   43.79   42.68
   44.26   42.49   44.21   44.01   42.48   44.23   42.73   44.48   42.88   44.18
   42.55   44.58   44.81    44.5   43.05   45.71   43.22   45.11   45.78   47.52
  2908.8  2908.9  2968.9  3683.9  3713.9  4028.9  4058.9  4118.9  4228.9  4253.9
  4300.1  4345.1  4390.1  4540.7  4768.5  4813.4  4838.9  4843.8    4884 4958.01
  4958.1  5028.5 5036.39  5036.5  5077.5  5078.9  5173.4  5173.5  5191.6  5231.6
  5336.6  5411.6  5441.6  6070.1  6150.1  6209.2  7364.2  7424.2  7638.7  8038.7
  9243.7  9930.1 10200.1 10755.1 10815.1 11015.1 11100.1 11280.1 11360.1 11490.1
 11535.1 11565.1 11630.1 11745.1 11790.1 11880.1 12120.1 12165.1 12365.1 12435.1
    47.5   44.51   43.08   42.33   43.54   41.65   42.23   49.54   49.96    49.3
   42.33   41.03   42.19    42.7   41.91   41.66   41.57      41   41.48   42.92
   42.92   42.78   42.23   42.22    41.2    41.2   41.85   41.85   41.99   42.28
   42.45   42.45   43.24    43.6    42.2   43.13   43.85   42.42   43.79   42.68
   44.26   42.49   44.21   44.01   42.48   44.23   42.73   44.48   42.88   44.18
   42.55   44.58   44.81    44.5   43.05   45.71   43.22   45.11   45.78   47.52
    47.4   44.41   42.98   42.23   43.44   41.55   42.13   49.44   49.86    49.2
   42.23   40.93   42.08   41.48    41.8   41.42   38.43   40.51   41.37   39.66
   41.52   41.38   40.83   39.69   40.33   38.01   39.71   41.29   41.68   40.63
   42.32   41.74   43.13   43.29   42.01   43.03   43.75   42.32   43.69   42.58
   44.16   42.39   44.11   43.91   42.38   44.13   42.63   44.38   42.78   44.08
   42.45   44.48   44.71    44.4   42.95   45.61   43.12   45.01   45.68   47.42
Pier Skew, UpSta & Num, DnSta & Num=  ,4969.4, 2 ,4969.4, 2 , 0 , 0 , 0 ,,
       1       1
   31.32    42.6
       1       1
   31.22    42.5
Pier Skew, UpSta & Num, DnSta & Num=  ,5009, 2 ,5009, 2 , 0 , 0 , 0 ,,
       1       1
   30.89   42.52
       1       1
   30.79   42.42
BR Coef= 1 , 1 , 0 ,1.25, 0 ,,,0.8,-1,2,0,
WSPro=,,,, 1 ,,,, 0 ,,,, 0 ,,,,-1 ,-1 ,-1 , 0 , 0 , 0 , 0 , 0
BR U #Sta/Elev= 192
  2908.8    47.5  2908.9   44.51  2968.9   43.08  3283.9   43.12  3293.9   42.65
  3323.9   42.69  3338.9   43.37  3488.9   42.87  3518.9   42.64  3533.9    42.8
  3588.9    42.9  3598.9      43  3683.9   42.33  3713.9   43.54  3908.9   42.78
  3918.9   42.32  4003.9   42.49  4028.9   41.65  4058.9   42.23  4078.9   44.16
  4088.9   45.51  4103.9   48.34  4118.9   49.54  4170.7   49.74  4228.9   49.96
  4253.9    49.3  4270.1   46.88  4285.1    44.1  4300.1   42.33  4345.1   41.03
  4370.7   41.68  4390.1   42.18  4415.7   42.15  4490.1   42.08  4525.1   41.96
  4530.7   41.82  4540.7   41.58  4555.1   41.23  4617.4      42  4647.4   41.37
  4705.7   41.54  4767.4   41.71  4768.4   41.88  4768.5    41.9  4769.9   41.89
    4812   41.53  4813.4   41.52  4813.8   41.47  4837.2   38.73  4838.9   38.53
  4843.5    40.6  4843.8   40.61    4884   41.47  4884.1   41.37  4884.2   41.36
  4886.2   41.13  4887.6    41.1  4944.1   40.03  4950.1   39.91 4958.01   39.76
  4958.1   39.76  4958.2   39.76  4959.1   39.74  4969.4   32.29  4976.2    32.7
  4983.5   31.73  4984.9   30.77  4998.1    31.7    5009   31.98  5013.1   31.27
  5014.5   32.25  5023.2   34.84  5028.5   36.96  5035.5   39.77  5036.2   39.78
  5036.3   39.78 5036.39   39.78  5036.5   39.79  5052.9   40.04  5077.5   40.43
  5078.9   38.11  5080.2   38.14  5121.7   39.11  5125.1   39.19  5173.4   39.81
  5173.5   41.39    5174   41.44  5175.6   41.47  5191.6   41.78  5231.6   40.73
  5290.1   41.67  5336.6   42.42  5345.1   42.35  5355.1   42.28  5365.1    42.2
  5375.1   42.12  5400.1   41.93  5411.6   41.84  5415.1   42.13  5426.6   43.08
  5441.6   43.23  5445.1   43.23  5550.8   43.21  5650.1    43.2  5665.1    43.2
  5731.7   43.19  5816.7    42.7  5846.7   43.16  5861.7   42.58  5998.9   43.51
  6018.9   42.99  6058.9   43.46  6070.1   43.39  6118.9    43.1  6138.9   42.21
  6149.2   42.11  6150.1   42.11  6156.8   42.12  6179.2   42.13  6209.2   43.13
  6489.2   43.34  6854.2   43.56  7364.2   43.85  7409.2   43.02  7424.2   42.42
  7454.2    43.2  7499.2   42.69  7514.2   43.65  7638.7   43.79  7963.7   43.31
  7978.7   43.77  8038.7   42.68  8653.7   43.33  8668.7   42.87  8683.7   43.74
  8713.7   43.03  8728.7   43.95  9243.7   44.26  9625.1   43.33  9720.1   43.68
  9735.1   43.05  9795.1   43.21  9810.1   43.69  9915.1   43.22  9930.1   42.49
  9945.1   42.53  9975.1    43.7 10175.1   43.73 10200.1   44.21 10295.1   43.54
 10360.1   43.91 10590.1   43.31 10665.1   43.83 10710.1   43.69 10755.1   44.01
 10770.1   43.48 10775.1   43.14 10815.1   42.48 10970.1   43.84 10980.1   43.66
 11015.1   44.23 11100.1   42.73 11130.1   43.86 11200.1   43.68 11270.1   44.13
 11280.1   44.48 11310.1   43.89 11325.1   43.06 11360.1   42.88 11490.1   44.18
 11505.1   43.89 11520.1   42.74 11535.1   42.55 11565.1   44.58 11590.1   44.54
 11630.1   44.81 11670.1   44.09 11745.1    44.5 11775.1   43.09 11790.1   43.05
 11820.1   44.61 11880.1   45.71 11990.1   44.04 12005.1   44.32 12075.1   44.03
 12090.1   43.25 12120.1   43.22 12165.1   45.11 12365.1   45.78 12405.1   46.62
 12420.1   47.39 12435.1   47.52
BR U #Mann= 5
  2908.8     .99  4170.7      .1  4959.1    .035  5035.5      .1  5550.8     .99
BR U Banks=4959.1,5035.5
BR D #Sta/Elev= 192
  2908.8    47.4  2908.9   44.41  2968.9   42.98  3283.9   43.02  3293.9   42.55
  3323.9   42.59  3338.9   43.27  3488.9   42.77  3518.9   42.54  3533.9    42.7
  3588.9    42.8  3598.9    42.9  3683.9   42.23  3713.9   43.44  3908.9   42.68
  3918.9   42.22  4003.9   42.39  4028.9   41.55  4058.9   42.13  4078.9   44.06
  4088.9   45.41  4103.9   48.24  4118.9   49.44  4170.7   49.64  4228.9   49.86
  4253.9    49.2  4270.1   46.78  4285.1      44  4300.1   42.23  4345.1   40.93
  4370.7   41.58  4390.1   42.08  4415.7   42.05  4490.1   41.98  4525.1   41.86
  4530.7   41.72  4540.7   41.48  4555.1   41.13  4617.4    41.9  4647.4   41.27
  4705.7   41.44  4767.4   41.61  4768.4   41.78  4768.5    41.8  4769.9   41.79
    4812   41.43  4813.4   41.42  4813.8   41.37  4837.2   38.63  4838.9   38.43
  4843.5    40.5  4843.8   40.51    4884   41.37  4884.1   41.27  4884.2   41.26
  4886.2   41.03  4887.6      41  4944.1   39.93  4950.1   39.81 4958.01   39.66
  4958.1   39.66  4958.2   39.66  4959.1   39.64  4969.4   32.19  4976.2    32.6
  4983.5   31.63  4984.9   30.67  4998.1    31.6    5009   31.88  5013.1   31.17
  5014.5   32.15  5023.2   34.74  5028.5   36.86  5035.5   39.67  5036.2   39.68
  5036.3   39.68 5036.39   39.68  5036.5   39.69  5052.9   39.94  5077.5   40.33
  5078.9   38.01  5080.2   38.04  5121.7   39.01  5125.1   39.09  5173.4   39.71
  5173.5   41.29    5174   41.34  5175.6   41.37  5191.6   41.68  5231.6   40.63
  5290.1   41.57  5336.6   42.32  5345.1   42.25  5355.1   42.18  5365.1    42.1
  5375.1   42.02  5400.1   41.83  5411.6   41.74  5415.1   42.03  5426.6   42.98
  5441.6   43.13  5445.1   43.13  5550.8   43.11  5650.1    43.1  5665.1    43.1
  5731.7   43.09  5816.7    42.6  5846.7   43.06  5861.7   42.48  5998.9   43.41
  6018.9   42.89  6058.9   43.36  6070.1   43.29  6118.9      43  6138.9   42.11
  6149.2   42.01  6150.1   42.01  6156.8   42.02  6179.2   42.03  6209.2   43.03
  6489.2   43.24  6854.2   43.46  7364.2   43.75  7409.2   42.92  7424.2   42.32
  7454.2    43.1  7499.2   42.59  7514.2   43.55  7638.7   43.69  7963.7   43.21
  7978.7   43.67  8038.7   42.58  8653.7   43.23  8668.7   42.77  8683.7   43.64
  8713.7   42.93  8728.7   43.85  9243.7   44.16  9625.1   43.23  9720.1   43.58
  9735.1   42.95  9795.1   43.11  9810.1   43.59  9915.1   43.12  9930.1   42.39
  9945.1   42.43  9975.1    43.6 10175.1   43.63 10200.1   44.11 10295.1   43.44
 10360.1   43.81 10590.1   43.21 10665.1   43.73 10710.1   43.59 10755.1   43.91
 10770.1   43.38 10775.1   43.04 10815.1   42.38 10970.1   43.74 10980.1   43.56
 11015.1   44.13 11100.1   42.63 11130.1   43.76 11200.1   43.58 11270.1   44.03
 11280.1   44.38 11310.1   43.79 11325.1   42.96 11360.1   42.78 11490.1   44.08
 11505.1   43.79 11520.1   42.64 11535.1   42.45 11565.1   44.48 11590.1   44.44
 11630.1   44.71 11670.1   43.99 11745.1    44.4 11775.1   42.99 11790.1   42.95
 11820.1   44.51 11880.1   45.61 11990.1   43.94 12005.1   44.22 12075.1   43.93
 12090.1   43.15 12120.1   43.12 12165.1   45.01 12365.1   45.68 12405.1   46.52
 12420.1   47.29 12435.1   47.42
BR D #Mann= 5
  2908.8     .99  4170.7      .1  4959.1    .035  5035.5      .1  5550.8     .99
BR D Banks=4959.1,5035.5
BC Design=,, 0 ,, 0 ,,,,,,
BC HTab HWMax=49.96
BC Use User HTab Curves=0
BC User HTab FreeFlow(D)= 0

Type RM Length L Ch R = 1 ,68773.6 ,426,426,426
BEGIN DESCRIPTION:
Downstream Section of Bridge/Culvert/Weir
END DESCRIPTION:
XS GIS Cut Line= 6
      3135634.77     13861495.87       3135694.3     13860107.88
      3135694.19     13859887.25      3135833.82     13856672.04
      3135720.36     13854575.31      3135695.02     13851977.08
#Sta/Elev= 30
  2908.8   47.39  2908.9    44.4  2968.9   42.97  4028.9   41.54  4058.9   42.12
  4118.9   49.43  4170.7   49.63  4253.9   49.19  4300.1   42.22  4345.1   40.92
  4768.5   41.79  4838.9   38.42    4884   41.36  4959.1   39.63  4969.4   32.18
  4984.9   30.66  5013.1   31.16  5035.5   39.66  5077.5   40.32  5078.9      38
  5191.6   41.67  5550.8    43.1 10815.1   42.37 11280.1   44.37 11535.1   42.44
 11630.1    44.7 11790.1   42.94 11880.1    45.6 12120.1   43.11 12435.1   47.41
#Mann= 5 , 1 , 0
  2908.8     .99       0  4170.7      .1       0  4959.1    .035       0
  5035.5      .1       0  5550.8     .99       0
#XS Ineff= 2 , 0
       0    4172    49.6    5046       0   41.06
Permanent Ineff=
       F       F
Bank Sta=4959.1,5035.5
XS Rating Curve= 0 ,0
Exp/Cntr=0.5,0.3

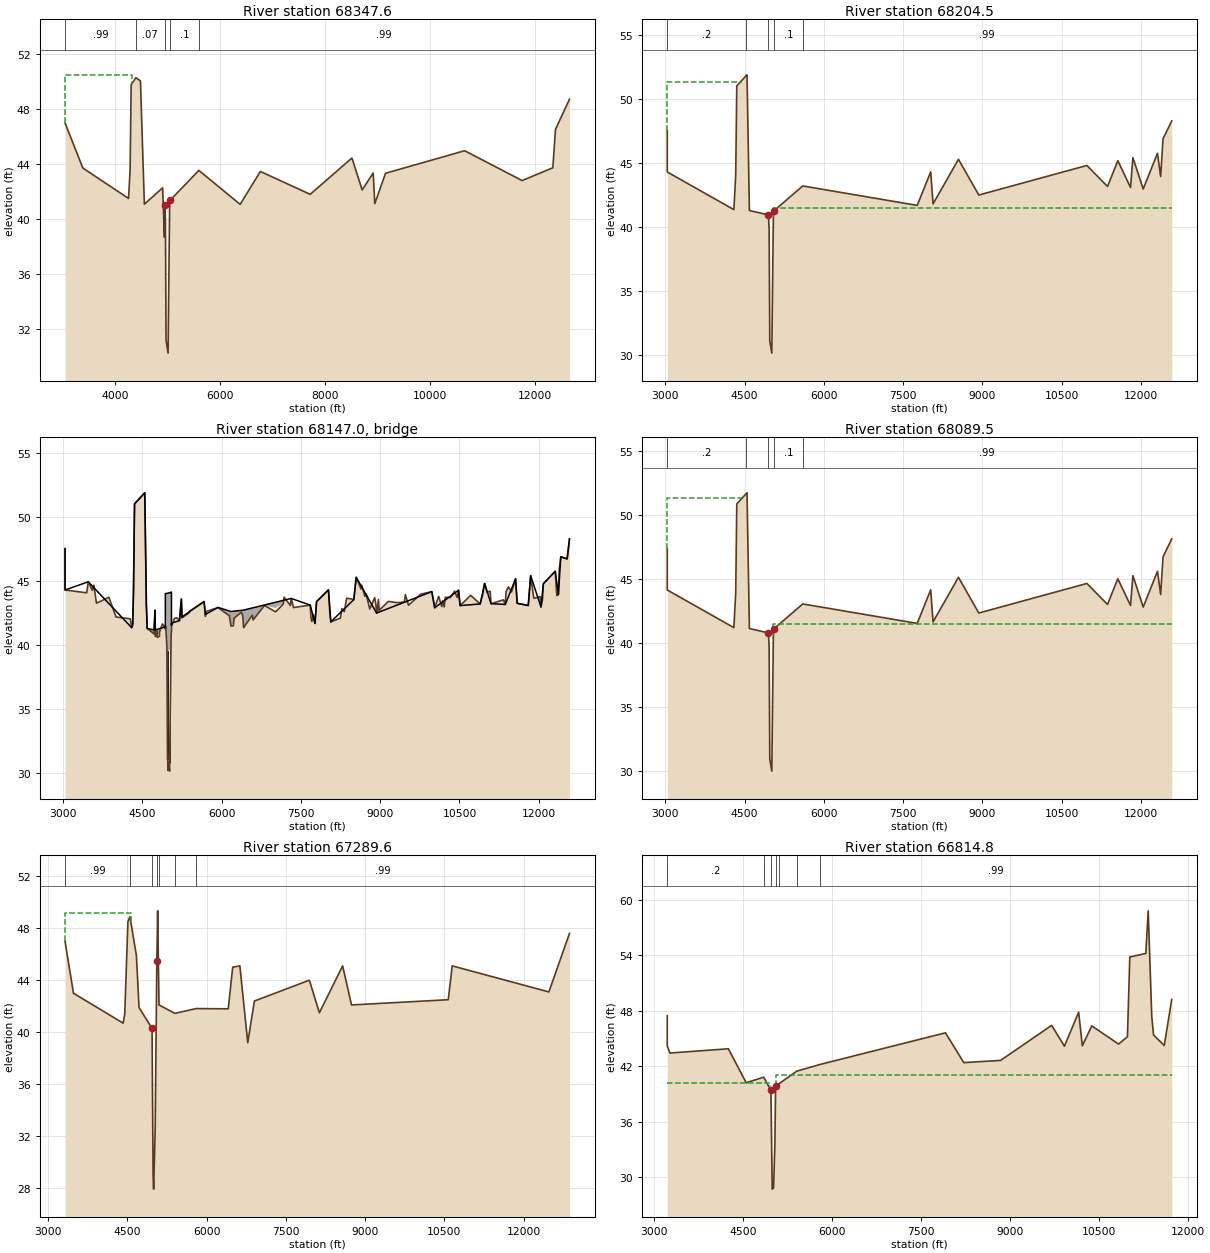
Type RM Length L Ch R = 1 ,68347.6 ,130.8,143.1,141.4
BEGIN DESCRIPTION:
Cross Section 68347.6
END DESCRIPTION:
XS GIS Cut Line= 6
      3135924.64     13861575.08      3135986.85     13860199.59
       3136102.9     13859294.86      3136160.03     13856391.03
       3136007.7     13854144.14      3136083.86     13851982.93
#Sta/Elev= 30
  3052.3      47  3392.4   43.72  4262.4   41.51  4292.4    43.6  4312.4   49.78
    4401   50.29  4489.2   50.06  4564.2   41.09  4911.7   42.28  4946.7   38.69
  4950.8   41.06    4965   39.98    4977   31.21  5015.4   30.26  5044.7   40.78
  5053.3   41.37  5601.2   43.55  6388.6   41.08  6773.6   43.47  7723.6   41.81
    8518   44.45    8713   42.13    8923   43.36    8953   41.13    9158   43.34
   10665   44.98 11760.1   42.81 12345.1   43.74 12395.1   46.53 12662.6   48.73
#Mann= 5 , 1 , 0
  3052.3     .99       0    4401     .07       0  4950.8     .04       0
  5053.3      .1       0  5601.2     .99       0
#XS Ineff= 2 , 0
       0    4326    50.5               0
Permanent Ineff=
       F       F
Bank Sta=4950.8,5053.3
XS Rating Curve= 0 ,0
Exp/Cntr=0.5,0.3

Type RM Length L Ch R = 1 ,68204.5 ,115,115,115
BEGIN DESCRIPTION:
Upstream Section of Bridge/Culvert/Weir
END DESCRIPTION:
XS GIS Cut Line= 6
      3136071.11     13861634.54      3136120.56     13860174.19
       3136177.9     13860015.44      3136213.33     13859615.15
      3136271.96     13858349.07      3136221.68     13852105.19
#Sta/Elev= 30
  3037.9   47.51    3038   44.28    4298   41.34    4333   44.06    4353   51.01
    4521   51.76  4546.7   51.87  4591.7   41.27  4950.8   40.93    4965   39.85
    4977   31.08  5015.4   30.13  5044.7   40.65  5053.3   41.24  5601.2   43.19
  7766.4   41.67  8021.4   44.29  8066.4   41.79  8546.4   45.27  8931.4   42.48
 10976.4   44.79 11366.4   43.15 11561.4   45.16 11801.4   43.07 11846.4    45.4
 12041.4   42.95 12311.4   45.74 12371.4   43.93 12416.4   46.87 12581.4   48.27
#Mann= 5 , 1 , 0
  3037.9      .2       0    4521     .07       0  4950.8     .04       0
  5053.3      .1       0  5601.2     .99       0
#XS Ineff= 2 , 0
       0    4450   51.34    5046       0    41.5
Permanent Ineff=
       F       F
Bank Sta=4950.8,5053.3
XS Rating Curve= 0 ,0
Exp/Cntr=0.5,0.3

Type RM Length L Ch R = 3 ,68147.0 ,,,
BEGIN DESCRIPTION:
LOCKWOOD ROAD
Structure ID: H00-59
END DESCRIPTION:
Bridge Culvert--1,0,-1,-1, 0
Deck Dist Width WeirC Skew NumUp NumDn MinLoCord MaxHiCord MaxSubmerge Is_Ogee
10,95,2.6,0, 60, 60, , , 0.95, 0, 1,1,,
  3037.9    3038    3478    4298    4318    4333    4353  4546.7  4576.7  4591.7
  4722.1  4741.2  4746.1 4935.39  4935.5    4937    4977 5036.29  5036.4  5044.7
  5051.9 5052.01  5054.6  5202.9  5239.5  5249.8  5668.6  5693.6    5932    6177
  6376.4  6416.4  7316.4  7676.4  7766.4  7796.4  8021.4  8066.4  8501.4  8546.4
  8931.4  9976.4 10031.4 10481.4 10511.4 10891.4 10976.4 11096.4 11366.4 11561.4
 11591.4 11801.4 11846.4 12041.4 12086.4 12311.4 12371.4 12416.4 12536.4 12581.4
    47.5   44.27   44.91   41.33   41.54   44.05      51   51.86   43.17   41.26
   41.16   42.69   41.15   41.39   43.99   43.99   44.01   44.08   44.08    44.1
   44.11   41.51   41.68   41.88   43.57   42.16   43.37   42.36   42.91   42.59
   42.68    42.7   43.61   43.09   41.66   43.36   44.28   41.78   43.52   45.26
   42.47   44.14   42.88   44.25   43.05   43.18   44.78    43.2   43.14   45.15
   43.23   43.06   45.39   42.94   44.76   45.73   43.92   46.86    46.7   48.26
    47.5   44.27   44.91   41.33   41.54   44.05      51   51.86   43.17   41.26
   40.84   42.68   40.64   41.32   41.32   41.47   39.51   39.58    37.5   40.64
   41.13   41.14   41.67   41.87   43.56   42.09   43.36   42.21    42.9   41.46
   42.54   41.33   43.61   43.09   41.66   43.36   44.28   41.78   43.52   45.26
   42.47   44.14   42.88   44.25   43.05   43.18   44.78    43.2   43.14   45.15
   43.23   43.06   45.39   42.94   44.76   45.73   43.92   46.86    46.7   48.26
  3037.9    3038    3478    4298    4318    4333    4353  4546.7  4576.7  4591.7
  4722.1  4741.2  4746.1 4935.39  4935.5    4937    4977 5036.29  5036.4  5044.7
  5051.9 5052.01  5054.6  5202.9  5239.5  5249.8  5668.6  5693.6    5932    6177
  6376.4  6416.4  7316.4  7676.4  7766.4  7796.4  8021.4  8066.4  8501.4  8546.4
  8931.4  9976.4 10031.4 10481.4 10511.4 10891.4 10976.4 11096.4 11366.4 11561.4
 11591.4 11801.4 11846.4 12041.4 12086.4 12311.4 12371.4 12416.4 12536.4 12581.4
    47.5   44.27   44.91   41.33   41.54   44.05      51   51.86   43.17   41.26
   41.16   42.69   41.15   41.39   43.99   43.99   44.01   44.08   44.08    44.1
   44.11   41.51   41.68   41.88   43.57   42.16   43.37   42.36   42.91   42.59
   42.68    42.7   43.61   43.09   41.66   43.36   44.28   41.78   43.52   45.26
   42.47   44.14   42.88   44.25   43.05   43.18   44.78    43.2   43.14   45.15
   43.23   43.06   45.39   42.94   44.76   45.73   43.92   46.86    46.7   48.26
    47.4   44.17   44.81   41.23   41.44   43.95    50.9   51.76   43.07   41.16
   40.74   42.58   40.54   41.22   41.22   41.37   39.41   39.48    37.4   40.54
   41.03   41.04   41.57   41.77   43.46   41.99   43.26   42.11    42.8   41.36
   42.44   41.23   43.51   42.99   41.56   43.26   44.18   41.68   43.42   45.16
   42.37   44.04   42.78   44.15   42.95   43.08   44.68    43.1   43.04   45.05
   43.13   42.96   45.29   42.84   44.66   45.63   43.82   46.76    46.6   48.16
Pier Skew, UpSta & Num, DnSta & Num=  ,4977, 2 ,4977, 2 , 0 , 0 , 0 ,,
     1.4     1.4
   30.05   40.53
     1.4     1.4
   29.95   40.43
Pier Skew, UpSta & Num, DnSta & Num=  ,5016.8, 2 ,5016.8, 2 , 0 , 0 , 0 ,,
     1.4     1.4
   29.46   40.56
     1.4     1.4
   29.36   40.46
BR Coef= 1 , 1 , 0 ,1.25, 0 ,,,0.8,0,2,0,
WSPro=,,,, 1 ,,,, 0 ,,,, 0 ,,,,-1 ,-1 ,-1 , 0 , 0 , 0 , 0 , 0
BR U #Sta/Elev= 173
  3037.9    47.5    3038   44.27    3448   44.05    3478   44.91    3553   44.25
    3583   44.65    3633   43.24    3868    43.7    4003   42.16    4273   42.02
    4298   41.33    4318   41.54    4333   44.05    4353      51    4521   51.75
  4546.7   51.86  4556.7   48.99  4566.7   45.83  4576.7   43.17  4591.7   41.26
    4621   41.17  4722.1   40.84  4741.2   42.68  4741.6   42.44  4743.7   41.15
  4746.1   40.64  4780.8   41.06  4781.9   41.07    4783   40.56  4823.9   40.66
  4824.6   40.66  4824.8   40.97  4876.1   41.58  4879.6   41.62 4935.39   41.32
  4935.5   41.32 4935.61   41.32  4935.7   41.32  4936.8   41.22  4936.9   41.36
    4937   41.47  4950.8   40.92  4956.4   40.49 4956.51   40.49  4956.6   40.48
  4956.7   40.47    4965   39.84    4977   31.07  4982.4   30.92  4984.6   30.18
  5000.4    30.8  5015.4   30.12  5016.8   30.79  5017.5   31.03  5030.6    35.3
  5036.2   37.42 5036.29   37.45  5036.4    37.5  5036.5   37.53  5044.7   40.64
 5051.79   41.13  5051.9   41.13 5052.01   41.14  5053.3   41.23  5054.6   41.67
  5054.7   41.58  5056.7   41.56  5107.5   42.04  5108.3   42.05    5153    42.1
  5153.3    42.1  5202.7   41.87  5202.9   41.87  5239.5   43.56  5249.4   42.15
  5249.8   42.09  5390.1    42.5  5393.6   42.61  5601.2   43.18  5668.6   43.36
  5693.6   42.21  5713.6   42.59    5932    42.9    6147   42.25    6177   41.46
    6222   41.47    6237   42.07  6376.4   42.54  6401.4   42.21  6416.4   41.33
  6424.2   41.38  6581.4    42.3  6596.4   41.93  6811.4   43.06  7021.4   42.56
  7166.4   43.17  7181.4   43.71  7301.4   43.06  7316.4   43.61  7361.4    42.9
  7676.4   43.09  7691.4   42.11  7706.4   41.81  7736.4   42.33  7766.4   41.66
  7796.4   43.36  8021.4   44.28  8051.4   42.28  8066.4   41.78  8246.4   42.07
  8276.4   42.82  8321.4   42.58  8366.4   43.64  8501.4   43.52  8546.4   45.26
  8636.4   44.35  8651.4   44.64  8711.4   43.77  8736.4   43.96  8801.4   42.79
  8896.4   43.67  8921.4   43.08  8931.4   42.47  8941.4   42.47  8966.4   43.53
  8981.4   42.68  9156.4   43.38  9321.4   43.28  9456.4   43.33  9476.4   43.91
  9536.4   43.08  9766.4   43.94  9976.4   44.14 10031.4   42.88 10106.4   43.77
 10166.4   42.97 10181.4   43.43 10211.4   42.95 10231.4    43.7 10331.4   43.68
 10406.4   44.18 10456.4   43.68 10481.4   44.25 10511.4   43.05 10711.4   43.85
 10891.4   43.18 10946.4   44.05 10961.4   44.57 10976.4   44.78 11021.4   44.08
 11081.4   44.18 11096.4    43.2 11331.4    43.5 11366.4   43.14 11381.4   44.14
 11426.4   44.51 11486.4   44.12 11561.4   45.15 11591.4   43.23 11801.4   43.06
 11846.4   45.39 11906.4   43.62 12026.4   43.75 12041.4   42.94 12071.4    43.5
 12086.4   44.76 12311.4   45.73 12341.4   43.83 12371.4   43.92 12386.4   45.83
 12416.4   46.86 12536.4    46.7 12581.4   48.26
BR U #Mann= 5
  3037.9      .2    4521     .07  4950.8     .04  5053.3      .1  5601.2     .99
BR U Banks=4950.8,5053.3
BR D #Sta/Elev= 173
  3037.9    47.4    3038   44.17    3448   43.95    3478   44.81    3553   44.15
    3583   44.55    3633   43.14    3868    43.6    4003   42.06    4273   41.92
    4298   41.23    4318   41.44    4333   43.95    4353    50.9    4521   51.65
  4546.7   51.76  4556.7   48.89  4566.7   45.73  4576.7   43.07  4591.7   41.16
    4621   41.07  4722.1   40.74  4741.2   42.58  4741.6   42.34  4743.7   41.05
  4746.1   40.54  4780.8   40.96  4781.9   40.97    4783   40.46  4823.9   40.56
  4824.6   40.56  4824.8   40.87  4876.1   41.48  4879.6   41.52 4935.39   41.22
  4935.5   41.22 4935.61   41.22  4935.7   41.22  4936.8   41.12  4936.9   41.26
    4937   41.37  4950.8   40.82  4956.4   40.39 4956.51   40.39  4956.6   40.38
  4956.7   40.37    4965   39.74    4977   30.97  4982.4   30.82  4984.6   30.08
  5000.4    30.7  5015.4   30.02  5016.8   30.69  5017.5   30.93  5030.6    35.2
  5036.2   37.32 5036.29   37.35  5036.4    37.4  5036.5   37.43  5044.7   40.54
 5051.79   41.03  5051.9   41.03 5052.01   41.04  5053.3   41.13  5054.6   41.57
  5054.7   41.48  5056.7   41.46  5107.5   41.94  5108.3   41.95    5153      42
  5153.3      42  5202.7   41.77  5202.9   41.77  5239.5   43.46  5249.4   42.05
  5249.8   41.99  5390.1    42.4  5393.6   42.51  5601.2   43.08  5668.6   43.26
  5693.6   42.11  5713.6   42.49    5932    42.8    6147   42.15    6177   41.36
    6222   41.37    6237   41.97  6376.4   42.44  6401.4   42.11  6416.4   41.23
  6424.2   41.28  6581.4    42.2  6596.4   41.83  6811.4   42.96  7021.4   42.46
  7166.4   43.07  7181.4   43.61  7301.4   42.96  7316.4   43.51  7361.4    42.8
  7676.4   42.99  7691.4   42.01  7706.4   41.71  7736.4   42.23  7766.4   41.56
  7796.4   43.26  8021.4   44.18  8051.4   42.18  8066.4   41.68  8246.4   41.97
  8276.4   42.72  8321.4   42.48  8366.4   43.54  8501.4   43.42  8546.4   45.16
  8636.4   44.25  8651.4   44.54  8711.4   43.67  8736.4   43.86  8801.4   42.69
  8896.4   43.57  8921.4   42.98  8931.4   42.37  8941.4   42.37  8966.4   43.43
  8981.4   42.58  9156.4   43.28  9321.4   43.18  9456.4   43.23  9476.4   43.81
  9536.4   42.98  9766.4   43.84  9976.4   44.04 10031.4   42.78 10106.4   43.67
 10166.4   42.87 10181.4   43.33 10211.4   42.85 10231.4    43.6 10331.4   43.58
 10406.4   44.08 10456.4   43.58 10481.4   44.15 10511.4   42.95 10711.4   43.75
 10891.4   43.08 10946.4   43.95 10961.4   44.47 10976.4   44.68 11021.4   43.98
 11081.4   44.08 11096.4    43.1 11331.4    43.4 11366.4   43.04 11381.4   44.04
 11426.4   44.41 11486.4   44.02 11561.4   45.05 11591.4   43.13 11801.4   42.96
 11846.4   45.29 11906.4   43.52 12026.4   43.65 12041.4   42.84 12071.4    43.4
 12086.4   44.66 12311.4   45.63 12341.4   43.73 12371.4   43.82 12386.4   45.73
 12416.4   46.76 12536.4    46.6 12581.4   48.16
BR D #Mann= 5
  3037.9      .2    4521     .07  4950.8     .04  5053.3      .1  5601.2     .99
BR D Banks=4950.8,5053.3
BC Design=,, 0 ,, 0 ,,,,,,
BC HTab HWMax=51.87
BC Use User HTab Curves=0
BC User HTab FreeFlow(D)= 0

Type RM Length L Ch R = 1 ,68089.5 ,799.9,799.9,799.9
BEGIN DESCRIPTION:
Downstream Section of Bridge/Culvert/Weir
END DESCRIPTION:
XS GIS Cut Line= 6
      3136185.44     13861646.89       3136234.9     13860186.53
      3136292.24     13860027.78      3136327.67     13859627.49
       3136386.3     13858361.41      3136336.02     13852117.53
#Sta/Elev= 30
  3037.9   47.37    3038   44.14    4298    41.2    4333   43.92    4353   50.87
    4521   51.62  4546.7   51.73  4591.7   41.13  4950.8   40.79    4965   39.71
    4977   30.94  5015.4   29.99  5044.7   40.51  5053.3    41.1  5601.2   43.05
  7766.4   41.53  8021.4   44.15  8066.4   41.65  8546.4   45.13  8931.4   42.34
 10976.4   44.65 11366.4   43.01 11561.4   45.02 11801.4   42.93 11846.4   45.26
 12041.4   42.81 12311.4    45.6 12371.4   43.79 12416.4   46.73 12581.4   48.13
#Mann= 5 , 1 , 0
  3037.9      .2       0    4521     .07       0  4950.8     .04       0
  5053.3      .1       0  5601.2     .99       0
#XS Ineff= 2 , 0
       0    4450   51.34    5046       0    41.5
Permanent Ineff=
       F       F
Bank Sta=4950.8,5053.3
XS Rating Curve= 0 ,0
Exp/Cntr=0.5,0.3

Type RM Length L Ch R = 1 ,67289.6 ,293.6,474.8,1991.7
BEGIN DESCRIPTION:
Cross Section 67289.6
END DESCRIPTION:
XS GIS Cut Line= 6
      3136735.62      13861502.2      3136894.19     13860261.73
      3137107.37     13859747.44      3136474.55     13858425.96
      3136642.06     13856490.28      3136532.33     13852208.21
#Sta/Elev= 30
  3321.9      47    3482      43    4422    40.7    4452    41.4    4512    48.5
  4550.4   48.88  4672.5    45.9  4722.5    41.9  4968.7   40.29  4988.5   29.02
  4998.5   27.95  5028.7   32.66    5059   45.48  5074.5   49.33  5100.4    42.1
  5400.4   41.45  5800.4   41.82  6409.9    41.8  6494.9      45  6629.9    45.1
  6779.6    39.2  6904.6    42.4  7944.6      44  8134.6    41.5  8574.6    45.1
  8742.5    42.1 10572.5    42.5 10647.5    45.1 12476.6    43.1 12866.6    47.6
#Mann= 7 , 1 , 0
  3321.9     .99       0  4550.4     .07       0  4968.7    .035       0
    5059     .07       0  5100.4      .1       0  5400.4      .2       0
  5800.4     .99       0
#XS Ineff= 2 , 0
       0  4572.5   49.13               0
Permanent Ineff=
       F       F
Bank Sta=4968.7,5059
XS Rating Curve= 0 ,0
Exp/Cntr=0.5,0.3

Type RM Length L Ch R = 1 ,66814.8 ,24,24,24
BEGIN DESCRIPTION:
Upstream Section of Bridge/Culvert/Weir
END DESCRIPTION:
XS GIS Cut Line= 6
      3137522.65     13861772.33      3137534.89     13860137.53
      3137566.98     13859411.19      3138424.87     13858385.75
      3139802.16     13855784.72       3140186.1     13853968.02
#Sta/Elev= 30
  3220.1   47.48  3220.2   44.19  3265.2   43.43  4250.2   43.89  4550.2   40.21
  4845.1   40.81    4967    39.4  4988.6   28.68  5011.4    28.8  5034.3   33.59
  5045.8   39.84  5400.3   41.46  5800.1    42.2  7907.8   45.62  8217.8   42.39
  8837.8   42.63  9697.8   46.43  9912.8   44.17 10152.8   47.85 10214.7   44.22
 10374.7   46.37 10824.7    44.4 10974.7   45.19 11014.7   53.84 11284.7   54.22
 11324.7   58.84 11384.7   47.39 11414.7   45.39 11594.7   44.24 11721.6   49.23
#Mann= 7 , 1 , 0
  3220.1      .2       0  4845.1     .07       0    4967    .035       0
  5045.8     .07       0  5095.1      .1       0  5400.3      .2       0
  5800.1     .99       0
#XS Ineff= 2 , 0
       0    4957   40.23  5055.8       0    41.1
Permanent Ineff=
       F       F
Bank Sta=4967,5045.8
XS Rating Curve= 0 ,0
Exp/Cntr=0.5,0.3