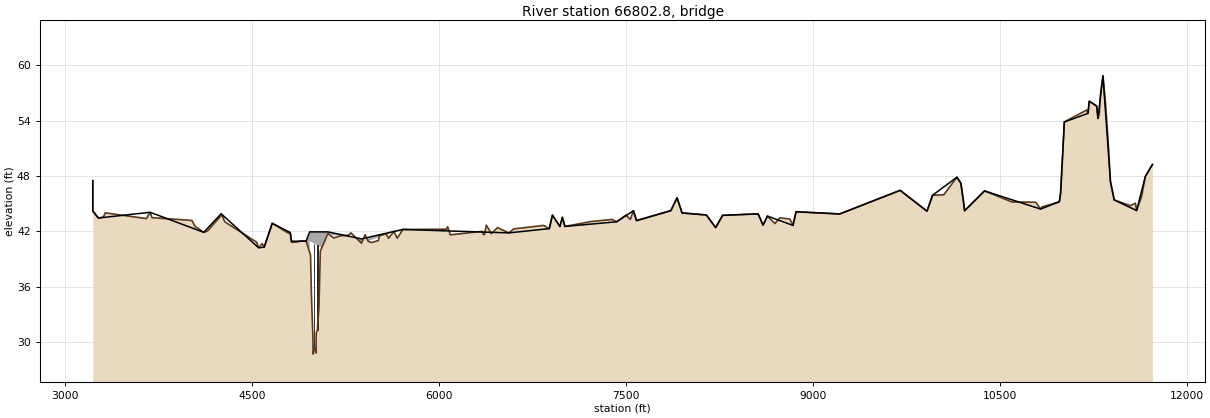
HEC-RAS study H100-00-00.prj: H100-00-00

--- H100-00-00.g01 (geometry) --- (continued)

Type RM Length L Ch R = 3 ,66802.8 ,,,
BEGIN DESCRIPTION:
HICKMAN STREET
Structure ID: H00-57
END DESCRIPTION:
Bridge Culvert--1,0,-1,-1, 0
Deck Dist Width WeirC Skew NumUp NumDn MinLoCord MaxHiCord MaxSubmerge Is_Ogee
10,4,2.6,0, 60, 60, , , 0.95, 0, 1,1,,
  3220.1  3220.2  3265.2  3680.2  4110.2  4250.2  4550.2  4595.2  4660.2  4803.9
  4814.8  4931.9 4960.11  4960.2  5057.4  5106.2  5375.6  5707.8  6557.8  6882.8
  6907.8  6967.8  6987.8  7007.8  7422.8  7557.8  7582.8  7857.8  7907.8  7947.8
  8142.8  8217.8  8272.8  8557.8  8597.8  8632.8  8837.8  8862.8  9212.8  9697.8
  9912.8  9957.8 10152.8 10184.7 10214.7 10374.7 10824.7 10974.7 10984.7 11014.7
 11204.7 11214.7 11274.7 11284.7 11324.7 11384.7 11414.7 11594.7 11664.7 11721.6
    47.5   44.21   43.45   44.07    41.9   43.91   40.23   40.29   42.88   41.88
   40.93   40.95   41.95   41.95   41.95   41.95   41.19   42.21   41.84    42.3
   43.77   42.53   43.53   42.54   43.04   44.24   43.17   44.25   45.64      44
   43.78   42.41   43.74    43.9   42.68   43.66   42.65   44.13   43.89   46.45
   44.19   45.92   47.87   47.22   44.24   46.39   44.42   45.21   46.12   53.86
   54.79   56.11   55.58   54.24   58.86   47.41   45.41   44.26   47.96   49.25
    47.5   44.21   43.45   44.07    41.9   43.91   40.23   40.29   42.88   41.88
   40.82   40.94   39.72   40.95   40.22   41.76   40.72   42.21   41.84    42.3
   43.77   42.53   43.53   42.54   43.04   44.24   43.17   44.25   45.64      44
   43.78   42.41   43.74    43.9   42.68   43.66   42.65   44.13   43.89   46.45
   44.19   45.92   47.87   47.22   44.24   46.39   44.42   45.21   46.12   53.86
   54.79   56.11   55.58   54.24   58.86   47.41   45.41   44.26   47.96   49.25
  3220.1  3220.2  3265.2  3680.2  4110.2  4250.2  4550.2  4595.2  4660.2  4803.9
  4814.8  4931.9 4960.11  4960.2  5057.4  5106.2  5375.6  5707.8  6557.8  6882.8
  6907.8  6967.8  6987.8  7007.8  7422.8  7557.8  7582.8  7857.8  7907.8  7947.8
  8142.8  8217.8  8272.8  8557.8  8597.8  8632.8  8837.8  8862.8  9212.8  9697.8
  9912.8  9957.8 10152.8 10184.7 10214.7 10374.7 10824.7 10974.7 10984.7 11014.7
 11204.7 11214.7 11274.7 11284.7 11324.7 11384.7 11414.7 11594.7 11664.7 11721.6
    47.5   44.21   43.45   44.07    41.9   43.91   40.23   40.29   42.88   41.88
   40.93   40.95   41.95   41.95   41.95   41.95   41.19   42.21   41.84    42.3
   43.77   42.53   43.53   42.54   43.04   44.24   43.17   44.25   45.64      44
   43.78   42.41   43.74    43.9   42.68   43.66   42.65   44.13   43.89   46.45
   44.19   45.92   47.87   47.22   44.24   46.39   44.42   45.21   46.12   53.86
   54.79   56.11   55.58   54.24   58.86   47.41   45.41   44.26   47.96   49.25
    47.4   44.11   43.35   43.97    41.8   43.81   40.13   40.19   42.78   41.78
   40.72   40.84   39.62   40.85   40.12   41.66   40.62   42.11   41.74    42.2
   43.67   42.43   43.43   42.44   42.94   44.14   43.07   44.15   45.54    43.9
   43.68   42.31   43.64    43.8   42.58   43.56   42.55   44.03   43.79   46.35
   44.09   45.82   47.77   47.12   44.14   46.29   44.32   45.11   46.02   53.76
   54.69   56.01   55.48   54.14   58.76   47.31   45.31   44.16   47.86   49.15
Pier Skew, UpSta & Num, DnSta & Num=  ,4995.7, 2 ,4995.7, 2 , 0 , 0 , 0 ,,
       1       1
   28.34   41.95
       1       1
   28.24   41.85
Pier Skew, UpSta & Num, DnSta & Num=  ,5023.1, 2 ,5023.1, 2 , 0 , 0 , 0 ,,
       1       1
   30.33   41.95
       1       1
   30.23   41.85
Abutment Skew #Up #Dn= , 2 , 2
    4960  4983.3
   40.95    31.5
    4960  4983.3
   40.85    31.4
Abutment Skew #Up #Dn= , 2 , 2
  5023.3 5057.49
   31.73   40.95
  5023.3 5057.49
   31.63   40.85
BR Coef= 1 , 1 , 0 ,1.25, 0 ,,,0.8,0,2,0,
WSPro=,,,, 1 ,,,, 0 ,,,, 0 ,,,,-1 ,-1 ,-1 , 0 , 0 , 0 , 0 , 0
BR U #Sta/Elev= 165
  3220.1    47.5  3220.2   44.21  3265.2   43.45  3305.2   43.56  3320.2   44.01
  3650.2   43.39  3680.2   44.07  3695.2   43.49  4015.2   43.19  4040.2   42.56
  4110.2    41.9  4140.2   42.04  4245.2   43.64  4250.2   43.91  4280.2   43.03
  4535.2   40.83  4550.2   40.23  4580.2   40.68  4595.2   40.29  4660.2   42.88
  4790.2    41.8  4803.9   41.88  4813.1   40.99  4814.8   40.82  4845.1   40.83
  4855.4   40.84  4857.3   40.85  4890.3   40.97    4891   40.97  4931.9   40.94
  4932.6   40.91 4959.49   39.75  4959.6   39.74 4959.81   39.73    4960   39.72
 4960.11   39.72  4960.2   39.71    4967   39.42  4974.7   34.96  4983.2   31.53
  4983.3    31.5  4987.1    30.2  4988.6    28.7  4995.7   29.39  5001.3   29.42
  5011.4   28.82  5012.8      31  5023.1   31.35  5023.2   31.54  5023.3   31.73
  5034.3   33.61  5045.8   39.86 5057.29   40.22  5057.4   40.22  5057.5   40.23
 5058.09   40.25  5058.2   40.25 5058.31   40.25  5106.2   41.76  5106.3   41.76
  5154.3   41.29  5155.9    41.3  5211.3   41.53  5212.6   41.53  5268.4   41.57
  5268.7   41.57  5272.3   41.62  5287.3   41.79  5291.5   41.84  5302.3    41.7
  5312.3   41.56  5347.3    41.1  5375.6   40.72  5387.3   41.08  5393.8   41.28
  5400.3   41.48  5405.6   41.64  5430.6   40.92  5456.1   40.79  5483.8    40.9
  5511.1   41.01  5517.3   41.34  5521.1   41.54  5571.1   41.73  5582.8   41.52
  5592.8   41.26  5637.8      42  5662.8   41.26  5707.8   42.21  5800.1   42.22
  6057.8   42.24  6067.8    42.5  6087.8   41.63  6342.8      42  6357.8   41.62
  6362.8    41.7  6377.8   42.67  6417.8   41.76  6467.8   42.41  6557.8   41.84
  6597.8   42.27  6837.8   42.65  6882.8    42.3  6907.8   43.77  6967.8   42.53
  6987.8   43.53  7007.8   42.54  7217.8   43.07  7387.8    43.3  7422.8   43.04
  7497.8   43.77  7532.8    43.3  7557.8   44.24  7582.8   43.17  7857.8   44.25
  7907.8   45.64  7947.8      44  8142.8   43.78  8217.8   42.41  8272.8   43.74
  8557.8    43.9  8597.8   42.68  8632.8   43.66  8692.8   42.85  8732.8   43.47
  8812.8   43.34  8837.8   42.65  8862.8   44.13  9212.8   43.89  9697.8   46.45
  9912.8   44.19  9957.8   45.92 10047.8   45.97 10152.8   47.87 10154.7   47.85
 10184.7   47.22 10204.7   45.46 10214.7   44.24 10374.7   46.39 10594.7   45.19
 10784.7   45.16 10824.7   44.42 10834.7   44.65 10974.7   45.21 10984.7   46.12
 11004.7   51.04 11014.7   53.86 11194.7   55.16 11204.7   54.79 11214.7   56.11
 11274.7   55.58 11284.7   54.24 11294.7   54.69 11304.7   56.89 11324.7   58.86
 11344.7   55.95 11364.7   52.09 11384.7   47.41 11414.7   45.41 11544.7   44.79
 11584.7   45.06 11594.7   44.26 11634.7   45.79 11664.7   47.96 11721.6   49.25
BR U #Mann= 7
  3220.1      .2  4845.1     .07    4967    .035  5045.8     .07  5095.1      .1
  5400.3      .2  5800.1     .99
BR U Banks=4967,5045.8
BR D #Sta/Elev= 165
  3220.1    47.4  3220.2   44.11  3265.2   43.35  3305.2   43.46  3320.2   43.91
  3650.2   43.29  3680.2   43.97  3695.2   43.39  4015.2   43.09  4040.2   42.46
  4110.2    41.8  4140.2   41.94  4245.2   43.54  4250.2   43.81  4280.2   42.93
  4535.2   40.73  4550.2   40.13  4580.2   40.58  4595.2   40.19  4660.2   42.78
  4790.2    41.7  4803.9   41.78  4813.1   40.89  4814.8   40.72  4845.1   40.73
  4855.4   40.74  4857.3   40.75  4890.3   40.87    4891   40.87  4931.9   40.84
  4932.6   40.81 4959.49   39.65  4959.6   39.64 4959.81   39.63    4960   39.62
 4960.11   39.62  4960.2   39.61    4967   39.32  4974.7   34.86  4983.2   31.43
  4983.3    31.4  4987.1    30.1  4988.6    28.6  4995.7   29.29  5001.3   29.32
  5011.4   28.72  5012.8    30.9  5023.1   31.25  5023.2   31.44  5023.3   31.63
  5034.3   33.51  5045.8   39.76 5057.29   40.12  5057.4   40.12  5057.5   40.13
 5058.09   40.15  5058.2   40.15 5058.31   40.15  5106.2   41.66  5106.3   41.66
  5154.3   41.19  5155.9    41.2  5211.3   41.43  5212.6   41.43  5268.4   41.47
  5268.7   41.47  5272.3   41.52  5287.3   41.69  5291.5   41.74  5302.3    41.6
  5312.3   41.46  5347.3      41  5375.6   40.62  5387.3   40.98  5393.8   41.18
  5400.3   41.38  5405.6   41.54  5430.6   40.82  5456.1   40.69  5483.8    40.8
  5511.1   40.91  5517.3   41.24  5521.1   41.44  5571.1   41.63  5582.8   41.42
  5592.8   41.16  5637.8    41.9  5662.8   41.16  5707.8   42.11  5800.1   42.12
  6057.8   42.14  6067.8    42.4  6087.8   41.53  6342.8    41.9  6357.8   41.52
  6362.8    41.6  6377.8   42.57  6417.8   41.66  6467.8   42.31  6557.8   41.74
  6597.8   42.17  6837.8   42.55  6882.8    42.2  6907.8   43.67  6967.8   42.43
  6987.8   43.43  7007.8   42.44  7217.8   42.97  7387.8    43.2  7422.8   42.94
  7497.8   43.67  7532.8    43.2  7557.8   44.14  7582.8   43.07  7857.8   44.15
  7907.8   45.54  7947.8    43.9  8142.8   43.68  8217.8   42.31  8272.8   43.64
  8557.8    43.8  8597.8   42.58  8632.8   43.56  8692.8   42.75  8732.8   43.37
  8812.8   43.24  8837.8   42.55  8862.8   44.03  9212.8   43.79  9697.8   46.35
  9912.8   44.09  9957.8   45.82 10047.8   45.87 10152.8   47.77 10154.7   47.75
 10184.7   47.12 10204.7   45.36 10214.7   44.14 10374.7   46.29 10594.7   45.09
 10784.7   45.06 10824.7   44.32 10834.7   44.55 10974.7   45.11 10984.7   46.02
 11004.7   50.94 11014.7   53.76 11194.7   55.06 11204.7   54.69 11214.7   56.01
 11274.7   55.48 11284.7   54.14 11294.7   54.59 11304.7   56.79 11324.7   58.76
 11344.7   55.85 11364.7   51.99 11384.7   47.31 11414.7   45.31 11544.7   44.69
 11584.7   44.96 11594.7   44.16 11634.7   45.69 11664.7   47.86 11721.6   49.15
BR D #Mann= 7
  3220.1      .2  4845.1     .07    4967    .035  5045.8     .07  5095.1      .1
  5400.3      .2  5800.1     .99
BR D Banks=4967,5045.8
BC Design=,, 0 ,, 0 ,,,,,,
BC HTab HWMax=58.84
BC Use User HTab Curves=0
BC User HTab FreeFlow(D)= 0