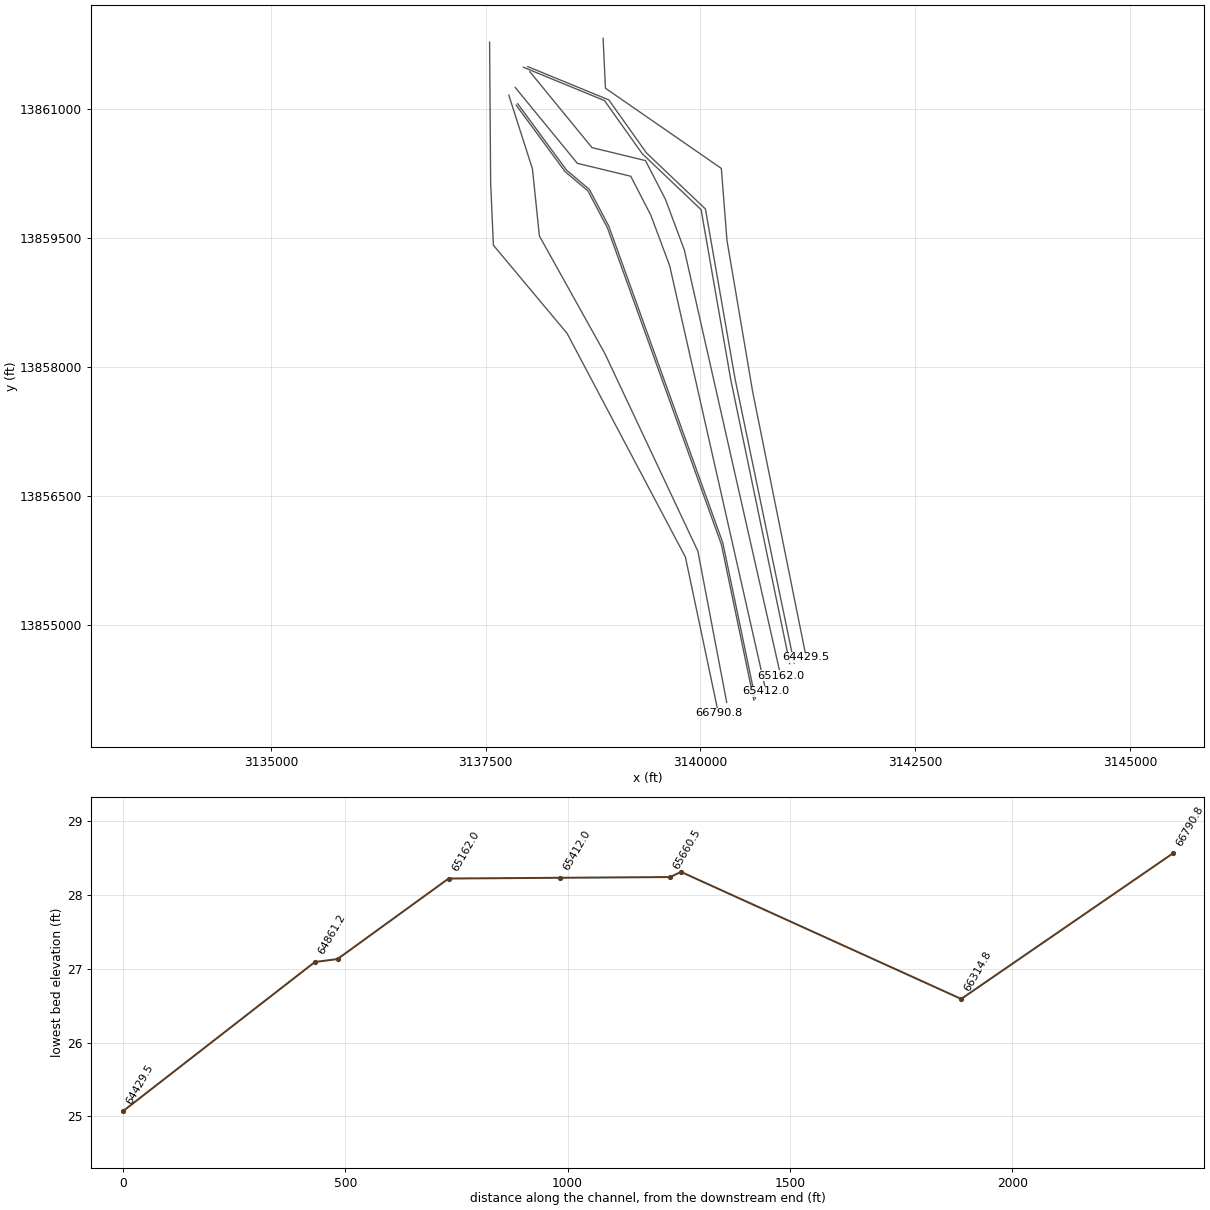
HEC-RAS study H100-00-00.prj: H100-00-00

--- H100-00-00.g01 (geometry) --- (continued)

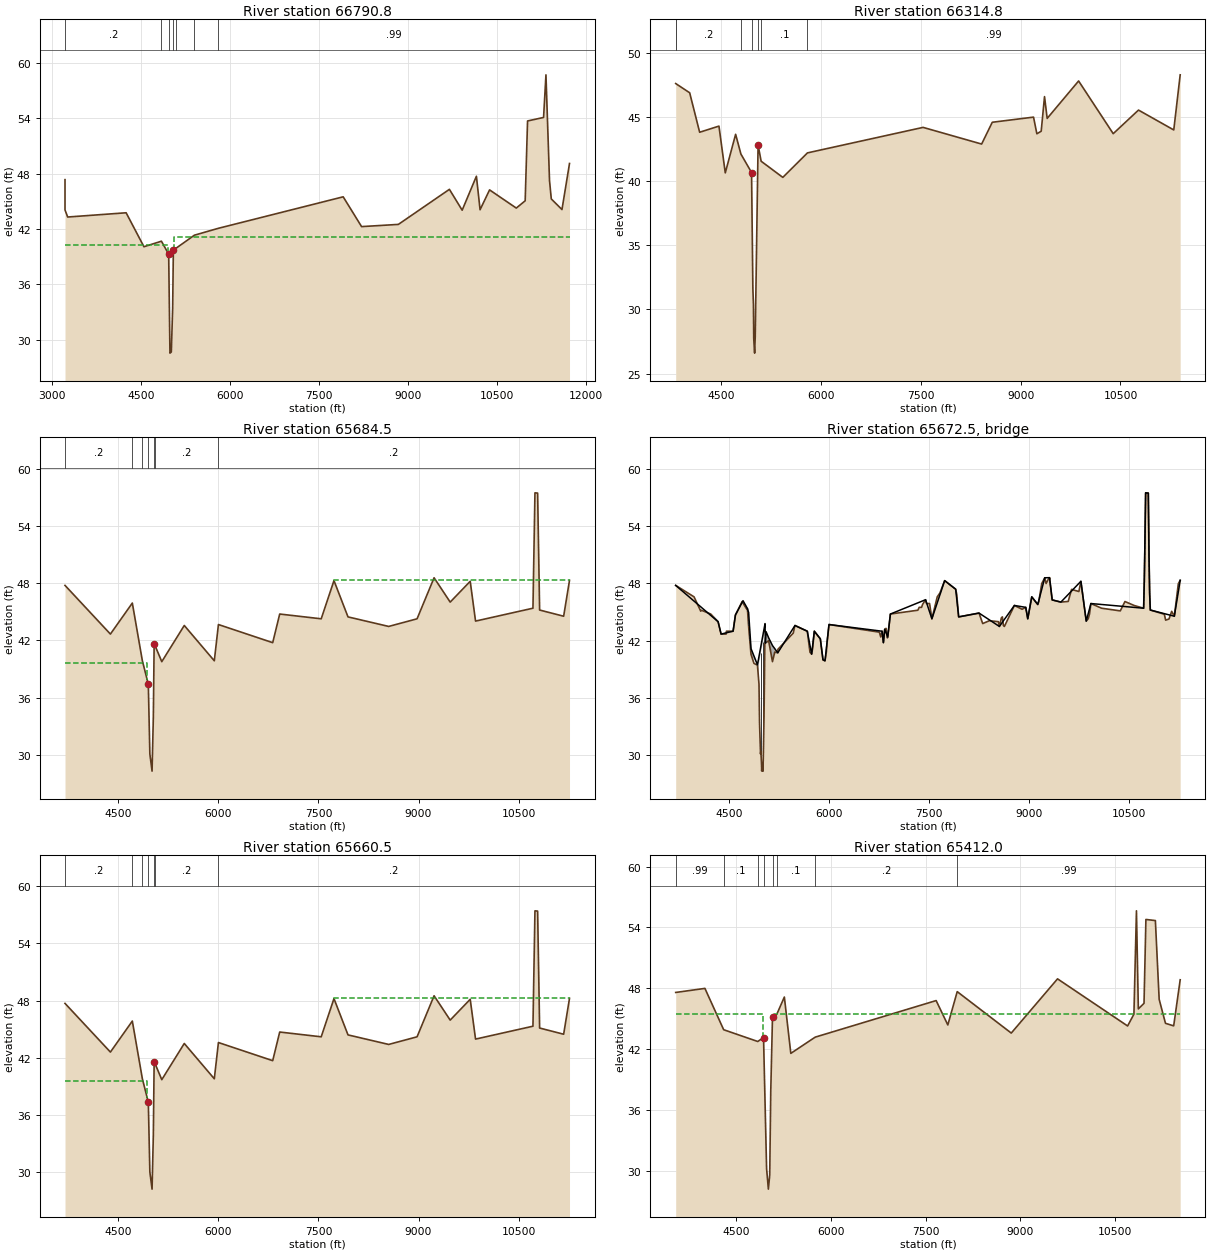
Type RM Length L Ch R = 1 ,66790.8 ,476,476,476
BEGIN DESCRIPTION:
Downstream Section of Bridge/Culvert/Weir
END DESCRIPTION:
XS GIS Cut Line= 6
      3137546.48     13861775.23      3137558.71     13860140.43
       3137590.8     13859414.09      3138448.69     13858388.65
      3139825.98     13855787.62      3140209.92     13853970.91
#Sta/Elev= 30
  3220.1   47.36  3220.2   44.07  3265.2   43.31  4250.2   43.77  4550.2   40.09
  4845.1   40.69    4967   39.28  4988.6   28.56  5011.4   28.68  5034.3   33.47
  5045.8   39.72  5400.3   41.34  5800.1   42.08  7907.8    45.5  8217.8   42.27
  8837.8   42.51  9697.8   46.31  9912.8   44.05 10152.8   47.73 10214.7    44.1
 10374.7   46.25 10824.7   44.28 10974.7   45.07 11014.7   53.72 11284.7    54.1
 11324.7   58.72 11384.7   47.27 11414.7   45.27 11594.7   44.12 11721.6   49.11
#Mann= 7 , 1 , 0
  3220.1      .2       0  4845.1     .07       0    4967    .035       0
  5045.8     .07       0  5095.1      .1       0  5400.3      .2       0
  5800.1     .99       0
#XS Ineff= 2 , 0
       0 4960.33   40.23 5052.47       0    41.1
Permanent Ineff=
       F       F
Bank Sta=4967,5045.8
XS Rating Curve= 0 ,0
Exp/Cntr=0.5,0.3

Type RM Length L Ch R = 1 ,66314.8 ,401.1,630.3,878.8
BEGIN DESCRIPTION:
Cross Section 66314.8
END DESCRIPTION:
XS GIS Cut Line= 6
      3137770.08     13861158.75      3138045.31     13860301.35
      3138125.99     13859521.78      3138888.35     13858154.29
      3139970.87     13855856.73      3140306.03      13854099.4
#Sta/Elev= 30
  3816.1   47.62  4026.1    46.9  4176.1   43.82  4466.1    44.3  4561.1   40.65
  4716.6   43.66  4796.1   42.12    4956   40.68  4975.8   31.65  4984.4   30.38
  4988.9   27.72  5002.1   26.59  5011.2   27.85  5054.1   42.82  5100.1   41.56
  5425.7    40.3  5796.2   42.21  7533.6    44.2  8413.6    42.9  8573.6    44.6
  9193.6      45  9243.6    43.7  9308.6    43.9  9358.6    46.6  9398.6    44.9
  9870.9   47.82 10390.9   43.71 10770.9   45.55 11300.9      44 11397.4    48.3
#Mann= 7 , 1 , 0
  3816.1      .2       0  3816.1      .2       0  4796.1     .07       0
    4956    .035       0  5054.1     .07       0  5100.1      .1       0
  5796.2     .99       0
Bank Sta=4956,5054.1
XS Rating Curve= 0 ,0
Exp/Cntr=0.5,0.3

Type RM Length L Ch R = 1 ,65684.5 ,24,24,24
BEGIN DESCRIPTION:
Upstream Section of Bridge/Culvert/Weir
END DESCRIPTION:
XS GIS Cut Line= 6
      3137856.09     13861042.77      3138425.49      13860269.6
      3138690.89     13860045.79      3138917.42     13859617.68
      3140244.42      13855934.7      3140622.14     13854125.65
#Sta/Elev= 30
  3703.3   47.77  4383.3   42.67  4711.9   45.92  4861.9   39.89  4951.4   37.41
  4974.6    30.1  5007.5   28.31  5026.7   33.97  5038.8   41.68  5153.3   39.78
  5490.2   43.57  5940.2   39.87  6001.9   43.67  6815.2   41.77  6920.2   44.77
    7542   44.27  7733.2   48.27  7943.2   44.47  8553.2   43.47  8978.2   44.27
  9233.2   48.57  9474.5   46.02  9774.5    48.2  9854.5   44.03 10714.5   45.38
 10744.5   57.47 10784.5   57.44 10814.5   45.19 11174.5   44.54 11262.2    48.3
#Mann= 7 , 1 , 0
  3703.3      .2       0  4711.9      .1       0  4861.9     .07       0
  4951.4    .035       0  5038.8      .1       0    5051      .2       0
  6001.9      .2       0
#XS Ineff= 2 , 0
       0    4934    39.6    7735       0    48.3
Permanent Ineff=
       F       F
Bank Sta=4951.4,5038.8
XS Rating Curve= 0 ,0
Exp/Cntr=0.5,0.3

Type RM Length L Ch R = 3 ,65672.5 ,,,
BEGIN DESCRIPTION:
Footbridge
Structure ID: H00-56
END DESCRIPTION:
Bridge Culvert--1,0,-1,-1, 0
Deck Dist Width WeirC Skew NumUp NumDn MinLoCord MaxHiCord MaxSubmerge Is_Ogee
10,4,2.6,0, 60, 60, , , 0.95, 0, 1,1,,
  3703.3  4338.3  4383.3  4563.3  4598.3  4711.9  4777.7  4796.3  4831.8  4927.9
 4945.01  4945.1 5041.89    5042  5046.5  5057.6  5095.8  5153.3    5233  5490.2
  5675.2  5740.2  5780.2  5870.2  5910.2  5940.2  6000.2  6795.2  6815.2  6835.2
  6880.2  6920.2    7447    7542  7733.2  7898.2  7943.2  8248.2  8553.2  8778.2
  8948.2  8978.2  9038.2  9128.2  9233.2  9304.5  9344.5  9474.5  9774.5  9854.5
  9924.5 10714.5 10724.5 10744.5 10784.5 10794.5 10804.5 10814.5 11174.5 11262.2
    47.8      44    42.7      43    44.7    46.2   45.38   44.95   41.18   39.49
   40.11   40.12    43.8    43.8   41.76   42.95   42.31    41.5   40.74    43.6
      43    40.6      43    42.2      40    39.9    43.7      43    41.8    43.2
    42.4    44.8    46.3    44.3    48.3    47.4    44.5    44.9    43.5    45.7
    45.5    44.3    46.6    45.8    48.6   48.61   46.28   46.05   48.23   44.06
    45.9   45.41   48.24    57.5   57.47   51.17   46.98   45.22   44.57   48.33
    47.8      44    42.7      43    44.7   45.95   45.37   43.46   40.58   39.44
      38   39.42    43.1   41.73   41.75   41.81      42   39.81   40.74    43.6
      43    40.6      43    42.2      40    39.9    43.7      43    41.8    43.2
    42.4    44.8    46.3    44.3    48.3    47.4    44.5    44.9    43.5    45.7
    45.5    44.3    46.6    45.8    48.6   48.61   46.28   46.05   48.23   44.06
    45.9   45.41   48.24    57.5   57.47   51.17   46.98   45.22   44.57   48.33
  3703.3  4338.3  4383.3  4563.3  4598.3  4711.9  4777.7  4796.3  4831.8  4927.9
 4945.01  4945.1 5041.89    5042  5046.5  5057.6  5095.8  5153.3    5233  5490.2
  5675.2  5740.2  5780.2  5870.2  5910.2  5940.2  6000.2  6795.2  6815.2  6835.2
  6880.2  6920.2    7447    7542  7733.2  7898.2  7943.2  8248.2  8553.2  8778.2
  8948.2  8978.2  9038.2  9128.2  9233.2  9304.5  9344.5  9474.5  9774.5  9854.5
  9924.5 10714.5 10724.5 10744.5 10784.5 10794.5 10804.5 10814.5 11174.5 11262.2
    47.8      44    42.7      43    44.7    46.2   45.38   44.95   41.18   39.49
   40.11   40.12    43.8    43.8   41.76   42.95   42.31    41.5   40.74    43.6
      43    40.6      43    42.2      40    39.9    43.7      43    41.8    43.2
    42.4    44.8    46.3    44.3    48.3    47.4    44.5    44.9    43.5    45.7
    45.5    44.3    46.6    45.8    48.6   48.61   46.28   46.05   48.23   44.06
    45.9   45.41   48.24    57.5   57.47   51.17   46.98   45.22   44.57   48.33
    47.7    43.9    42.6    42.9    44.6   45.85   45.27   43.36   40.48   39.34
    37.9   39.32      43   41.63   41.65   41.71    41.9   39.71   40.64    43.5
    42.9    40.5    42.9    42.1    39.9    39.8    43.6    42.9    41.7    43.1
    42.3    44.7    46.2    44.2    48.2    47.3    44.4    44.8    43.4    45.6
    45.4    44.2    46.5    45.7    48.5   48.51   46.18   45.95   48.13   43.96
    45.8   45.31   48.14    57.4   57.37   51.07   46.88   45.12   44.47   48.23
Pier Skew, UpSta & Num, DnSta & Num=  ,4979.4, 2 ,4979.4, 2 , 0 , 0 , 0 ,,
       1       1
   29.36   41.74
       1       1
   29.26   41.64
Pier Skew, UpSta & Num, DnSta & Num=  ,5008.3, 2 ,5008.3, 2 , 0 , 0 , 0 ,,
       1       1
   27.34   42.84
       1       1
   27.24   42.74
Abutment Skew #Up #Dn= , 2 , 2
  4944.9  4974.6
   39.42   30.13
  4944.9  4974.6
   39.32   30.03
Abutment Skew #Up #Dn= , 2 , 2
  5014.9 5042.09
   29.44    43.1
  5014.9 5042.09
   29.34      43
BR Coef= 1 , 1 , 0 ,1.25, 0 ,,,0.8,0,2,0,
WSPro=,,,, 1 ,,,, 0 ,,,, 0 ,,,,-1 ,-1 ,-1 , 0 , 0 , 0 , 0 , 0
BR U #Sta/Elev= 155
  3703.3    47.8  3978.3    46.6  4078.3    45.1  4088.3    45.2  4228.3    44.8
  4338.3      44  4383.3    42.7  4458.3    42.7  4463.3      43  4563.3      43
  4598.3    44.7  4698.7    46.1  4711.9   45.95  4768.7    45.3  4776.9   45.36
  4777.7   45.37  4781.9    44.9  4790.3   43.95  4796.3   43.46  4831.6    40.6
  4831.8   40.58  4861.9   39.92  4875.4   39.63  4876.1   39.63  4927.9   39.44
  4928.5   39.44 4944.39   38.05  4944.5   38.04 4944.61   38.03  4944.9   38.01
 4945.01      38  4945.1   37.99  4951.4   37.44  4959.9    33.3  4974.5   30.15
  4974.6   30.13  4979.4   30.43  4990.3   28.94  4991.6   28.35  4999.4   29.02
  5007.5   28.34  5008.3   28.34  5009.7   28.73  5014.8   29.43  5014.9   29.44
  5026.7      34  5038.8   41.71 5041.89   41.73    5042   41.73  5042.1   41.73
 5042.69   41.73  5042.8   41.73 5042.91   41.73  5046.5   41.75  5046.6   41.75
  5054.7   41.79  5057.6   41.81    5058   41.81  5095.8      42  5153.3   39.81
  5180.3   40.59  5180.4    40.6  5184.8   40.72  5187.8   40.81    5233   40.74
  5234.4    41.1  5464.4    42.8  5490.2    43.6  5675.2      43  5715.2    40.8
  5740.2    40.6  5755.2    41.2  5780.2      43  5870.2    42.2  5890.2    41.1
  5910.2      40  5940.2    39.9  5960.2    40.8  5970.2    41.7  6000.2    43.7
  6001.9    43.7  6755.2    42.9  6775.2    42.4  6795.2      43  6815.2    41.8
  6835.2    43.2  6855.2    43.3  6875.2    42.3  6880.2    42.4  6920.2    44.8
    7332    45.2    7352    45.5    7387    45.5    7402    45.8    7447    46.3
    7462    45.9    7507    45.9    7542    44.3    7622    46.6    7662      47
  7733.2    48.3  7898.2    47.4  7913.2    46.9  7943.2    44.5  8248.2    44.9
  8303.2    43.8  8403.2    44.1  8538.2      44  8553.2    43.5  8583.2    44.4
  8598.2    44.5  8613.2    43.6  8628.2    43.5  8778.2    45.7  8893.2    45.3
  8948.2    45.5  8978.2    44.3  9038.2    46.6  9128.2    45.8  9143.2    46.1
  9188.2      48  9233.2    48.6  9253.2      48  9298.2    48.6  9302.7    48.5
  9304.5   48.61  9344.5   46.28  9474.5   46.05  9584.5   46.12  9634.5   47.38
  9744.5   47.16  9774.5   48.23  9854.5   44.06  9884.5   44.31  9904.5   44.83
  9924.5    45.9 10084.5   45.41 10364.5   45.13 10434.5   46.11 10574.5   45.69
 10714.5   45.41 10724.5   48.24 10734.5   52.31 10744.5    57.5 10784.5   57.47
 10794.5   51.17 10804.5   46.98 10814.5   45.22 11024.5   44.78 11044.5   44.16
 11094.5   44.28 11134.5   45.08 11174.5   44.57 11234.5   47.98 11262.2   48.33
BR U #Mann= 7
  3703.3      .2  4711.9      .1  4861.9     .07  4951.4    .035  5038.8      .1
    5051      .2  6001.9      .2
BR U Banks=4951.4,5038.8
BR D #Sta/Elev= 155
  3703.3    47.7  3978.3    46.5  4078.3      45  4088.3    45.1  4228.3    44.7
  4338.3    43.9  4383.3    42.6  4458.3    42.6  4463.3    42.9  4563.3    42.9
  4598.3    44.6  4698.7      46  4711.9   45.85  4768.7    45.2  4776.9   45.26
  4777.7   45.27  4781.9    44.8  4790.3   43.85  4796.3   43.36  4831.6    40.5
  4831.8   40.48  4861.9   39.82  4875.4   39.53  4876.1   39.53  4927.9   39.34
  4928.5   39.34 4944.39   37.95  4944.5   37.94 4944.61   37.93  4944.9   37.91
 4945.01    37.9  4945.1   37.89  4951.4   37.34  4959.9    33.2  4974.5   30.05
  4974.6   30.03  4979.4   30.33  4990.3   28.84  4991.6   28.25  4999.4   28.92
  5007.5   28.24  5008.3   28.24  5009.7   28.63  5014.8   29.33  5014.9   29.34
  5026.7    33.9  5038.8   41.61 5041.89   41.63    5042   41.63  5042.1   41.63
 5042.69   41.63  5042.8   41.63 5042.91   41.63  5046.5   41.65  5046.6   41.65
  5054.7   41.69  5057.6   41.71    5058   41.71  5095.8    41.9  5153.3   39.71
  5180.3   40.49  5180.4    40.5  5184.8   40.62  5187.8   40.71    5233   40.64
  5234.4      41  5464.4    42.7  5490.2    43.5  5675.2    42.9  5715.2    40.7
  5740.2    40.5  5755.2    41.1  5780.2    42.9  5870.2    42.1  5890.2      41
  5910.2    39.9  5940.2    39.8  5960.2    40.7  5970.2    41.6  6000.2    43.6
  6001.9    43.6  6755.2    42.8  6775.2    42.3  6795.2    42.9  6815.2    41.7
  6835.2    43.1  6855.2    43.2  6875.2    42.2  6880.2    42.3  6920.2    44.7
    7332    45.1    7352    45.4    7387    45.4    7402    45.7    7447    46.2
    7462    45.8    7507    45.8    7542    44.2    7622    46.5    7662    46.9
  7733.2    48.2  7898.2    47.3  7913.2    46.8  7943.2    44.4  8248.2    44.8
  8303.2    43.7  8403.2      44  8538.2    43.9  8553.2    43.4  8583.2    44.3
  8598.2    44.4  8613.2    43.5  8628.2    43.4  8778.2    45.6  8893.2    45.2
  8948.2    45.4  8978.2    44.2  9038.2    46.5  9128.2    45.7  9143.2      46
  9188.2    47.9  9233.2    48.5  9253.2    47.9  9298.2    48.5  9302.7    48.4
  9304.5   48.51  9344.5   46.18  9474.5   45.95  9584.5   46.02  9634.5   47.28
  9744.5   47.06  9774.5   48.13  9854.5   43.96  9884.5   44.21  9904.5   44.73
  9924.5    45.8 10084.5   45.31 10364.5   45.03 10434.5   46.01 10574.5   45.59
 10714.5   45.31 10724.5   48.14 10734.5   52.21 10744.5    57.4 10784.5   57.37
 10794.5   51.07 10804.5   46.88 10814.5   45.12 11024.5   44.68 11044.5   44.06
 11094.5   44.18 11134.5   44.98 11174.5   44.47 11234.5   47.88 11262.2   48.23
BR D #Mann= 7
  3703.3      .2  4711.9      .1  4861.9     .07  4951.4    .035  5038.8      .1
    5051      .2  6001.9      .2
BR D Banks=4951.4,5038.8
BC Design=,, 0 ,, 0 ,,,,,,
BC HTab HWMax=57.47
BC Use User HTab Curves=0
BC User HTab FreeFlow(D)= 0

Type RM Length L Ch R = 1 ,65660.5 ,248.5,248.5,248.5
BEGIN DESCRIPTION:
Downstream Section of Bridge/Culvert/Weir
END DESCRIPTION:
XS GIS Cut Line= 6
      3137873.48     13861059.32      3138442.87     13860286.14
      3138708.27     13860062.33       3138934.8     13859634.22
       3140261.8     13855951.24      3140639.52     13854142.19
#Sta/Elev= 30
  3703.3    47.7  4383.3    42.6  4711.9   45.85  4861.9   39.82  4951.4   37.34
  4974.6   30.03  5007.5   28.24  5026.7    33.9  5038.8   41.61  5153.3   39.71
  5490.2    43.5  5940.2    39.8  6001.9    43.6  6815.2    41.7  6920.2    44.7
    7542    44.2  7733.2    48.2  7943.2    44.4  8553.2    43.4  8978.2    44.2
  9233.2    48.5  9474.5   45.95  9774.5   48.13  9854.5   43.96 10714.5   45.31
 10744.5    57.4 10784.5   57.37 10814.5   45.12 11174.5   44.47 11262.2   48.23
#Mann= 7 , 1 , 0
  3703.3      .2       0  4711.9      .1       0  4861.9     .07       0
  4951.4    .035       0  5038.8      .1       0    5051      .2       0
  6001.9      .2       0
#XS Ineff= 2 , 0
       0    4934    39.6    7735       0    48.3
Permanent Ineff=
       F       F
Bank Sta=4951.4,5038.8
XS Rating Curve= 0 ,0
Exp/Cntr=0.5,0.3

Type RM Length L Ch R = 1 ,65412.0 ,250,250,250
BEGIN DESCRIPTION:
Upstream Section of Bridge/Culvert/Weir
END DESCRIPTION:
XS GIS Cut Line= 6
      3137844.82     13861248.26      3138567.39     13860366.59
      3139189.63     13860215.89      3139422.76     13859764.04
      3139642.29     13859176.03      3140763.32     13854227.54
#Sta/Elev= 30
  3539.2    47.6  4002.1      48  4299.2   43.93  4839.2   42.77 4930.72   43.16
 4979.13   30.25 5007.36   28.23 5028.84   29.63 5045.21   37.89 5072.74   45.22
  5139.2   45.43 5260.58   47.15  5362.9    41.6  5749.8    43.2  7665.2    46.8
  7850.2    44.4  7999.2   47.68  8855.2    43.6  9588.4   48.94 10698.4    44.3
 10798.4   45.46 10838.4   55.64 10868.4   45.98 10958.4   46.53 10988.4   54.79
 11138.4   54.68 11198.4   46.92 11298.4   44.56 11428.4   44.31 11531.4   48.85
#Mann= 8 , 1 , 0
  3539.2     .99       0  4299.2      .1       0  4839.2     .07       0
 4930.72    .032       0 5072.74     .07       0  5139.2      .1       0
  5749.8      .2       0  7999.2     .99       0
#XS Ineff= 2 , 0
       0    4920    45.5    5090       0    45.5
Permanent Ineff=
       F       F
Bank Sta=4930.72,5072.74
XS Rating Curve= 0 ,0
Exp/Cntr=0.5,0.3

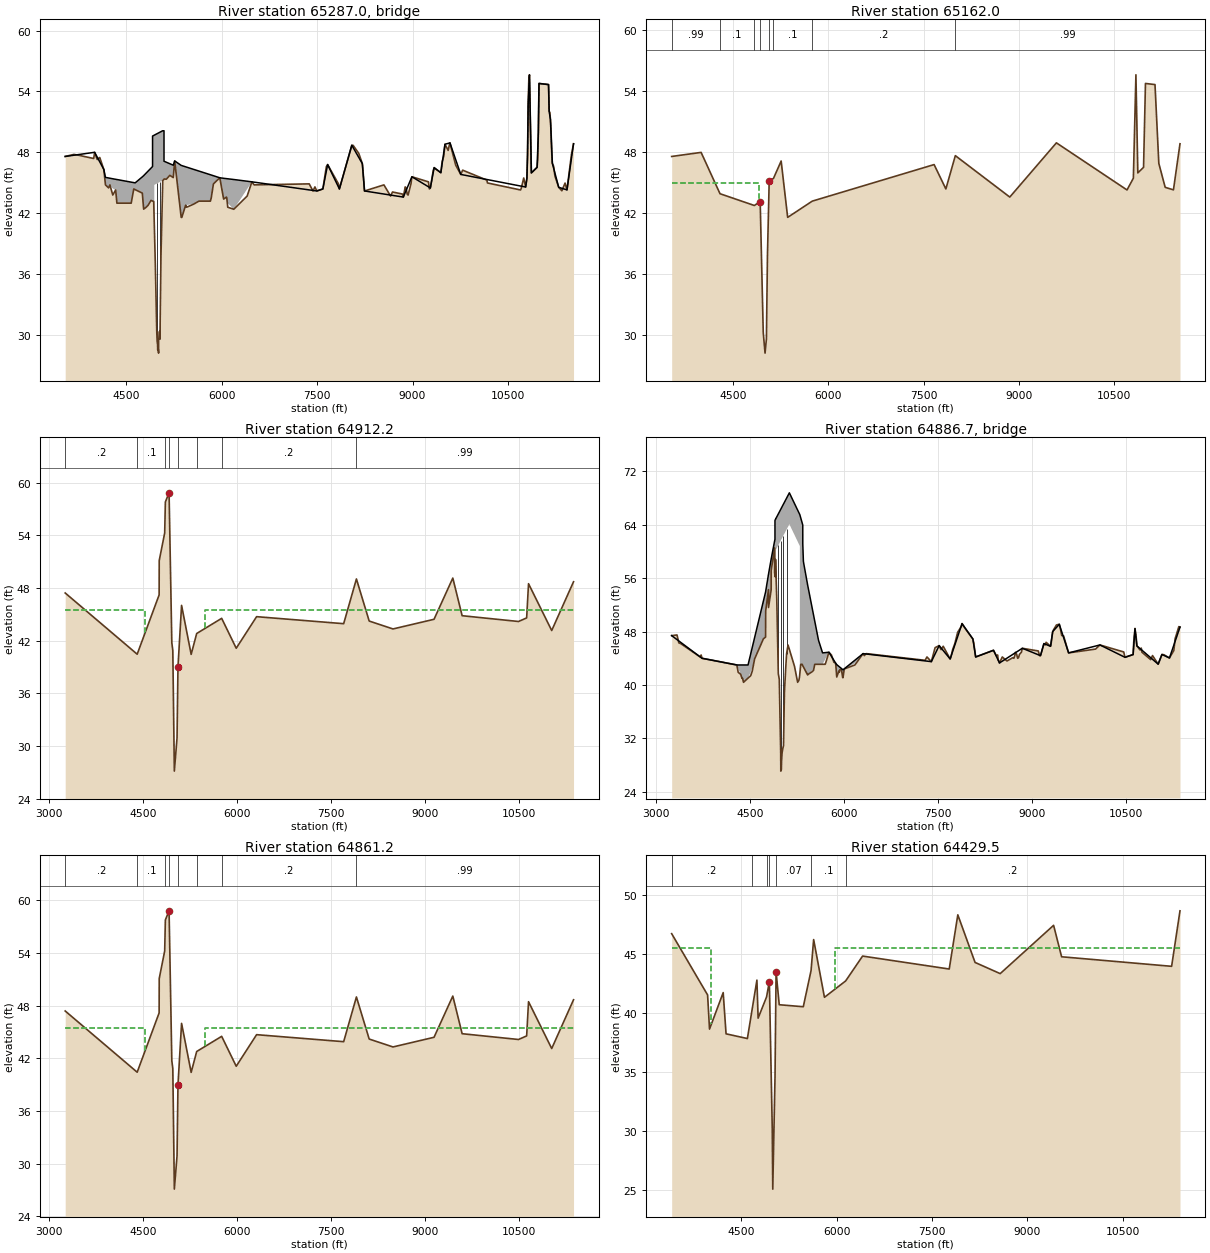
Type RM Length L Ch R = 3 ,65287.0 ,,,
BEGIN DESCRIPTION:
I-610 - 30 Degree Skew
Structure ID: H00-55
END DESCRIPTION:
Bridge Culvert--1,0,-1,-1, 0
Deck Dist Width WeirC Skew NumUp NumDn MinLoCord MaxHiCord MaxSubmerge Is_Ogee
10,230,2.6,0, 60, 60, , , 0.95, 0, 1,1,,
  3539.2  4002.1  4147.1  4172.1  4332.1  4352.1  4577.1  4639.2 4751.46 4772.59
 4912.59  4912.7 4930.72 4940.07 4940.16  5067.7 5067.81 5072.74  5092.7 5092.81
 5237.98 5260.58  5362.9  5432.9    5822  5969.8  6029.9  6189.9  6474.8  7495.2
  7590.2  7665.2  7850.2  8045.3  8210.2  8245.2  8855.2  8990.2  9280.2  9340.2
  9445.2  9510.2  9588.4  9758.4 10778.4 10798.4 10808.4 10818.4 10838.4 10868.4
 10958.4 10978.4 10988.4 11138.4 11148.4 11168.4 11198.4 11298.4 11428.4 11531.4
    47.6   48.01   46.31   45.54   45.35   45.33   45.07      45   45.59   45.71
   46.61   49.61   49.67    49.7    49.7   50.12   50.12   50.13   50.13   47.13
   46.74   47.16   46.72   46.58    45.8    45.5   45.45   45.33    45.1    44.2
    44.4    46.8    44.4    48.7    46.9    44.2    43.6    45.6    44.5    46.5
      46    48.8   48.94   45.83   44.59   45.46   47.78   52.79   55.64   45.98
   46.53   49.99   54.79   54.68   52.03   51.22   46.92   44.56   44.31   48.85
    47.6      48    46.3    44.8    44.3      43      43   44.33   43.99   42.41
   43.21   43.21   43.16   40.88    44.8   45.22   43.91   45.22   45.36   45.36
   45.52   47.15    41.6    42.8    43.2    45.5    43.4    42.4    45.1    44.2
    44.4    46.8    44.4    48.7    46.9    44.2    43.6    45.6    44.5    46.5
      46    48.8   48.94   45.83   44.59   45.46   47.78   52.79   55.64   45.98
   46.53   49.99   54.79   54.68   52.03   51.22   46.92   44.56   44.31   48.85
  3539.2  4002.1  4147.1  4172.1  4332.1  4352.1  4577.1  4639.2 4751.46 4772.59
 4912.59  4912.7 4930.72 4940.07 4940.16  5067.7 5067.81 5072.74  5092.7 5092.81
 5237.98 5260.58  5362.9  5432.9    5822  5969.8  6029.9  6189.9  6474.8  7495.2
  7590.2  7665.2  7850.2  8045.3  8210.2  8245.2  8855.2  8990.2  9280.2  9340.2
  9445.2  9510.2  9588.4  9758.4 10778.4 10798.4 10808.4 10818.4 10838.4 10868.4
 10958.4 10978.4 10988.4 11138.4 11148.4 11168.4 11198.4 11298.4 11428.4 11531.4
   47.63   48.03   46.33   45.54   45.35   45.33   45.07      45   45.59   45.71
   46.61   49.61   49.67    49.7    49.7   50.12   50.12   50.13   50.13   47.13
   46.74   47.18   46.72   46.58    45.8   45.53   45.45   45.33   45.13   44.23
   44.43   46.83   44.43   48.73   46.93   44.23   43.63   45.63   44.53   46.53
   46.03   48.83   48.97   45.86   44.62   45.49   47.81   52.82   55.67   46.01
   46.56   50.02   54.82   54.71   52.06   51.25   46.95   44.59   44.34   48.88
   47.63   48.03   46.33   44.83   44.33   43.03   43.03   44.36   44.02   42.44
   43.24   43.24   43.19   40.91   44.83   45.25   43.94   45.25   45.39   45.39
   45.55   47.18   41.63   42.83   43.23   45.53   43.43   42.43   45.13   44.23
   44.43   46.83   44.43   48.73   46.93   44.23   43.63   45.63   44.53   46.53
   46.03   48.83   48.97   45.86   44.62   45.49   47.81   52.82   55.67   46.01
   46.56   50.02   54.82   54.71   52.06   51.25   46.95   44.59   44.34   48.88
Pier Skew, UpSta & Num, DnSta & Num=  ,4985.5, 2 ,4985.5, 2 , 0 , 0 , 0 ,,
       2       2
   28.31   45.95
       2       2
   28.34   45.98
Pier Skew, UpSta & Num, DnSta & Num=  ,5028.8, 2 ,5028.8, 2 , 0 , 0 , 0 ,,
       2       2
   28.74   46.09
       2       2
   28.77   46.12
Abutment Skew #Up #Dn= , 2 , 2
 4939.96 4944.49
    44.8   39.81
 4939.96 4944.49
   44.83   39.84
Abutment Skew #Up #Dn= , 2 , 2
  5065.3  5067.9
   43.24   45.22
  5065.3  5067.9
   43.27   45.25
BR Coef= 1 , 1 , 0 ,1.25, 0 ,,,0.8,0,2,0,
WSPro=,,,, 1 ,,,, 0 ,,,, 0 ,,,,-1 ,-1 ,-1 , 0 , 0 , 0 , 0 , 0
BR U #Sta/Elev= 167
  3539.2    47.6  3677.1    47.8  3767.1    47.7  3844.2   47.59  3944.2   47.46
  3987.1    47.4  3994.2   47.68  4002.1      48  4042.1    47.3  4079.2   47.49
  4082.1    47.5  4119.2   46.82  4147.1    46.3  4172.1    44.8  4222.1    44.5
  4242.1    44.8  4287.1    43.8  4299.2   43.93  4332.1    44.3  4352.1      43
  4577.1      43  4617.1    44.4  4639.2   44.33  4736.4   44.04 4751.46   43.99
 4772.59   42.41  4777.3   42.43 4807.23   42.57    4820   42.65  4839.2   42.77
 4843.69    42.8    4875   43.13 4888.11   43.27 4912.59   43.21  4912.7   43.21
 4912.81   43.21 4930.72   43.16  4930.9   43.12 4940.07   40.88 4940.16   40.86
 4944.49   39.81 4956.35   36.92 4979.13   30.25 4985.45   29.36 4992.12   29.05
 4993.25   28.56 5002.34   28.62 5007.36   28.23 5007.79   29.47    5022   30.37
 5028.84   29.63 5045.21   37.89  5065.3   43.24  5067.7   43.88 5067.81   43.91
 5072.74   45.22  5078.3   45.26 5092.59   45.36  5092.7   45.36 5092.81   45.36
 5095.35   45.38  5109.1   45.37 5129.55   45.36  5139.2   45.43  5150.5   45.51
 5183.85   45.74  5209.1   45.64 5237.98   45.52 5260.58   47.15  5278.4   46.18
  5362.9    41.6  5372.9    41.6  5432.9    42.8  5447.9    42.6  5557.9    42.9
    5642    43.2  5749.8    43.2    5822    43.2  5834.9    43.5  5869.9    44.9
  5969.8    45.5  5969.9    45.5  6029.9    43.4  6074.9    43.6  6079.9    43.5
  6094.9    42.6  6189.9    42.4  6399.9    43.7  6474.8    45.1  6474.9    45.1
  6510.2    44.8  7375.2    44.9  7435.2    44.2  7465.2    44.6  7495.2    44.2
  7590.2    44.4  7645.2    46.6  7665.2    46.8  7835.2    44.9  7850.2    44.4
  7999.2   47.68  8045.3    48.7  8065.2    48.7  8155.2    47.9  8210.2    46.9
  8215.2    46.7  8240.2    44.5  8245.2    44.2  8550.2    44.8  8655.2    43.7
  8685.2    44.1  8840.2    43.9  8855.2    43.6  8885.2    44.6  8900.2    44.5
  8915.2    43.9  8930.2    43.8  8975.2    44.9  8990.2    45.6  9250.2    45.1
  9265.2    44.4  9280.2    44.5  9325.2    46.2  9340.2    46.5  9355.2    46.4
  9445.2      46  9465.2    47.1  9490.2    47.6  9510.2    48.8  9560.2    48.2
  9581.6    48.8  9588.4   48.94  9678.4   46.75  9758.4   45.83  9788.4   46.25
 10168.4   45.27 10178.4   44.99 10698.4    44.3 10708.4   44.44 10748.4   45.48
 10778.4   44.59 10798.4   45.46 10808.4   47.78 10818.4   52.79 10828.4   55.16
 10838.4   55.64 10858.4   48.95 10868.4   45.98 10958.4   46.53 10968.4   47.31
 10978.4   49.99 10988.4   54.79 11138.4   54.68 11148.4   52.03 11158.4   51.95
 11168.4   51.22 11178.4   49.99 11188.4      48 11198.4   46.92 11218.4   46.63
 11238.4   45.68 11298.4   44.56 11348.4   44.22 11398.4   44.98 11428.4   44.31
 11498.4   47.78 11531.4   48.85
BR U #Mann= 8
  3539.2     .99  4299.2      .1  4839.2     .07 4930.72    .032 5072.74     .07
  5139.2      .1  5749.8      .2  7999.2     .99
BR U Banks=4930.72,5072.74
BR D #Sta/Elev= 167
  3539.2   47.63  3677.1   47.83  3767.1   47.73  3844.2   47.62  3944.2   47.49
  3987.1   47.43  3994.2   47.71  4002.1   48.03  4042.1   47.33  4079.2   47.52
  4082.1   47.53  4119.2   46.85  4147.1   46.33  4172.1   44.83  4222.1   44.53
  4242.1   44.83  4287.1   43.83  4299.2   43.96  4332.1   44.33  4352.1   43.03
  4577.1   43.03  4617.1   44.43  4639.2   44.36  4736.4   44.07 4751.46   44.02
 4772.59   42.44  4777.3   42.46 4807.23    42.6    4820   42.68  4839.2    42.8
 4843.69   42.83    4875   43.16 4888.11    43.3 4912.59   43.24  4912.7   43.24
 4912.81   43.24 4930.72   43.19  4930.9   43.15 4940.07   40.91 4940.16   40.89
 4944.49   39.84 4956.35   36.95 4979.13   30.28 4985.45   29.39 4992.12   29.08
 4993.25   28.59 5002.34   28.65 5007.36   28.26 5007.79    29.5    5022    30.4
 5028.84   29.66 5045.21   37.92  5065.3   43.27  5067.7   43.91 5067.81   43.94
 5072.74   45.25  5078.3   45.29 5092.59   45.39  5092.7   45.39 5092.81   45.39
 5095.35   45.41  5109.1    45.4 5129.55   45.39  5139.2   45.46  5150.5   45.54
 5183.85   45.77  5209.1   45.67 5237.98   45.55 5260.58   47.18  5278.4   46.21
  5362.9   41.63  5372.9   41.63  5432.9   42.83  5447.9   42.63  5557.9   42.93
    5642   43.23  5749.8   43.23    5822   43.23  5834.9   43.53  5869.9   44.93
  5969.8   45.53  5969.9   45.53  6029.9   43.43  6074.9   43.63  6079.9   43.53
  6094.9   42.63  6189.9   42.43  6399.9   43.73  6474.8   45.13  6474.9   45.13
  6510.2   44.83  7375.2   44.93  7435.2   44.23  7465.2   44.63  7495.2   44.23
  7590.2   44.43  7645.2   46.63  7665.2   46.83  7835.2   44.93  7850.2   44.43
  7999.2   47.71  8045.3   48.73  8065.2   48.73  8155.2   47.93  8210.2   46.93
  8215.2   46.73  8240.2   44.53  8245.2   44.23  8550.2   44.83  8655.2   43.73
  8685.2   44.13  8840.2   43.93  8855.2   43.63  8885.2   44.63  8900.2   44.53
  8915.2   43.93  8930.2   43.83  8975.2   44.93  8990.2   45.63  9250.2   45.13
  9265.2   44.43  9280.2   44.53  9325.2   46.23  9340.2   46.53  9355.2   46.43
  9445.2   46.03  9465.2   47.13  9490.2   47.63  9510.2   48.83  9560.2   48.23
  9581.6   48.83  9588.4   48.97  9678.4   46.78  9758.4   45.86  9788.4   46.28
 10168.4    45.3 10178.4   45.02 10698.4   44.33 10708.4   44.47 10748.4   45.51
 10778.4   44.62 10798.4   45.49 10808.4   47.81 10818.4   52.82 10828.4   55.19
 10838.4   55.67 10858.4   48.98 10868.4   46.01 10958.4   46.56 10968.4   47.34
 10978.4   50.02 10988.4   54.82 11138.4   54.71 11148.4   52.06 11158.4   51.98
 11168.4   51.25 11178.4   50.02 11188.4   48.03 11198.4   46.95 11218.4   46.66
 11238.4   45.71 11298.4   44.59 11348.4   44.25 11398.4   45.01 11428.4   44.34
 11498.4   47.81 11531.4   48.88
BR D #Mann= 8
  3539.2     .99  4299.2      .1  4839.2     .07 4930.72    .032 5072.74     .07
  5139.2      .1  5749.8      .2  7999.2     .99
BR D Banks=4930.72,5072.74
BC Design=,, 0 ,, 0 ,,,,,,
BC HTab HWMax=55.64
BC Use User HTab Curves=0
BC User HTab FreeFlow(D)= 0

Type RM Length L Ch R = 1 ,65162.0 ,249.8,249.8,249.8
BEGIN DESCRIPTION:
Downstream Section of Bridge/Culvert/Weir
END DESCRIPTION:
XS GIS Cut Line= 6
       3138015.9     13861430.56      3138738.47     13860548.89
      3139360.71     13860398.19      3139593.84     13859946.34
      3139813.37     13859358.33       3140934.4     13854409.83
#Sta/Elev= 30
  3539.2   47.59  4002.1   47.99  4299.2   43.92  4839.2   42.76 4930.72   43.15
 4979.13   30.24 5007.36   28.22 5028.84   29.62 5045.21   37.88 5072.74   45.21
  5139.2   45.42 5260.58   47.14  5362.9   41.59  5749.8   43.19  7665.2   46.79
  7850.2   44.39  7999.2   47.67  8855.2   43.59  9588.4   48.93 10698.4   44.29
 10798.4   45.45 10838.4   55.63 10868.4   45.97 10958.4   46.52 10988.4   54.78
 11138.4   54.67 11198.4   46.91 11298.4   44.55 11428.4    44.3 11531.4   48.84
#Mann= 8 , 1 , 0
  3539.2     .99       0  4299.2      .1       0  4839.2     .07       0
 4930.72    .032       0 5072.74     .07       0  5139.2      .1       0
  5749.8      .2       0  7999.2     .99       0
#XS Ineff= 2 , 0
       0    4920      45    5090       0      45
Permanent Ineff=
       F       F
Bank Sta=4930.72,5072.74
XS Rating Curve= 0 ,0
Exp/Cntr=0.5,0.3

Type RM Length L Ch R = 1 ,64912.2 ,51,51,51
BEGIN DESCRIPTION:
Upstream Section of Bridge/Culvert/Weir
END DESCRIPTION:
XS GIS Cut Line= 6
      3137939.97     13861483.25      3138883.77     13861095.82
      3139322.88     13860478.22      3140008.38     13859827.85
      3140353.35     13857852.14      3141040.52     13854548.73
#Sta/Elev= 30
  3252.4   47.44  4401.4   40.46 4751.72   47.22 4753.36   51.14 4840.57   54.28
  4851.4   57.82 4910.46   58.86 4954.45   41.76  4970.3   40.89 4994.63   27.13
 5037.76   30.92 5052.65      39 5110.16   46.03  5263.2   40.44  5351.4   42.82
  5750.2   44.55  5982.7   41.14  6307.7   44.74  7697.8   43.94  7901.4   49.04
  8105.3   44.24  8485.3   43.34  9140.3   44.44  9440.3   49.14    9589   44.85
   10489   44.19   10619    44.6   10649    48.5   11019   43.16 11367.4   48.72
#Mann= 8 , 1 , 0
  3252.4      .2       0  4401.4      .1       0  4851.4     .07       0
 4910.46    .032       0 5052.65     .07       0  5351.4      .1       0
  5750.2      .2       0  7901.4     .99       0
#XS Ineff= 2 , 0
       0    4520    45.5    5490       0    45.5
Permanent Ineff=
       F       F
Bank Sta=4910.46,5052.65
XS Rating Curve= 0 ,0
Exp/Cntr=0.5,0.3

Type RM Length L Ch R = 3 ,64886.7 ,,,
BEGIN DESCRIPTION:
KELLY ROAD - Skewed 30 Degrees
Structure ID: H00-54
END DESCRIPTION:
Bridge Culvert--1,0,-1,-1, 0
Deck Dist Width WeirC Skew NumUp NumDn MinLoCord MaxHiCord MaxSubmerge Is_Ogee
10,31,2.6,0, 60, 60, , , 0.95, 0, 1,1,,
  3252.4  3737.4  4292.4  4399.3  4471.4 4751.72 4753.36 4798.14 4798.57 4840.57
 4841.35 4895.82 4895.99 4901.29  4901.4  4902.7 4906.47 4910.46 4915.65 4915.74
 4915.82  5131.2 5298.66 5298.77  5345.3 5345.41  5355.4  5423.2  5596.4  5661.4
  5762.7  5867.7  5887.7  5962.7  5987.7  6307.7  7397.8  7522.8  7697.8  7887.8
  8060.3  8105.3  8390.3  8485.3  8850.3  9140.3  9195.3  9300.3  9335.3  9440.3
    9589   10089   10489   10619   10649   10679   11019   11079   11199 11367.4
    47.4      44      43      43      43   53.95   54.05    56.6   56.62   58.86
    58.9   61.59   61.59   61.84   64.64    64.7   64.77   64.84   64.93   64.93
   64.94    68.8   65.52   65.51   63.97   61.17    58.5   54.98   46.71   44.81
   44.91   43.31   43.05   42.47   42.27    44.7    43.5    45.9    43.9    49.2
    46.9    44.2    45.2    43.3    45.5    44.4    46.2    45.8      48    49.1
   44.81      46   44.15   44.56   48.46   45.87   43.12   44.57   44.05   48.68
    47.4      44      43    40.4   41.03   47.18    51.1   54.29   51.61   54.24
   57.16   60.54   56.79    56.5   56.49   56.42   56.21   58.82   57.27   60.23
   60.24    64.1   60.82   41.73   42.88   42.88   42.71    41.5    43.1    43.1
    44.9    43.3    41.2    42.3    41.1    44.7    43.5    45.9    43.9    49.2
    46.9    44.2    45.2    43.3    45.5    44.4    46.2    45.8      48    49.1
   44.81      46   44.15   44.56   48.46   45.87   43.12   44.57   44.05   48.68
  3252.4  3737.4  4292.4  4399.3  4471.4 4751.72 4753.36 4798.14 4798.57 4840.57
 4841.35 4895.82 4895.99 4901.29  4901.4  4902.7 4906.47 4910.46 4915.65 4915.74
 4915.82  5131.2 5298.66 5298.77  5345.3 5345.41  5355.4  5423.2  5596.4  5661.4
  5762.7  5867.7  5887.7  5962.7  5987.7  6307.7  7397.8  7522.8  7697.8  7887.8
  8060.3  8105.3  8390.3  8485.3  8850.3  9140.3  9195.3  9300.3  9335.3  9440.3
    9589   10089   10489   10619   10649   10679   11019   11079   11199 11367.4
   47.45   44.05   43.05      43      43   53.95   54.05    56.6   56.62   58.86
    58.9   61.59   61.59   61.84   64.64    64.7   64.77   64.84   64.93   64.93
   64.94    68.8   65.52   65.51   63.97   61.17    58.5   54.98   46.71   44.81
   44.95   43.35   43.05   42.47   42.27   44.75   43.55   45.95   43.95   49.25
   46.95   44.25   45.25   43.35   45.55   44.45   46.25   45.85   48.05   49.15
   44.86   46.05    44.2   44.61   48.51   45.92   43.17   44.62    44.1   48.73
   47.45   44.05   43.05   40.45   41.08   47.23   51.15   54.34   51.66   54.29
   57.21   60.59   56.84   56.55   56.54   56.47   56.26   58.87   57.32   60.28
   60.29   64.15   60.87   41.78   42.93   42.93   42.76   41.55   43.15   43.15
   44.95   43.35   41.25   42.35   41.15   44.75   43.55   45.95   43.95   49.25
   46.95   44.25   45.25   43.35   45.55   44.45   46.25   45.85   48.05   49.15
   44.86   46.05    44.2   44.61   48.51   45.92   43.17   44.62    44.1   48.73
Pier Skew, UpSta & Num, DnSta & Num=  ,4954.4, 2 ,4954.4, 2 , 0 , 0 , 0 ,,
       2       2
   40.67   61.95
       2       2
   40.72      62
Pier Skew, UpSta & Num, DnSta & Num=  ,4993.1, 2 ,4993.1, 2 , 0 , 0 , 0 ,,
       2       2
   26.84   62.64
       2       2
   26.89   62.69
Pier Skew, UpSta & Num, DnSta & Num=  ,5031.4, 2 ,5031.4, 2 , 0 , 0 , 0 ,,
       2       2
   29.65   63.33
       2       2
    29.7   63.38
Pier Skew, UpSta & Num, DnSta & Num=  ,5087.3, 2 ,5087.3, 2 , 0 , 0 , 0 ,,
       2       2
   43.55   64.33
       2       2
    43.6   64.38
BR Coef= 1 , 1 , 0 ,1.25, 0 ,,,0.8,0,2,0,
WSPro=,,,, 1 ,,,, 0 ,,,, 0 ,,,,-1 ,-1 ,-1 , 0 , 0 , 0 , 0 , 0
BR U #Sta/Elev= 188
  3252.4    47.4  3337.4    47.5  3367.4    46.3  3397.4    46.2  3552.4    45.2
  3707.4    44.2  3722.4    44.5  3737.4      44  3852.4    43.8  4201.4   43.17
  4292.4      43  4314.3    41.9  4354.3    41.6  4374.3      41  4384.3      41
  4399.3    40.4  4401.4   40.42  4471.4   41.03  4514.3    41.4  4539.3    42.1
  4574.3    43.8  4576.2    43.9    4691   46.36 4716.04    46.9  4716.8   46.91
 4751.72   47.18 4753.36    51.1  4764.3   51.88 4798.14   54.29 4798.57   51.61
  4817.9   52.82 4840.57   54.24 4841.35   57.16  4851.4   57.78  4879.4   59.52
 4895.82   60.54 4895.99   56.79 4901.29    56.5  4901.4   56.49 4901.51   56.48
  4902.7   56.42 4906.47   56.21 4910.46   58.82 4915.65   57.27 4915.74   57.25
 4915.82   57.22 4930.11   52.97 4954.45   41.72  4970.3   40.85 4985.36   33.54
 4993.07   29.73 4993.68   28.36 4994.63   27.09 4998.61   27.19 5003.38   27.32
 5006.32   28.54 5015.59   29.87 5031.44    30.7 5037.76   30.88 5052.65   38.96
 5072.92   42.53 5087.29    44.7 5110.16   45.99  5131.2   45.34  5213.2    42.8
  5244.9   41.28  5263.2    40.4  5283.2    40.7  5293.2    41.2 5298.58   41.71
 5298.66   41.72 5298.77   41.73  5313.2    43.1  5333.2    43.1    5345   42.89
 5345.19   42.89  5345.3   42.88 5345.41   42.88  5351.4   42.78  5355.4   42.71
  5423.2    41.5    5431   41.59    5432    41.6  5460.4   41.77  5461.7   41.78
    5497      42    5517    42.2    5537    43.1    5561    43.1  5596.4    43.1
  5661.4    43.1    5702    43.1  5707.7    43.2  5750.2   44.51  5762.7    44.9
  5802.7    44.5  5842.7    43.4  5867.7    43.3  5872.7      43  5887.7    41.2
  5922.7    42.1  5927.7    41.9  5932.7      42  5937.7    42.3  5962.7    42.3
  5982.7    41.1  5987.7    41.1  6007.7    42.4  6009.9   42.41  6032.2   42.49
  6177.7      43  6307.7    44.7  6327.7    44.4  6357.8    44.7  7297.8    43.7
  7327.8    44.2  7397.8    43.5  7457.8    45.6  7522.8    45.9  7552.8    45.3
  7587.8    45.8  7697.8    43.9  7707.8    44.1  7737.8    45.3  7772.8    46.2
  7817.8    47.9  7877.8    48.8  7887.8    49.2  7901.4      49  7935.3    48.5
  8060.3    46.9  8075.3    46.3  8105.3    44.2  8390.3    45.2  8440.3    44.3
  8455.3    44.5  8465.3    43.8  8485.3    43.3  8530.3    44.2  8605.3    43.6
  8700.3    44.1  8715.3      44  8730.3    44.4  8740.3    44.9  8760.3    44.6
  8775.3      44  8790.3    44.1  8805.3    44.6  8835.3    44.9  8850.3    45.5
  9105.3    45.1  9125.3    44.4  9140.3    44.4  9195.3    46.2  9215.3      46
  9230.3    46.4  9300.3    45.8  9305.3    45.9  9335.3      48  9350.3    48.3
  9395.3      49  9440.3    49.1  9460.5    48.3    9479   47.42    9509   47.36
    9589   44.81   10019   45.38   10089      46   10469   44.95   10489   44.15
   10619   44.56   10629   46.46   10649   48.46   10669   47.04   10679   45.87
   10729   45.25   10749   45.53   10759   44.92   10899    43.8   10929   44.41
   11019   43.12   11079   44.57   11109   44.54   11199   44.05   11269   45.17
   11289   46.92   11349   48.75 11367.4   48.68
BR U #Mann= 8
  3252.4      .2  4401.4      .1  4851.4     .07 4910.46    .032 5052.65     .07
  5351.4      .1  5750.2      .2  7901.4     .99
BR U Banks=4910.46,5052.65
BR D #Sta/Elev= 188
  3252.4   47.45  3337.4   47.55  3367.4   46.35  3397.4   46.25  3552.4   45.25
  3707.4   44.25  3722.4   44.55  3737.4   44.05  3852.4   43.85  4201.4   43.22
  4292.4   43.05  4314.3   41.95  4354.3   41.65  4374.3   41.05  4384.3   41.05
  4399.3   40.45  4401.4   40.47  4471.4   41.08  4514.3   41.45  4539.3   42.15
  4574.3   43.85  4576.2   43.95    4691   46.41 4716.04   46.95  4716.8   46.96
 4751.72   47.23 4753.36   51.15  4764.3   51.93 4798.14   54.34 4798.57   51.66
  4817.9   52.87 4840.57   54.29 4841.35   57.21  4851.4   57.83  4879.4   59.57
 4895.82   60.59 4895.99   56.84 4901.29   56.55  4901.4   56.54 4901.51   56.53
  4902.7   56.47 4906.47   56.26 4910.46   58.87 4915.65   57.32 4915.74    57.3
 4915.82   57.27 4930.11   53.02 4954.45   41.77  4970.3    40.9 4985.36   33.59
 4993.07   29.78 4993.68   28.41 4994.63   27.14 4998.61   27.24 5003.38   27.37
 5006.32   28.59 5015.59   29.92 5031.44   30.75 5037.76   30.93 5052.65   39.01
 5072.92   42.58 5087.29   44.75 5110.16   46.04  5131.2   45.39  5213.2   42.85
  5244.9   41.33  5263.2   40.45  5283.2   40.75  5293.2   41.25 5298.58   41.76
 5298.66   41.77 5298.77   41.78  5313.2   43.15  5333.2   43.15    5345   42.94
 5345.19   42.94  5345.3   42.93 5345.41   42.93  5351.4   42.83  5355.4   42.76
  5423.2   41.55    5431   41.64    5432   41.65  5460.4   41.82  5461.7   41.83
    5497   42.05    5517   42.25    5537   43.15    5561   43.15  5596.4   43.15
  5661.4   43.15    5702   43.15  5707.7   43.25  5750.2   44.56  5762.7   44.95
  5802.7   44.55  5842.7   43.45  5867.7   43.35  5872.7   43.05  5887.7   41.25
  5922.7   42.15  5927.7   41.95  5932.7   42.05  5937.7   42.35  5962.7   42.35
  5982.7   41.15  5987.7   41.15  6007.7   42.45  6009.9   42.46  6032.2   42.54
  6177.7   43.05  6307.7   44.75  6327.7   44.45  6357.8   44.75  7297.8   43.75
  7327.8   44.25  7397.8   43.55  7457.8   45.65  7522.8   45.95  7552.8   45.35
  7587.8   45.85  7697.8   43.95  7707.8   44.15  7737.8   45.35  7772.8   46.25
  7817.8   47.95  7877.8   48.85  7887.8   49.25  7901.4   49.05  7935.3   48.55
  8060.3   46.95  8075.3   46.35  8105.3   44.25  8390.3   45.25  8440.3   44.35
  8455.3   44.55  8465.3   43.85  8485.3   43.35  8530.3   44.25  8605.3   43.65
  8700.3   44.15  8715.3   44.05  8730.3   44.45  8740.3   44.95  8760.3   44.65
  8775.3   44.05  8790.3   44.15  8805.3   44.65  8835.3   44.95  8850.3   45.55
  9105.3   45.15  9125.3   44.45  9140.3   44.45  9195.3   46.25  9215.3   46.05
  9230.3   46.45  9300.3   45.85  9305.3   45.95  9335.3   48.05  9350.3   48.35
  9395.3   49.05  9440.3   49.15  9460.5   48.35    9479   47.47    9509   47.41
    9589   44.86   10019   45.43   10089   46.05   10469      45   10489    44.2
   10619   44.61   10629   46.51   10649   48.51   10669   47.09   10679   45.92
   10729    45.3   10749   45.58   10759   44.97   10899   43.85   10929   44.46
   11019   43.17   11079   44.62   11109   44.59   11199    44.1   11269   45.22
   11289   46.97   11349    48.8 11367.4   48.73
BR D #Mann= 8
  3252.4      .2  4401.4      .1  4851.4     .07 4910.46    .032 5052.65     .07
  5351.4      .1  5750.2      .2  7901.4     .99
BR D Banks=4910.46,5052.65
BC Design=,, 0 ,, 0 ,,,,,,
BC HTab HWMax=60.58
BC Use User HTab Curves=0
BC User HTab FreeFlow(D)= 0

Type RM Length L Ch R = 1 ,64861.2 ,431.7,431.7,431.7
BEGIN DESCRIPTION:
Downstream Section of Bridge/Culvert/Weir
END DESCRIPTION:
XS GIS Cut Line= 6
      3137990.39     13861490.88      3138934.19     13861103.46
       3139373.3     13860485.86       3140058.8     13859835.49
      3140403.77     13857859.78      3141090.95     13854556.37
#Sta/Elev= 30
  3252.4    47.4  4401.4   40.42 4751.72   47.18 4753.36    51.1 4840.57   54.24
  4851.4   57.78 4910.46   58.82 4954.45   41.72  4970.3   40.85 4994.63   27.09
 5037.76   30.88 5052.65   38.96 5110.16   45.99  5263.2    40.4  5351.4   42.78
  5750.2   44.51  5982.7    41.1  6307.7    44.7  7697.8    43.9  7901.4      49
  8105.3    44.2  8485.3    43.3  9140.3    44.4  9440.3    49.1    9589   44.81
   10489   44.15   10619   44.56   10649   48.46   11019   43.12 11367.4   48.68
#Mann= 8 , 1 , 0
  3252.4      .2       0  4401.4      .1       0  4851.4     .07       0
 4910.46    .032       0 5052.65     .07       0  5351.4      .1       0
  5750.2      .2       0  7901.4     .99       0
#XS Ineff= 2 , 0
       0    4520    45.5    5490       0    45.5
Permanent Ineff=
       F       F
Bank Sta=4910.46,5052.65
XS Rating Curve= 0 ,0
Exp/Cntr=0.5,0.3

Type RM Length L Ch R = 1 ,64429.5 ,63,63,63
BEGIN DESCRIPTION:
Upstream Section of Bridge/Culvert/Weir
END DESCRIPTION:
XS GIS Cut Line= 6
      3138867.44     13861819.46      3138895.17     13861239.13
      3140243.83     13860307.12       3140309.6     13859469.04
      3140608.62      13857709.6      3141231.22     13854624.39
#Sta/Elev= 30
  3407.1   46.75  3972.1   41.55  4002.5   38.65  4217.4   41.75  4262.4   38.25
    4598   37.85  4669.4   40.22 4747.73   42.81 4766.61   39.58  4899.4   41.38
 4943.28   42.68 4989.18   30.16 4997.06   25.07 5032.65   34.63 5049.36   43.49
  5098.9   40.72  5477.2   40.55  5599.4   43.62    5640   46.25    5810   41.35
  6143.6   42.74    6410   44.85  7772.5   43.75  7907.5   48.35  8178.7   44.31
  8574.1   43.36  9414.1   47.46    9540   44.79 11270.2   43.98   11402   48.69
#Mann= 7 , 1 , 0
  3407.1      .2       0  4669.4      .1       0  4899.4     .07       0
 4943.28    .035       0 5049.36     .07       0  5599.4      .1       0
  6143.6      .2       0
#XS Ineff= 2 , 0
       0    4030    45.5    5980       0    45.5
Permanent Ineff=
       F       F
Bank Sta=4943.28,5049.36
XS Rating Curve= 0 ,0
Exp/Cntr=0.5,0.3