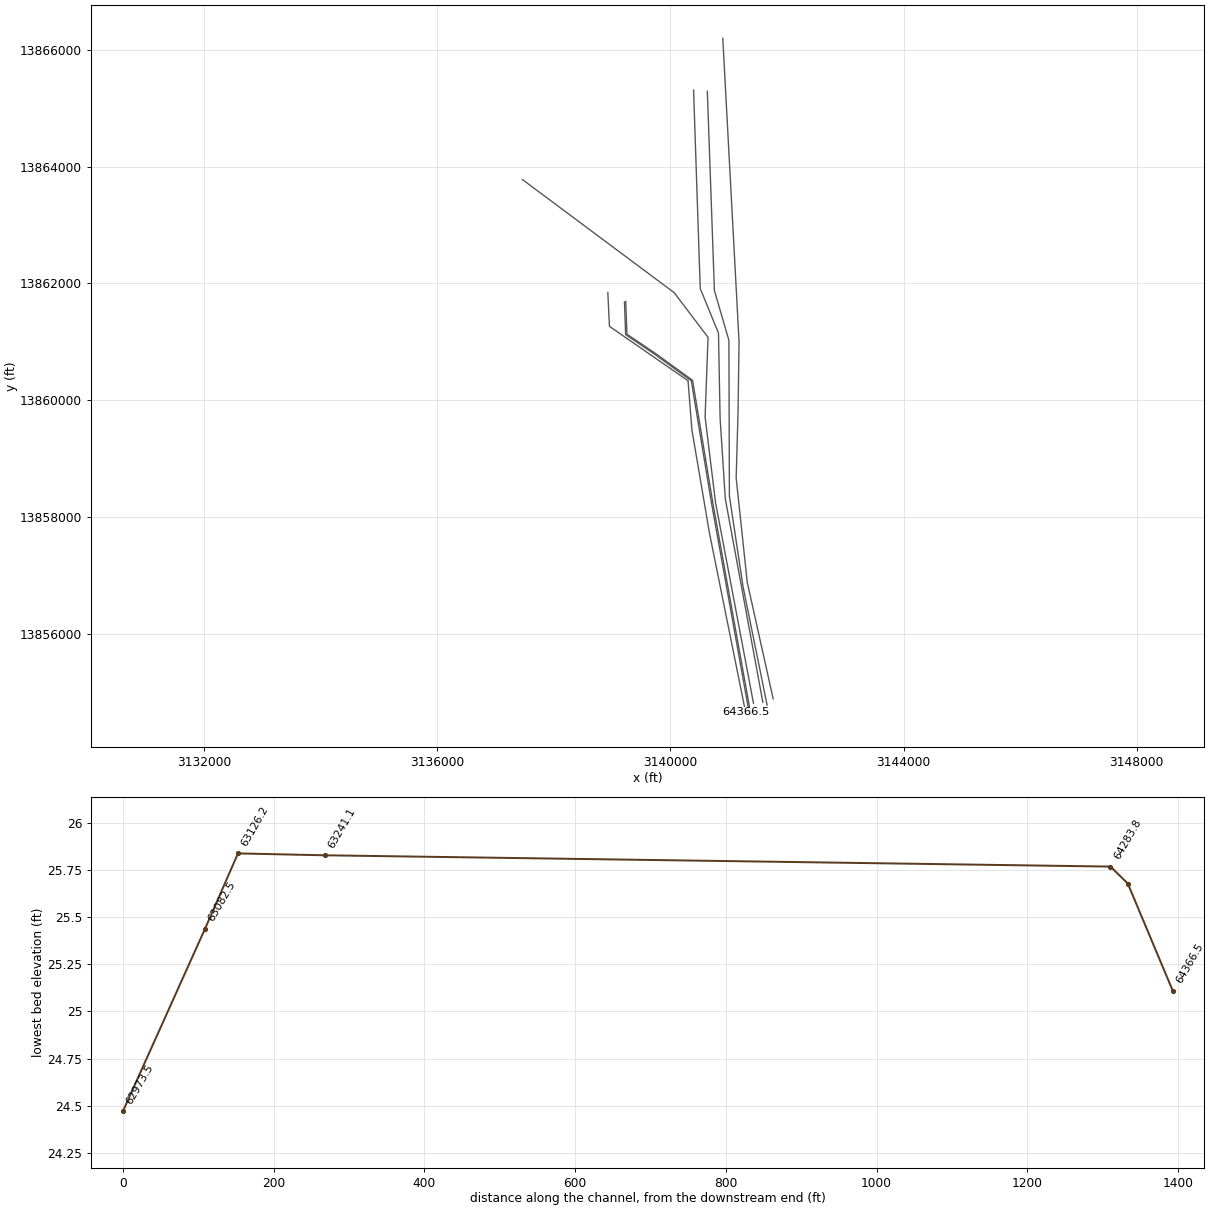
HEC-RAS study H100-00-00.prj: H100-00-00

--- H100-00-00.g01 (geometry) --- (continued)

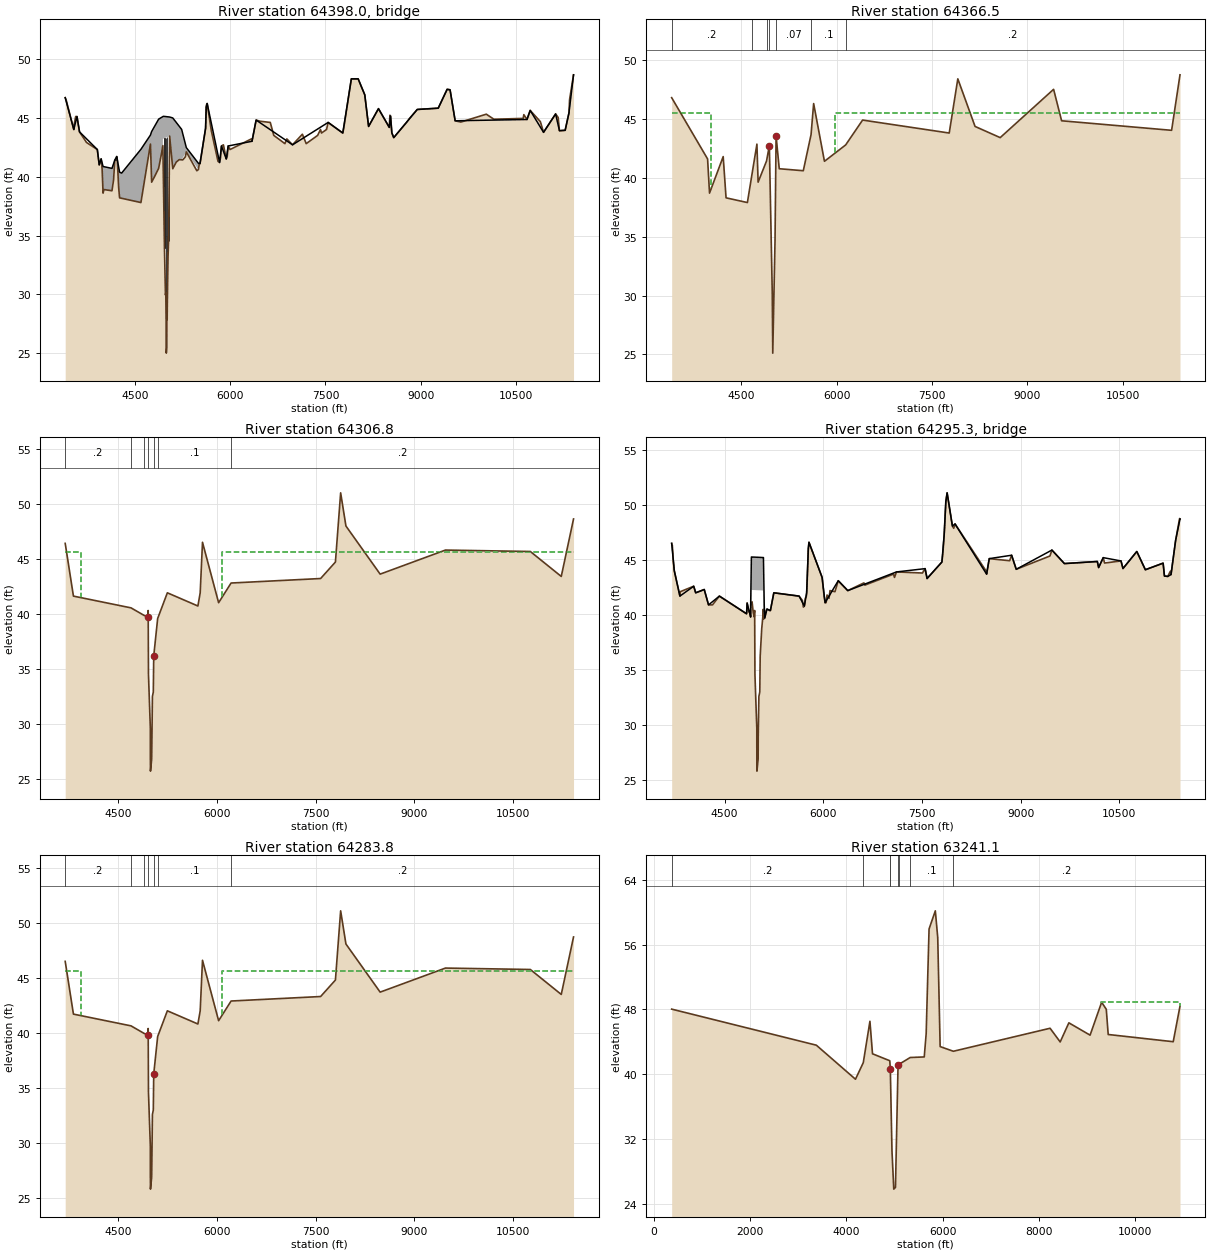
Type RM Length L Ch R = 3 ,64398.0 ,,,
BEGIN DESCRIPTION:
KELLY STREET-WEST - Skewed 30 Degrees
Structure ID: H00-53
END DESCRIPTION:
Bridge Culvert--1,0,-1,-1, 0
Deck Dist Width WeirC Skew NumUp NumDn MinLoCord MaxHiCord MaxSubmerge Is_Ogee
10,43,2.6,0, 60, 60, , , 0.95, 0, 1,1,,
  3407.1  3542.1  3592.1  3632.1  3912.1  3942.1  3972.1  4002.5  4142.5  4187.4
  4217.4  4262.4  4294.4    4598 4747.73 4766.61 4876.77 4944.23 4944.32  4950.7
 5049.36  5098.9  5238.4  5312.2  5502.2  5527.2    5615    5625    5640    5835
    5865    5940    5970    6345    6410  6982.5  7542.5  7772.5  7907.5  8014.5
  8118.7  8178.7  8334.1  8504.1  8524.1  8544.1  8574.1  8944.1  9274.1  9414.1
    9460    9540 10670.2 10720.2 10930.2 11120.2 11180.2 11270.2 11330.2   11402
    46.7      44    45.1    43.8    42.3      41   41.51   40.86    40.7   41.41
   41.71   40.38    40.3   42.32   43.53   43.83   44.88    45.1    45.1   45.12
   45.06   44.98   44.01   42.46   41.13   41.11   44.11   45.91   46.21    41.2
    42.6    41.5    42.6      43    44.8    42.7    44.6    43.7    48.3    48.3
   46.94   44.26   45.77   44.18   45.14   43.72   43.31    45.7   45.81   47.41
   47.37   44.74   44.85   45.62   43.76   45.32    43.9   43.93   45.41   48.64
    46.7      44    45.1    43.8    42.3      41    41.5    38.6    38.8    41.4
    41.7    38.2   38.16    37.8   42.76   39.53    40.7    42.3    43.2   43.22
   43.44   40.67   41.43    42.1    40.6    41.1    44.1    45.9    46.2    41.2
    42.6    41.5    42.6      43    44.8    42.7    44.6    43.7    48.3    48.3
   46.94   44.26   45.77   44.18   45.14   43.72   43.31    45.7   45.81   47.41
   47.37   44.74   44.85   45.62   43.76   45.32    43.9   43.93   45.41   48.64
  3407.1  3542.1  3592.1  3632.1  3912.1  3942.1  3972.1  4002.5  4142.5  4187.4
  4217.4  4262.4  4294.4    4598 4747.73 4766.61 4876.77 4944.23 4944.32  4950.7
 5049.36  5098.9  5238.4  5312.2  5502.2  5527.2    5615    5625    5640    5835
    5865    5940    5970    6345    6410  6982.5  7542.5  7772.5  7907.5  8014.5
  8118.7  8178.7  8334.1  8504.1  8524.1  8544.1  8574.1  8944.1  9274.1  9414.1
    9460    9540 10670.2 10720.2 10930.2 11120.2 11180.2 11270.2 11330.2   11402
    46.7      44    45.1    43.8    42.3      41   41.51   40.86    40.7   41.41
   41.71   40.38    40.3   42.32   43.53   43.83   44.88    45.1    45.1   45.12
   45.06   44.98   44.01   42.46   41.13   41.11   44.11   45.91   46.21    41.2
    42.6    41.5    42.6      43    44.8    42.7    44.6    43.7    48.3    48.3
   46.94   44.26   45.77   44.18   45.14   43.72   43.31    45.7   45.81   47.41
   47.37   44.74   44.85   45.62   43.76   45.32    43.9   43.93   45.41   48.64
    46.7      44    45.1    43.8    42.3      41    41.5    38.6    38.8    41.4
    41.7    38.2   38.16    37.8   42.76   39.53    40.7    42.3    43.2   43.22
   43.44   40.67   41.43    42.1    40.6    41.1    44.1    45.9    46.2    41.2
    42.6    41.5    42.6      43    44.8    42.7    44.6    43.7    48.3    48.3
   46.94   44.26   45.77   44.18   45.14   43.72   43.31    45.7   45.81   47.41
   47.37   44.74   44.85   45.62   43.76   45.32    43.9   43.93   45.41   48.64
Pier Skew, UpSta & Num, DnSta & Num=  ,4968.1, 2 ,4968.1, 2 , 0 , 0 , 0 ,,
     1.4     1.4
   32.77   44.21
     1.4     1.4
   32.77   44.21
Pier Skew, UpSta & Num, DnSta & Num=  ,4989.2, 2 ,4989.2, 2 , 0 , 0 , 0 ,,
     1.4     1.4
   28.79   44.19
     1.4     1.4
   28.79   44.19
Pier Skew, UpSta & Num, DnSta & Num=  ,5010.7, 2 ,5010.7, 2 , 0 , 0 , 0 ,,
     1.4     1.4
   26.83   44.18
     1.4     1.4
   26.83   44.18
Pier Skew, UpSta & Num, DnSta & Num=  ,5032.6, 2 ,5032.6, 2 , 0 , 0 , 0 ,,
     1.4     1.4
   33.46   44.17
     1.4     1.4
   33.46   44.17
Abutment Skew #Up #Dn= , 2 , 2
 4944.12 4953.58
    43.2   39.04
 4944.12 4953.58
    43.2   39.04
Abutment Skew #Up #Dn= , 2 , 2
 5047.63 5054.47
   42.52   43.17
 5047.63 5054.47
   42.52   43.17
BR Coef= 1 , 1 , 0 ,1.25, 0 ,,,0.8,0,2,0,
WSPro=,,,, 1 ,,,, 0 ,,,, 0 ,,,,-1 ,-1 ,-1 , 0 , 0 , 0 , 0 , 0
BR U #Sta/Elev= 153
  3407.1    46.7  3422.1    46.5  3542.1      44  3547.1    44.4  3572.1    45.1
  3592.1    45.1  3632.1    43.8  3742.1    42.9  3912.1    42.3  3942.1      41
  3969.4   41.46  3972.1    41.5  3987.1    40.7  3999.4   39.02  4002.5    38.6
  4009.4   38.74  4017.5    38.9  4054.4   38.87  4064.4   38.86  4142.5    38.8
  4167.5    39.7  4187.4    41.4  4207.4    41.4  4217.4    41.7  4222.4    41.6
  4227.4    41.3  4247.4    39.1  4262.4    38.2  4294.4   38.16    4598    37.8
  4669.4   40.17  4684.4   40.66  4729.8   42.17 4747.73   42.76 4766.61   39.53
  4789.1   39.76 4815.46   40.03  4859.8   40.51 4876.77    40.7  4899.4   41.33
  4900.8   41.37 4912.79   41.71 4938.49   42.49  4938.6   42.49 4938.71   42.49
 4943.28   42.63 4944.23    42.3 4944.32   42.27  4950.7   40.04 4953.58   39.04
 4959.21   37.07 4968.13   33.95 4983.89   29.96 4989.18   30.11  4994.2    27.8
 4995.06   25.35 4997.06   25.02  5005.2   25.48  5005.8   27.79 5010.65   27.84
 5012.99   29.19 5024.59   33.21 5032.65   34.58 5047.63   42.52 5049.36   43.44
 5054.27   43.17 5054.38   43.16 5056.99   43.01  5057.1   43.01 5057.21      43
  5098.9   40.67  5124.6   40.93 5154.93   41.24  5179.3   41.35 5200.48   41.44
  5238.4   41.43 5256.34   41.42 5296.86   41.68  5297.8   41.71  5312.2    42.1
  5390.6   41.34  5477.2    40.5  5502.2    40.6  5517.2    41.1  5527.2    41.1
  5599.4   43.57    5615    44.1    5625    45.9    5630    46.1    5640    46.2
  5653.6   45.72    5705    43.9    5810    41.3    5835    41.2    5850    41.6
    5865    42.6    5895    42.7    5940    41.5    5955    41.7    5970    42.6
    6000    42.3  6143.6   42.69    6335    43.2    6345      43    6410    44.8
  6472.5    44.7  6632.5    44.6  6687.5    43.5  6862.5    42.8  6892.5    43.2
  6982.5    42.7  7137.5    43.6  7197.5    42.8  7377.5    43.5  7422.5      44
  7437.5    43.7  7517.5      44  7542.5    44.6  7772.5    43.7  7787.5    44.1
  7907.5    48.3  8014.5    48.3  8118.7   46.94  8178.7   44.26  8334.1   45.77
  8504.1   44.18  8514.1   45.21  8524.1   45.14  8544.1   43.72  8574.1   43.31
  8774.1   44.59  8824.1   44.95  8944.1    45.7  9274.1   45.81  9414.1   47.41
    9460   47.37    9540   44.74    9630   44.63   10030    45.3   10150   44.87
 10610.2   44.94 10620.2   45.26 10670.2   44.85 10720.2   45.62 10880.2   44.67
 10930.2   43.76 11120.2   45.32 11160.2   45.02 11180.2    43.9 11270.2   43.93
 11330.2   45.41 11340.2   46.55   11402   48.64
BR U #Mann= 7
  3407.1      .2  4669.4      .1  4899.4     .07 4943.28    .035 5049.36     .07
  5599.4      .1  6143.6      .2
BR U Banks=4943.28,5049.36
BR D #Sta/Elev= 153
  3407.1    46.7  3422.1    46.5  3542.1      44  3547.1    44.4  3572.1    45.1
  3592.1    45.1  3632.1    43.8  3742.1    42.9  3912.1    42.3  3942.1      41
  3969.4   41.46  3972.1    41.5  3987.1    40.7  3999.4   39.02  4002.5    38.6
  4009.4   38.74  4017.5    38.9  4054.4   38.87  4064.4   38.86  4142.5    38.8
  4167.5    39.7  4187.4    41.4  4207.4    41.4  4217.4    41.7  4222.4    41.6
  4227.4    41.3  4247.4    39.1  4262.4    38.2  4294.4   38.16    4598    37.8
  4669.4   40.17  4684.4   40.66  4729.8   42.17 4747.73   42.76 4766.61   39.53
  4789.1   39.76 4815.46   40.03  4859.8   40.51 4876.77    40.7  4899.4   41.33
  4900.8   41.37 4912.79   41.71 4938.49   42.49  4938.6   42.49 4938.71   42.49
 4943.28   42.63 4944.23    42.3 4944.32   42.27  4950.7   40.04 4953.58   39.04
 4959.21   37.07 4968.13   33.95 4983.89   29.96 4989.18   30.11  4994.2    27.8
 4995.06   25.35 4997.06   25.02  5005.2   25.48  5005.8   27.79 5010.65   27.84
 5012.99   29.19 5024.59   33.21 5032.65   34.58 5047.63   42.52 5049.36   43.44
 5054.27   43.17 5054.38   43.16 5056.99   43.01  5057.1   43.01 5057.21      43
  5098.9   40.67  5124.6   40.93 5154.93   41.24  5179.3   41.35 5200.48   41.44
  5238.4   41.43 5256.34   41.42 5296.86   41.68  5297.8   41.71  5312.2    42.1
  5390.6   41.34  5477.2    40.5  5502.2    40.6  5517.2    41.1  5527.2    41.1
  5599.4   43.57    5615    44.1    5625    45.9    5630    46.1    5640    46.2
  5653.6   45.72    5705    43.9    5810    41.3    5835    41.2    5850    41.6
    5865    42.6    5895    42.7    5940    41.5    5955    41.7    5970    42.6
    6000    42.3  6143.6   42.69    6335    43.2    6345      43    6410    44.8
  6472.5    44.7  6632.5    44.6  6687.5    43.5  6862.5    42.8  6892.5    43.2
  6982.5    42.7  7137.5    43.6  7197.5    42.8  7377.5    43.5  7422.5      44
  7437.5    43.7  7517.5      44  7542.5    44.6  7772.5    43.7  7787.5    44.1
  7907.5    48.3  8014.5    48.3  8118.7   46.94  8178.7   44.26  8334.1   45.77
  8504.1   44.18  8514.1   45.21  8524.1   45.14  8544.1   43.72  8574.1   43.31
  8774.1   44.59  8824.1   44.95  8944.1    45.7  9274.1   45.81  9414.1   47.41
    9460   47.37    9540   44.74    9630   44.63   10030    45.3   10150   44.87
 10610.2   44.94 10620.2   45.26 10670.2   44.85 10720.2   45.62 10880.2   44.67
 10930.2   43.76 11120.2   45.32 11160.2   45.02 11180.2    43.9 11270.2   43.93
 11330.2   45.41 11340.2   46.55   11402   48.64
BR D #Mann= 7
  3407.1      .2  4669.4      .1  4899.4     .07 4943.28    .035 5049.36     .07
  5599.4      .1  6143.6      .2
BR D Banks=4943.28,5049.36
BC Design=,, 0 ,, 0 ,,,,,,
BC HTab HWMax=48.69
BC Use User HTab Curves=0
BC User HTab FreeFlow(D)= 0

Type RM Length L Ch R = 1 ,64366.5 ,59.7,59.7,59.7
BEGIN DESCRIPTION:
Downstream Section of Bridge/Culvert/Weir
END DESCRIPTION:
XS GIS Cut Line= 6
      3138924.75     13861845.62      3138952.49     13861265.29
      3140301.15     13860333.28      3140366.92      13859495.2
      3140665.94     13857735.76      3141288.53     13854650.55
#Sta/Elev= 30
  3407.1   46.79  3972.1   41.59  4002.5   38.69  4217.4   41.79  4262.4   38.29
    4598   37.89  4669.4   40.26 4747.73   42.85 4766.61   39.62  4899.4   41.42
 4943.28   42.72 4989.18    30.2 4997.06   25.11 5032.65   34.67 5049.36   43.53
  5098.9   40.76  5477.2   40.59  5599.4   43.66    5640   46.29    5810   41.39
  6143.6   42.78    6410   44.89  7772.5   43.79  7907.5   48.39  8178.7   44.35
  8574.1    43.4  9414.1    47.5    9540   44.83 11270.2   44.02   11402   48.73
#Mann= 7 , 1 , 0
  3407.1      .2       0  4669.4      .1       0  4899.4     .07       0
 4943.28    .035       0 5049.36     .07       0  5599.4      .1       0
  6143.6      .2       0
#XS Ineff= 2 , 0
       0    4030    45.5    5980       0    45.5
Permanent Ineff=
       F       F
Bank Sta=4943.28,5049.36
XS Rating Curve= 0 ,0
Exp/Cntr=0.5,0.3

Type RM Length L Ch R = 1 ,64306.8 ,23,23,23
BEGIN DESCRIPTION:
Upstream Section of Bridge/Culvert/Weir
END DESCRIPTION:
XS GIS Cut Line= 6
      3139210.26     13861683.02       3139230.5     13861123.28
        3139729.     13860787.63      3140356.85     13860332.98
      3140703.93     13858234.23        3141352.     13854630.87
#Sta/Elev= 30
  3695.5   46.41  3820.5   41.61  4695.5   40.54  4895.5   39.85 4950.21   39.72
 4956.53    40.3 4960.86   34.48 4989.26   29.59 4989.69   26.76 4991.25   25.68
 5009.61   26.78 5020.78   32.48 5034.38   32.88  5040.7   36.15  5100.5   39.57
  5247.9   41.91  5711.8   40.71  5746.8   41.91  5781.8   46.51  6026.8   41.01
  6216.2    42.8  7576.8   43.21  7801.8   44.71  7881.2   51.01  7961.5   47.99
  8481.5   43.61  9473.8    45.8 10763.8   45.67 11233.8    43.4 11420.2   48.63
#Mann= 7 , 1 , 0
  3695.5      .2       0  4695.5      .1       0  4895.5     .07       0
 4950.21    .035       0  5040.7     .07       0  5100.5      .1       0
  6216.2      .2       0
#XS Ineff= 2 , 0
       0    3930    45.6    6080       0    45.6
Permanent Ineff=
       F       F
Bank Sta=4950.21,5040.7
XS Rating Curve= 0 ,0
Exp/Cntr=0.5,0.3

Type RM Length L Ch R = 3 ,64295.3 ,,,
BEGIN DESCRIPTION:
Pipeline - Skewed 30 Degrees
END DESCRIPTION:
Bridge Culvert--1,0,-1,-1, 0
Deck Dist Width WeirC Skew NumUp NumDn MinLoCord MaxHiCord MaxSubmerge Is_Ogee
10,3,2.6,0, 60, 60, , , 0.95, 0, 1,1,,
  3695.5  3735.5  3820.5  4030.5  4060.5  4190.5  4255.6  4420.6 4833.73 4842.13
  4895.3 4896.86  4906.8 4909.93 4910.02 5088.57 5088.68  5090.1  5102.4 5110.33
 5143.84 5195.89  5247.9  5631.8  5711.8  5746.8  5771.8  5781.8  5981.8  6026.8
  6226.8  6371.8  7111.8  7546.8  7576.8  7801.8  7836.8  7861.8  7881.2  7961.5
  8001.5  8481.5  8521.5  8861.5  8931.5  9473.8  9663.8 10163.8 10183.8 10253.8
 10523.8 10553.8 10763.8 10893.8 11163.8 11183.8 11233.8 11283.8 11353.8 11420.2
    46.5      44    41.7    42.6      42    42.3    40.9    41.7   40.09   41.07
    39.8   41.33   45.26   45.26   45.26   45.21   45.21   45.21   40.83   39.71
   40.52   40.39      42    41.7    40.8      42      46    46.6    43.4    41.1
    43.1    42.2    43.9    44.2    43.3    44.8    47.3    50.3    51.1   48.08
   48.27    43.7   45.11   45.42   44.14   45.89   44.66   44.85    44.3    45.2
    44.9   44.21   45.76    44.1    44.7   43.53   43.49   43.66   46.77   48.72
    46.5      44    41.7    42.6      42    42.3    40.9    41.7   40.09   41.07
    39.8   40.92   41.09   41.12   42.26   42.21    40.3      40   39.67   39.71
   40.52   40.39      42    41.7    40.8      42      46    46.6    43.4    41.1
    43.1    42.2    43.9    44.2    43.3    44.8    47.3    50.3    51.1   48.08
   48.27    43.7   45.11   45.42   44.14   45.89   44.66   44.85    44.3    45.2
    44.9   44.21   45.76    44.1    44.7   43.53   43.49   43.66   46.77   48.72
  3695.5  3735.5  3820.5  4030.5  4060.5  4190.5  4255.6  4420.6 4833.73 4842.13
  4895.3 4896.86  4906.8 4909.93 4910.02 5088.57 5088.68  5090.1  5102.4 5110.33
 5143.84 5195.89  5247.9  5631.8  5711.8  5746.8  5771.8  5781.8  5981.8  6026.8
  6226.8  6371.8  7111.8  7546.8  7576.8  7801.8  7836.8  7861.8  7881.2  7961.5
  8001.5  8481.5  8521.5  8861.5  8931.5  9473.8  9663.8 10163.8 10183.8 10253.8
 10523.8 10553.8 10763.8 10893.8 11163.8 11183.8 11233.8 11283.8 11353.8 11420.2
    46.5      44    41.7    42.6      42    42.3    40.9    41.7   40.09   41.07
    39.8   41.33   45.26   45.26   45.26   45.21   45.21   45.21   40.83   39.71
   40.52   40.39      42    41.7    40.8      42      46    46.6    43.4    41.1
    43.1    42.2    43.9    44.2    43.3    44.8    47.3    50.3    51.1   48.08
   48.27    43.7   45.11   45.42   44.14   45.89   44.66   44.85    44.3    45.2
    44.9   44.21   45.76    44.1    44.7   43.53   43.49   43.66   46.77   48.72
    46.5      44    41.7    42.6      42    42.3    40.9    41.7   40.09   41.07
    39.8   40.92   41.09   41.12   42.26   42.21    40.3      40   39.67   39.71
   40.52   40.39      42    41.7    40.8      42      46    46.6    43.4    41.1
    43.1    42.2    43.9    44.2    43.3    44.8    47.3    50.3    51.1   48.08
   48.27    43.7   45.11   45.42   44.14   45.89   44.66   44.85    44.3    45.2
    44.9   44.21   45.76    44.1    44.7   43.53   43.49   43.66   46.77   48.72
BR Coef= 1 , 1 , 0 ,1.25, 0 ,,,0.8,0,2,0,
WSPro=,,,, 1 ,,,, 0 ,,,, 0 ,,,,-1 ,-1 ,-1 , 0 , 0 , 0 , 0 , 0
BR U #Sta/Elev= 118
  3695.5    46.5  3705.5    46.3  3720.5    44.9  3735.5      44  3820.5    41.7
  3825.5    42.1  4030.5    42.6  4060.5      42  4190.5    42.3  4255.6    40.9
  4315.6    40.9  4420.6    41.7  4695.5   40.63 4833.73   40.09 4842.13   41.07
 4868.71   40.26 4880.84   40.33  4895.3    39.8  4895.5   39.94  4896.1   40.37
 4896.86   40.92 4901.02   41.04  4906.8   41.09 4909.93   41.12 4910.02   41.12
 4917.04   41.18 4934.36   40.23 4950.21   39.81 4951.16   40.15 4956.53   40.39
 4960.86   34.57 4978.18   31.55 4989.26   29.68 4989.69   26.85 4991.25   25.77
 5009.61   26.87 5010.74   28.97 5020.78   32.57 5034.38   32.97  5040.7   36.24
 5063.91   38.73 5078.72   39.67 5087.73    40.5 5088.57   40.32 5088.68    40.3
  5090.1      40 5091.97   39.61  5100.5   39.66  5102.4   39.67 5110.33   39.71
 5127.22   40.28 5133.54   40.41 5143.84   40.52 5186.54   40.37 5195.89   40.39
  5247.9      42  5631.8    41.7  5681.8    41.3  5696.8    40.7  5711.8    40.8
  5726.8    41.5  5741.8    41.7  5746.8      42  5756.8    43.4  5771.8      46
  5781.8    46.6  5981.8    43.4  6011.8    41.7  6026.8    41.1  6041.8    41.1
  6056.8    41.8  6086.8    41.5  6101.8    42.2  6176.8    42.1  6216.2   42.89
  6226.8    43.1  6371.8    42.2  6616.8    42.9  6631.8    42.7  7066.8    43.7
  7081.8    43.4  7111.8    43.9  7506.8    43.8  7546.8    44.2  7576.8    43.3
  7801.8    44.8  7816.8    45.6  7836.8    47.3  7861.8    50.3  7881.2    51.1
  7961.5   48.08  7981.5   47.87  8001.5   48.27  8471.5      44  8481.5    43.7
  8521.5   45.11  8831.5   44.92  8861.5   45.42  8931.5   44.14  9443.8   45.35
  9473.8   45.89  9663.8   44.66 10163.8   44.85 10183.8    44.3 10253.8    45.2
 10273.8   44.71 10523.8    44.9 10553.8   44.21 10763.8   45.76 10893.8    44.1
 11163.8    44.7 11183.8   43.53 11233.8   43.49 11273.8   43.96 11283.8   43.66
 11353.8   46.77 11413.8   48.76 11420.2   48.72
BR U #Mann= 7
  3695.5      .2  4695.5      .1  4895.5     .07 4950.21     .04  5040.7     .07
  5100.5      .1  6216.2      .2
BR U Banks=4950.21,5040.7
BR D #Sta/Elev= 118
  3695.5    46.5  3705.5    46.3  3720.5    44.9  3735.5      44  3820.5    41.7
  3825.5    42.1  4030.5    42.6  4060.5      42  4190.5    42.3  4255.6    40.9
  4315.6    40.9  4420.6    41.7  4695.5   40.63 4833.73   40.09 4842.13   41.07
 4868.71   40.26 4880.84   40.33  4895.3    39.8  4895.5   39.94  4896.1   40.37
 4896.86   40.92 4901.02   41.04  4906.8   41.09 4909.93   41.12 4910.02   41.12
 4917.04   41.18 4934.36   40.23 4950.21   39.81 4951.16   40.15 4956.53   40.39
 4960.86   34.57 4978.18   31.55 4989.26   29.68 4989.69   26.85 4991.25   25.77
 5009.61   26.87 5010.74   28.97 5020.78   32.57 5034.38   32.97  5040.7   36.24
 5063.91   38.73 5078.72   39.67 5087.73    40.5 5088.57   40.32 5088.68    40.3
  5090.1      40 5091.97   39.61  5100.5   39.66  5102.4   39.67 5110.33   39.71
 5127.22   40.28 5133.54   40.41 5143.84   40.52 5186.54   40.37 5195.89   40.39
  5247.9      42  5631.8    41.7  5681.8    41.3  5696.8    40.7  5711.8    40.8
  5726.8    41.5  5741.8    41.7  5746.8      42  5756.8    43.4  5771.8      46
  5781.8    46.6  5981.8    43.4  6011.8    41.7  6026.8    41.1  6041.8    41.1
  6056.8    41.8  6086.8    41.5  6101.8    42.2  6176.8    42.1  6216.2   42.89
  6226.8    43.1  6371.8    42.2  6616.8    42.9  6631.8    42.7  7066.8    43.7
  7081.8    43.4  7111.8    43.9  7506.8    43.8  7546.8    44.2  7576.8    43.3
  7801.8    44.8  7816.8    45.6  7836.8    47.3  7861.8    50.3  7881.2    51.1
  7961.5   48.08  7981.5   47.87  8001.5   48.27  8471.5      44  8481.5    43.7
  8521.5   45.11  8831.5   44.92  8861.5   45.42  8931.5   44.14  9443.8   45.35
  9473.8   45.89  9663.8   44.66 10163.8   44.85 10183.8    44.3 10253.8    45.2
 10273.8   44.71 10523.8    44.9 10553.8   44.21 10763.8   45.76 10893.8    44.1
 11163.8    44.7 11183.8   43.53 11233.8   43.49 11273.8   43.96 11283.8   43.66
 11353.8   46.77 11413.8   48.76 11420.2   48.72
BR D #Mann= 7
  3695.5      .2  4695.5      .1  4895.5     .07 4950.21     .04  5040.7     .07
  5100.5      .1  6216.2      .2
BR D Banks=4950.21,5040.7
BC Design=,, 0 ,, 0 ,,,,,,
BC HTab HWMax=51.01
BC Use User HTab Curves=0
BC User HTab FreeFlow(D)= 0

Type RM Length L Ch R = 1 ,64283.8 ,1042.7,1042.7,1042.7
BEGIN DESCRIPTION:
Downstream Section of Bridge/Culvert/Weir
END DESCRIPTION:
XS GIS Cut Line= 6
      3139232.18       13861690.      3139252.42     13861130.26
      3139750.92     13860794.61      3140378.77     13860339.96
      3140725.85     13858241.21      3141373.92     13854637.85
#Sta/Elev= 30
  3695.5    46.5  3820.5    41.7  4695.5   40.63  4895.5   39.94 4950.21   39.81
 4956.53   40.39 4960.86   34.57 4989.26   29.68 4989.69   26.85 4991.25   25.77
 5009.61   26.87 5020.78   32.57 5034.38   32.97  5040.7   36.24  5100.5   39.66
  5247.9      42  5711.8    40.8  5746.8      42  5781.8    46.6  6026.8    41.1
  6216.2   42.89  7576.8    43.3  7801.8    44.8  7881.2    51.1  7961.5   48.08
  8481.5    43.7  9473.8   45.89 10763.8   45.76 11233.8   43.49 11420.2   48.72
#Mann= 7 , 1 , 0
  3695.5      .2       0  4695.5      .1       0  4895.5     .07       0
 4950.21    .035       0  5040.7     .07       0  5100.5      .1       0
  6216.2      .2       0
#XS Ineff= 2 , 0
       0    3930    45.6    6080       0    45.6
Permanent Ineff=
       F       F
Bank Sta=4950.21,5040.7
XS Rating Curve= 0 ,0
Exp/Cntr=0.5,0.3

Type RM Length L Ch R = 1 ,63241.1 ,110,114.9,91
BEGIN DESCRIPTION:
Cross Section 63241.1
END DESCRIPTION:
XS GIS Cut Line= 6
      3137460.97     13863780.47       3140064.8     13861841.84
      3140644.16      13861076.6      3140593.95     13859712.41
      3140772.05     13858250.47      3141424.03     13854804.53
#Sta/Elev= 30
   370.9   48.04  3374.9   43.59  4187.6   39.39  4349.7   41.44  4487.6   46.54
    4541   42.53  4899.7   41.67  4911.1    40.6  4945.2   30.56  4982.9   25.83
  5017.8   26.04  5071.5   41.18  5099.7   41.26  5323.2   42.07  5615.3   42.14
  5655.3   45.01  5715.3   57.93  5845.4   60.17  5895.4   56.88  5945.4   43.42
  6219.7   42.84  8228.1   45.68  8438.1   43.99  8618.1   46.35  9058.9   44.83
  9298.9   48.89  9395.1   48.02  9435.1   44.91 10785.1   44.02 10925.8    48.4
#Mann= 8 , 1 , 0
   370.9      .2       0  4349.7      .1       0  4899.7     .07       0
  4911.1    .035       0  5071.5     .07       0  5099.7      .1       0
  5323.2      .1       0  6219.7      .2       0
#XS Ineff= 2 , 0
       0  4487.6   46.54    9290       0    48.9
Permanent Ineff=
       F       F
Bank Sta=4911.1,5071.5
XS Rating Curve= 0 ,0
Exp/Cntr=0.5,0.3

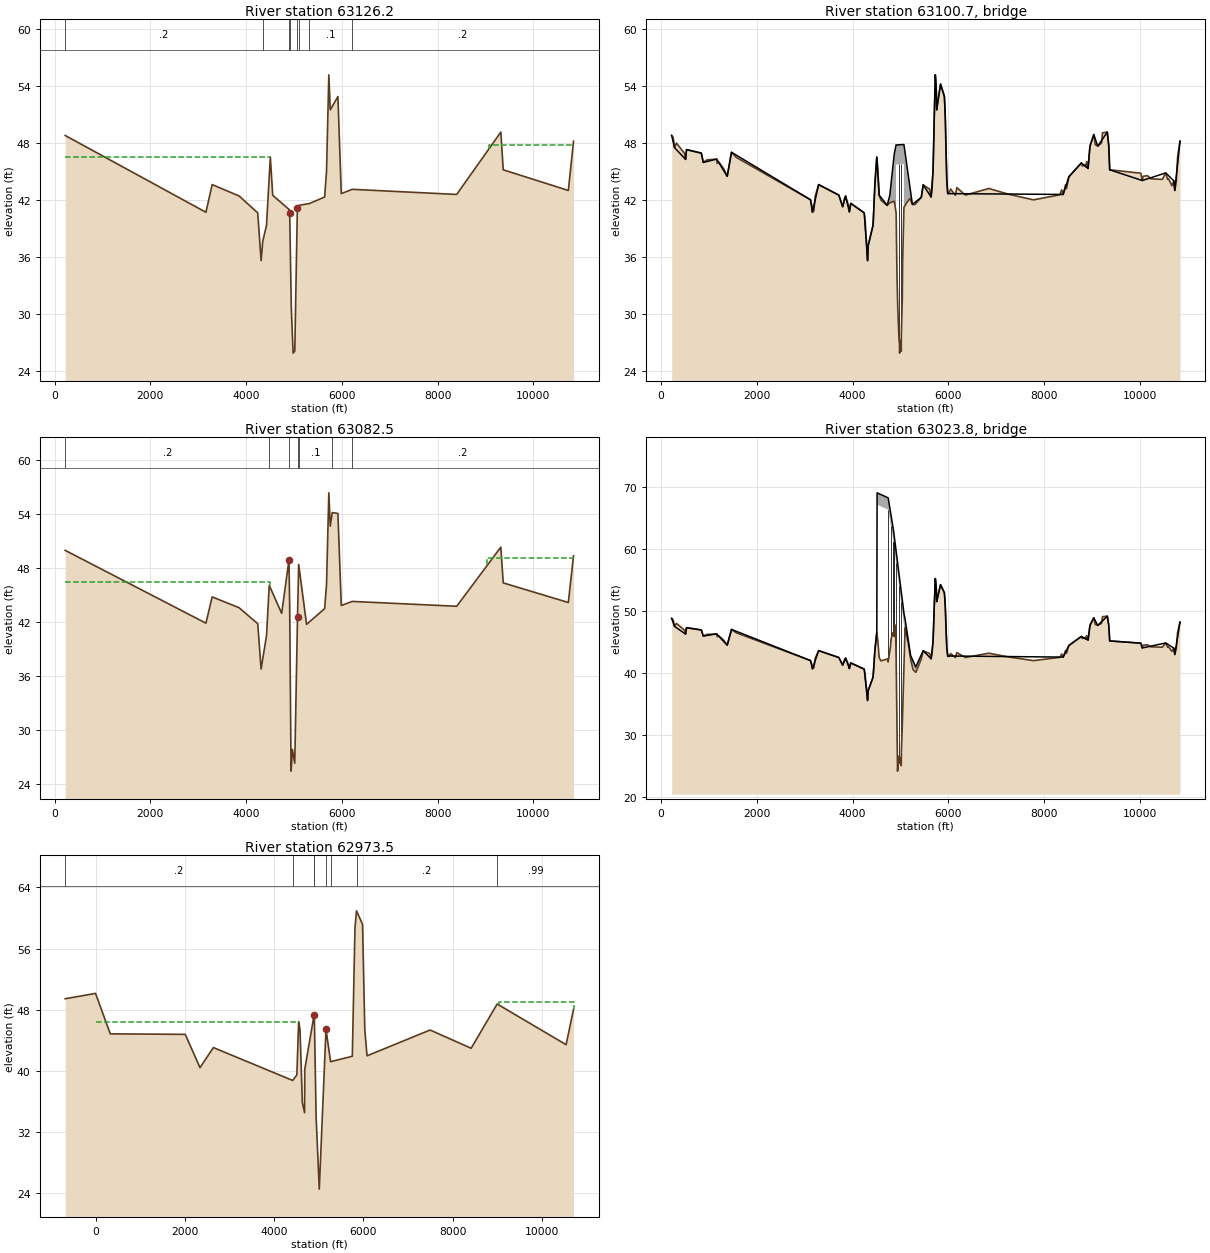
Type RM Length L Ch R = 1 ,63126.2 ,43.7,43.7,43.7
BEGIN DESCRIPTION:
Upstream Section of Bridge/Culvert/Weir
END DESCRIPTION:
XS GIS Cut Line= 6
      3140396.14     13865314.72       3140510.4     13861913.26
      3140823.41     13861148.94      3140851.38     13859689.55
      3140940.43     13858309.24      3141584.75     13854821.48
#Sta/Elev= 30
   221.7    48.8  3161.7    40.7  3291.7   43.62  3853.8   42.42  4243.8   40.64
  4313.8    35.6  4349.7   37.67  4426.8    39.3  4506.8   46.53  4556.8   42.49
  4899.7   40.99  4911.1   40.61  4945.2   30.57  4982.9   25.84  5017.8   26.05
  5071.5   41.19  5099.7   41.43  5323.2   41.62  5641.1   42.31  5681.1   45.04
  5728.9    55.2  5758.9    51.5  5918.9   52.91  5988.9   42.67  6219.7   43.12
    8400   42.58  9322.3   49.16  9372.3   45.18 10732.3      43 10840.9    48.2
#Mann= 8 , 1 , 0
   221.7      .2       0  4349.7      .1       0  4899.7     .07       0
  4911.1    .035       0  5071.5     .07       0  5099.7      .1       0
  5323.2      .1       0  6219.7      .2       0
#XS Ineff= 2 , 0
       0    4507   46.53    9067       0    47.8
Permanent Ineff=
       F       F
Bank Sta=4911.1,5071.5
XS Rating Curve= 0 ,0
Exp/Cntr=0.5,0.3

Type RM Length L Ch R = 3 ,63100.7 ,,,
BEGIN DESCRIPTION:
HOMESTEAD ROAD S RAMP
Structure ID: H00-51,,,,
END DESCRIPTION:
Bridge Culvert--1,0,-1,-1, 0
Deck Dist Width WeirC Skew NumUp NumDn MinLoCord MaxHiCord MaxSubmerge Is_Ogee
10,31,2.6,0, 60, 60, , , 0.95, 0, 1,1,,
   221.7   281.7   511.7   531.7   841.7   881.7  1161.7  1381.7  1471.7  3121.7
  3161.7  3291.7  3713.8  3793.8  3853.8  3933.8  3963.8  4243.8  4313.8  4326.8
  4426.8  4466.8  4506.8  4556.8    4724  4777.1  4872.4 4907.91    4908  4909.3
 5073.59  5073.7  5250.2  5435.9  5475.9  5641.1  5681.1  5728.9  5748.9  5758.9
  5838.9  5918.9  5938.9  5968.9  5988.9    8400    8520    8780    8920    8960
    9040  9122.3  9322.3  9352.3  9372.3 10052.3 10542.3 10712.3 10732.3 10840.9
    48.8   47.52   46.28   47.31   46.94   45.96   46.31   44.49   47.03   42.02
    40.7   43.62   42.51   41.28   42.42   40.74   41.64   40.64    35.6   37.19
    39.3   43.66   46.53    42.5   41.43   42.45   46.88   47.77   47.77    47.8
   47.85   47.85   41.53   42.27   43.59   42.31   45.04    55.2   53.68    51.5
   54.22   52.91   50.49   44.09   42.67   42.58   44.45    45.9   45.32   47.68
    48.9   47.68   49.16   47.73   45.18   44.05   44.85   44.02      43    48.2
    48.8   47.52   46.28   47.31   46.94   45.96   46.31   44.49   47.03   42.02
    40.7   43.62   42.51   41.28   42.42   40.74   41.64   40.64    35.6   37.19
    39.3   43.66   46.53   42.49   41.42   41.69   41.87   40.72    45.7   45.73
   45.78   41.21   41.52   42.27   43.59   42.31   45.04    55.2   53.68    51.5
   54.22   52.91   50.49   44.09   42.67   42.58   44.45    45.9   45.32   47.68
    48.9   47.68   49.16   47.73   45.18   44.05   44.85   44.02      43    48.2
   221.7   281.7   511.7   531.7   841.7   881.7  1161.7  1381.7  1471.7  3121.7
  3161.7  3291.7  3713.8  3793.8  3853.8  3933.8  3963.8  4243.8  4313.8  4326.8
  4426.8  4466.8  4506.8  4556.8    4724  4777.1  4872.4 4907.91    4908  4909.3
 5073.59  5073.7  5250.2  5435.9  5475.9  5641.1  5681.1  5728.9  5748.9  5758.9
  5838.9  5918.9  5938.9  5968.9  5988.9    8400    8520    8780    8920    8960
    9040  9122.3  9322.3  9352.3  9372.3 10052.3 10542.3 10712.3 10732.3 10840.9
    48.8   47.52   46.28   47.31   46.94   45.96   46.31   44.49   47.03   42.02
    40.7   43.62   42.51   41.28   42.42   40.74   41.64   40.64    35.6   37.19
    39.3   43.66   46.53    42.5   41.43   42.45   46.88   47.77   47.77    47.8
   47.85   47.85   41.53   42.27   43.59   42.31   45.04    55.2   53.68    51.5
   54.22   52.91   50.49   44.09   42.67   42.58   44.45    45.9   45.32   47.68
    48.9   47.68   49.16   47.73   45.18   44.05   44.85   44.02      43    48.2
   48.72   47.44    46.2   47.23   46.86   45.88   46.23   44.41   46.95   41.94
   40.62   43.54   42.43    41.2   42.34   40.66   41.56   40.56   35.52   37.11
   39.22   43.58   46.45   42.41   41.34   41.61   41.79   40.64   45.62   45.65
    45.7   41.13   41.44   42.19   43.51   42.23   44.96   55.12    53.6   51.42
   54.14   52.83   50.41   44.01   42.59    42.5   44.37   45.82   45.24    47.6
   48.82    47.6   49.08   47.65    45.1   43.97   44.77   43.94   42.92   48.12
Pier Skew, UpSta & Num, DnSta & Num=  ,4971.9, 2 ,4971.9, 2 , 0 , 0 , 0 ,,
       3       3
   26.11    46.7
       3       3
   26.03   46.62
Pier Skew, UpSta & Num, DnSta & Num=  ,5012.7, 2 ,5012.7, 2 , 0 , 0 , 0 ,,
       3       3
   25.86   46.62
       3       3
   25.78   46.54
Abutment Skew #Up #Dn= , 2 , 2
  5070.4 5073.79
   40.93   45.78
  5070.4 5073.79
   40.85    45.7
BR Coef= 1 , 1 , 0 ,1.25, 0 ,,,0.8,0,2,0,
WSPro=,,,, 1 ,,,, 0 ,,,, 0 ,,,,-1 ,-1 ,-1 , 0 , 0 , 0 , 0 , 0
BR U #Sta/Elev= 169
   221.7    48.8   251.7    48.6   281.7   47.52   321.7      48   491.7    46.9
   511.7   46.28   531.7   47.31   841.7   46.94   881.7   45.96   961.7   46.23
  1161.7   46.31  1171.7   45.86  1211.7   45.97  1311.7   45.27  1381.7   44.49
  1471.7   47.03  1571.7   46.49  3121.7   42.02  3151.7   41.38  3161.7    40.7
  3191.7   40.83  3221.7   42.42  3291.7   43.62  3713.8   42.51  3793.8   41.28
  3833.8   42.21  3843.8   42.04  3853.8   42.42  3923.8   41.28  3933.8   40.74
  3963.8   41.64  4243.8   40.64  4263.8   39.85  4283.8   38.02  4293.8   37.52
  4313.8    35.6  4323.8   36.92  4326.8   37.19  4349.7   37.67  4426.8    39.3
  4436.8   39.87  4466.8   43.66  4506.8   46.53  4526.8   45.34  4549.7   43.16
  4556.8   42.49  4589.7   42.04  4594.6   41.97  4609.7   41.91  4709.7   41.48
  4714.1   41.46    4724   41.42 4775.59   41.68  4775.7   41.68 4775.81   41.68
  4777.1   41.69  4779.3    41.7  4844.4   41.82  4872.4   41.87  4899.7   40.99
 4907.91   40.72    4908   40.72  4908.1   40.71  4909.3   40.68  4910.1   40.65
  4911.1   40.61  4927.7   34.29  4945.2   30.57  4967.3   27.63  4971.9   27.16
  4974.9   27.06  4981.3   26.84  4982.9   25.84  5007.4   27.16  5012.7   27.19
  5015.1   26.66  5017.8   26.05  5018.6   27.53  5039.5   31.62  5046.8   35.48
  5064.1   39.48  5070.3   40.91  5070.4   40.93  5071.5   41.19 5073.59   41.21
  5073.7   41.21  5073.8   41.21  5099.7   41.43  5116.5   41.58  5128.7   41.68
 5175.89   41.99    5176   41.99 5176.11   41.99  5191.1   42.08  5201.2   42.15
  5246.3   41.57  5250.2   41.52  5250.3   41.52  5250.8   41.52  5256.7   41.52
  5305.9   41.52  5323.2   41.62  5435.9   42.27  5475.9   43.59  5591.1    43.2
  5611.1   43.15  5641.1   42.31  5661.1    43.1  5681.1   45.04  5688.9   46.33
  5708.9   51.18  5728.9    55.2  5738.9   54.81  5748.9   53.68  5758.9    51.5
  5778.9   52.35  5838.9   54.22  5918.9   52.91  5928.9   52.02  5938.9   50.49
  5948.9      48  5968.9   44.09  5988.9   42.67  6018.9   42.75  6048.9   43.15
  6148.9    42.5  6178.9    43.3  6219.7   43.12  6358.9   42.51  6847.1   43.21
  7247.1   42.62    7780   42.01    8330   42.54    8370   43.07    8400   42.58
    8450    43.6    8470   43.19    8520   44.45    8780    45.9    8800   45.57
    8860   45.72    8870    45.5    8890   46.05    8920   45.32    8960   47.68
    9040    48.9    9070   47.84  9122.3   47.68  9202.3   48.01  9222.3   49.08
  9322.3   49.16  9352.3   47.73  9362.3   46.71  9372.3   45.18 10022.3   44.82
 10052.3   44.05 10072.3    44.5 10162.3   44.56 10232.3   44.23 10472.3   44.17
 10542.3   44.85 10582.3   44.17 10602.3   44.23 10672.3    43.5 10712.3   44.02
 10732.3      43 10762.3   43.96 10792.3   46.59 10840.9    48.2
BR U #Mann= 8
   221.7      .2  4349.7      .1  4899.7     .07  4911.1    .035  5071.5     .07
  5099.7      .1  5323.2      .1  6219.7      .2
BR U Banks=4911.1,5071.5
BR D #Sta/Elev= 169
   221.7   48.72   251.7   48.52   281.7   47.44   321.7   47.92   491.7   46.82
   511.7    46.2   531.7   47.23   841.7   46.86   881.7   45.88   961.7   46.15
  1161.7   46.23  1171.7   45.78  1211.7   45.89  1311.7   45.19  1381.7   44.41
  1471.7   46.95  1571.7   46.41  3121.7   41.94  3151.7    41.3  3161.7   40.62
  3191.7   40.75  3221.7   42.34  3291.7   43.54  3713.8   42.43  3793.8    41.2
  3833.8   42.13  3843.8   41.96  3853.8   42.34  3923.8    41.2  3933.8   40.66
  3963.8   41.56  4243.8   40.56  4263.8   39.77  4283.8   37.94  4293.8   37.44
  4313.8   35.52  4323.8   36.84  4326.8   37.11  4349.7   37.59  4426.8   39.22
  4436.8   39.79  4466.8   43.58  4506.8   46.45  4526.8   45.26  4549.7   43.08
  4556.8   42.41  4589.7   41.96  4594.6   41.89  4609.7   41.83  4709.7    41.4
  4714.1   41.38    4724   41.34 4775.59    41.6  4775.7    41.6 4775.81    41.6
  4777.1   41.61  4779.3   41.62  4844.4   41.74  4872.4   41.79  4899.7   40.91
 4907.91   40.64    4908   40.64  4908.1   40.63  4909.3    40.6  4910.1   40.57
  4911.1   40.53  4927.7   34.21  4945.2   30.49  4967.3   27.55  4971.9   27.08
  4974.9   26.98  4981.3   26.76  4982.9   25.76  5007.4   27.08  5012.7   27.11
  5015.1   26.58  5017.8   25.97  5018.6   27.45  5039.5   31.54  5046.8    35.4
  5064.1    39.4  5070.3   40.83  5070.4   40.85  5071.5   41.11 5073.59   41.13
  5073.7   41.13  5073.8   41.13  5099.7   41.35  5116.5    41.5  5128.7    41.6
 5175.89   41.91    5176   41.91 5176.11   41.91  5191.1      42  5201.2   42.07
  5246.3   41.49  5250.2   41.44  5250.3   41.44  5250.8   41.44  5256.7   41.44
  5305.9   41.44  5323.2   41.54  5435.9   42.19  5475.9   43.51  5591.1   43.12
  5611.1   43.07  5641.1   42.23  5661.1   43.02  5681.1   44.96  5688.9   46.25
  5708.9    51.1  5728.9   55.12  5738.9   54.73  5748.9    53.6  5758.9   51.42
  5778.9   52.27  5838.9   54.14  5918.9   52.83  5928.9   51.94  5938.9   50.41
  5948.9   47.92  5968.9   44.01  5988.9   42.59  6018.9   42.67  6048.9   43.07
  6148.9   42.42  6178.9   43.22  6219.7   43.04  6358.9   42.43  6847.1   43.13
  7247.1   42.54    7780   41.93    8330   42.46    8370   42.99    8400    42.5
    8450   43.52    8470   43.11    8520   44.37    8780   45.82    8800   45.49
    8860   45.64    8870   45.42    8890   45.97    8920   45.24    8960    47.6
    9040   48.82    9070   47.76  9122.3    47.6  9202.3   47.93  9222.3      49
  9322.3   49.08  9352.3   47.65  9362.3   46.63  9372.3    45.1 10022.3   44.74
 10052.3   43.97 10072.3   44.42 10162.3   44.48 10232.3   44.15 10472.3   44.09
 10542.3   44.77 10582.3   44.09 10602.3   44.15 10672.3   43.42 10712.3   43.94
 10732.3   42.92 10762.3   43.88 10792.3   46.51 10840.9   48.12
BR D #Mann= 8
   221.7      .2  4349.7      .1  4899.7     .07  4911.1    .035  5071.5     .07
  5099.7      .1  5323.2      .1  6219.7      .2
BR D Banks=4911.1,5071.5
BC Design=,, 0 ,, 0 ,,,,,,
BC HTab HWMax=55.2
BC Use User HTab Curves=0
BC User HTab FreeFlow(D)= 0

Type RM Length L Ch R = 1 ,63082.5 ,109,109,109
BEGIN DESCRIPTION:
Upstream Section of Bridge/Culvert/Weir
END DESCRIPTION:
XS GIS Cut Line= 6
      3140632.23     13865294.38      3140753.58     13861879.11
      3141002.47     13861025.33       3141010.9       13858356.
      3141245.69     13856798.76      3141657.91     13854772.72
#Sta/Elev= 30
   221.7      50  3161.7    41.9  3291.7   44.82  3853.8   43.62  4243.8   41.84
  4313.8    36.8  4426.8    40.5  4484.2   46.11  4743.8   42.99  4895.8   48.91
  4910.8   43.91  4940.1   25.44  4968.5   27.85  5017.2   26.32  5074.5   42.57
  5099.2   48.43  5264.1   41.77  5641.1   43.51  5681.1   46.24  5728.9    56.4
  5758.9    52.7  5799.7    54.2  5918.9   54.11  5988.9   43.87  6219.2   44.32
    8400   43.78  9322.3   50.36  9372.3   46.38 10732.3    44.2 10840.9    49.4
#Mann= 7 , 1 , 0
   221.7      .2       0  4484.2      .1       0  4895.8    .035       0
  5074.5     .07       0  5099.2      .1       0  5799.7      .2       0
  6219.2      .2       0
#XS Ineff= 2 , 0
       0    4507   46.53    9042       0    49.1
Permanent Ineff=
       F       F
Bank Sta=4895.8,5074.5
XS Rating Curve= 0 ,0
Exp/Cntr=0.5,0.3

Type RM Length L Ch R = 3 ,63023.8 ,,,
BEGIN DESCRIPTION:
HOMESTEAD ROAD
Structure ID: H00-50
END DESCRIPTION:
Bridge Culvert--1,0,-1,-1, 0
Deck Dist Width WeirC Skew NumUp NumDn MinLoCord MaxHiCord MaxSubmerge Is_Ogee
10,97.4,2.6,0, 60, 60, , , 0.95, 0, 1,1,,
   221.7   281.7   511.7   531.7   841.7   881.7  1161.7  1381.7  1471.7  3121.7
  3161.7  3291.7  3713.8  3793.8  3853.8  3933.8  3963.8  4243.8  4313.8  4326.8
  4426.8  4466.8  4506.8  4512.8 4517.71  4517.8  4744.6  4854.9 5076.79  5076.9
  5097.5  5213.3  5320.1  5475.9  5641.1  5681.1  5728.9  5748.9  5758.9  5838.9
  5918.9  5938.9  5968.9  5988.9    8400    8520    8780    8920    8960    9040
  9122.3  9322.3  9352.3  9372.3 10022.3 10052.3 10542.3 10712.3 10732.3 10840.9
    48.8   47.52   46.28   47.31   46.94   45.96   46.31   44.49   47.03   42.02
    40.7   43.62   42.51   41.28   42.42   40.74   41.64   40.64    35.6   37.19
    39.3   43.66   46.53      69   68.98   68.98   68.19   63.03   49.49   49.48
    48.7   42.85   40.98    43.6   42.32   45.05   55.21   53.69   51.51   54.23
   52.92    50.5    44.1   42.76   42.58   44.45    45.9   45.32   47.68    48.9
   47.68   49.16   47.73   45.18   44.82   44.05   44.85   44.02      43    48.2
    48.8   47.52   46.28   47.31   46.94   45.96   46.31   44.49   47.03   42.02
    40.7   43.62   42.51   41.28   42.42   40.74   41.64   40.64    35.6   37.19
    39.3   43.66   46.53   46.17   45.88   67.08   66.29   61.13   47.59   41.99
   47.29   42.23   40.16   43.59   42.31   45.04    55.2   53.68    51.5   54.22
   52.91   50.49   44.09   42.67   42.58   44.45    45.9   45.32   47.68    48.9
   47.68   49.16   47.73   45.18   44.82   44.05   44.85   44.02      43    48.2
   221.7   281.7   511.7   531.7   841.7   881.7  1161.7  1381.7  1471.7  3121.7
  3161.7  3291.7  3713.8  3793.8  3853.8  3933.8  3963.8  4243.8  4313.8  4326.8
  4426.8  4466.8  4506.8  4512.8 4517.71  4517.8  4744.6  4854.9 5076.79  5076.9
  5097.5  5213.3  5320.1  5475.9  5641.1  5681.1  5728.9  5748.9  5758.9  5838.9
  5918.9  5938.9  5968.9  5988.9    8400    8520    8780    8920    8960    9040
  9122.3  9322.3  9352.3  9372.3 10022.3 10052.3 10542.3 10712.3 10732.3 10840.9
   49.02   47.74    46.5   47.53   47.16   46.18   46.53   44.71   47.25   42.24
   40.92   43.84   42.73    41.5   42.64   40.96   41.86   40.86   35.82   37.41
   39.52   43.88   46.75      69   68.98   68.98   68.19   63.03   49.49   49.48
    48.7   42.85   40.98   43.81   42.53   45.26   55.42    53.9   51.72   54.44
   53.13   50.71   44.31   42.89    42.8   44.67   46.12   45.54    47.9   49.12
    47.9   49.38   47.95    45.4   45.04   44.27   45.07   44.24   43.22   48.42
   49.02   47.74    46.5   47.53   47.16   46.18   46.53   44.71   47.25   42.24
   40.92   43.84   42.73    41.5   42.64   40.96   41.86   40.86   35.82   37.41
   39.52   43.88   46.75   46.39    46.1    67.3   66.51   61.35   47.81   42.21
   47.51   42.45   40.38   43.81   42.53   45.26   55.42    53.9   51.72   54.44
   53.13   50.71   44.31   42.89    42.8   44.67   46.12   45.54    47.9   49.12
    47.9   49.38   47.95    45.4   45.04   44.27   45.07   44.24   43.22   48.42
Pier Skew, UpSta & Num, DnSta & Num=  ,4740.6, 2 ,4740.6, 2 , 0 , 0 , 0 ,,
       2       2
   41.14    67.3
       2       2
   41.36   67.52
Pier Skew, UpSta & Num, DnSta & Num=  ,4800.7, 2 ,4800.7, 2 , 0 , 0 , 0 ,,
       2       2
   44.18   64.96
       2       2
    44.4   65.18
Pier Skew, UpSta & Num, DnSta & Num=  ,4855.5, 2 ,4855.5, 2 , 0 , 0 , 0 ,,
       2       2
   45.02   62.15
       2       2
   45.24   62.37
Pier Skew, UpSta & Num, DnSta & Num=  ,4910.8, 2 ,4910.8, 2 , 0 , 0 , 0 ,,
       2       2
   41.08   58.89
       2       2
    41.3   59.11
Pier Skew, UpSta & Num, DnSta & Num=  ,4972.3, 2 ,4972.3, 2 , 0 , 0 , 0 ,,
       2       2
    24.7   55.09
       2       2
   24.92   55.31
Pier Skew, UpSta & Num, DnSta & Num=  ,5013.2, 2 ,5013.2, 2 , 0 , 0 , 0 ,,
       2       2
   24.49   52.56
       2       2
   24.71   52.78
Abutment Skew #Up #Dn= , 2 , 2
  4517.6  4518.8
   67.08   45.82
  4517.6  4518.8
    67.3   46.04
BR Coef= 1 , 1 , 0 ,1.25, 0 ,,,0.8,0,2,0,
WSPro=,,,, 1 ,,,, 0 ,,,, 0 ,,,,-1 ,-1 ,-1 , 0 , 0 , 0 , 0 , 0
BR U #Sta/Elev= 179
   221.7    48.8   251.7    48.6   281.7   47.52   321.7      48   491.7    46.9
   511.7   46.28   531.7   47.31   841.7   46.94   881.7   45.96   961.7   46.23
  1161.7   46.31  1171.7   45.86  1211.7   45.97  1311.7   45.27  1381.7   44.49
  1471.7   47.03  1571.7   46.49  3121.7   42.02  3151.7   41.38  3161.7    40.7
  3191.7   40.83  3221.7   42.42  3291.7   43.62  3713.8   42.51  3793.8   41.28
  3833.8   42.21  3843.8   42.04  3853.8   42.42  3923.8   41.28  3933.8   40.74
  3963.8   41.64  4243.8   40.64  4263.8   39.85  4283.8   38.02  4293.8   37.52
  4313.8    35.6  4323.8   36.92  4326.8   37.19  4426.8    39.3  4436.8   39.87
  4466.8   43.66  4484.2   44.91  4506.8   46.53  4512.8   46.17 4517.71   45.88
  4517.8   45.88  4518.8   45.82  4526.8   45.34  4556.8   42.49  4594.6   41.97
  4740.6    42.3  4743.8   41.79  4744.6   41.83  4794.6   44.37  4800.7   45.34
  4803.3   45.42  4837.5   46.48  4854.9   46.01  4855.5   45.99  4879.7    47.6
  4895.8   47.71  4905.3   44.54  4910.8   42.71  4940.1   24.24  4968.5   26.65
  4972.3   25.56    4979   26.53  4984.1   26.46  5008.3   25.97  5013.2   25.61
  5017.2   25.12    5021   27.63    5037   30.96  5074.5   41.37 5074.79   41.44
  5074.9   41.47 5075.01    41.5  5076.7   41.94 5076.79   41.96  5076.9   41.99
    5077   42.01 5081.69   43.22  5081.8   43.25 5081.91   43.28  5096.3   46.98
  5097.5   47.29  5099.2   47.23  5162.2   44.85  5162.4   44.84  5213.3   42.23
  5214.3   42.18  5264.1   40.57  5265.3   40.56  5320.1   40.16  5323.9   40.13
  5359.8   40.79  5435.9   42.27  5475.9   43.59  5591.1    43.2  5611.1   43.15
  5641.1   42.31  5661.1    43.1  5681.1   45.04  5688.9   46.33  5708.9   51.18
  5728.9    55.2  5738.9   54.81  5745.3   54.09  5748.9   53.68  5755.7    52.2
  5758.9    51.5  5760.7   51.58  5770.7      52  5778.9   52.35  5785.7   52.56
  5799.7      53  5800.7   53.03  5815.7    53.5  5820.7   53.65  5830.7   53.96
  5835.7   54.12  5838.9   54.22  5845.7   54.11  5855.7   53.94  5860.7   53.86
  5875.7   53.62  5918.9   52.91  5928.9   52.02  5938.9   50.49  5948.9      48
  5968.9   44.09  5988.9   42.67  6018.9   42.75  6048.9   43.15  6148.9    42.5
  6178.9    43.3  6219.2   43.12  6358.9   42.51  6847.1   43.21  6925.7   43.09
  7247.1   42.62    7780   42.01    8330   42.54    8370   43.07    8400   42.58
    8450    43.6    8470   43.19    8520   44.45    8780    45.9    8800   45.57
    8860   45.72    8870    45.5    8890   46.05    8920   45.32    8960   47.68
    9040    48.9    9070   47.84  9122.3   47.68  9202.3   48.01  9222.3   49.08
  9322.3   49.16  9352.3   47.73  9362.3   46.71  9372.3   45.18 10022.3   44.82
 10052.3   44.05 10072.3    44.5 10162.3   44.56 10232.3   44.23 10472.3   44.17
 10542.3   44.85 10582.3   44.17 10602.3   44.23 10672.3    43.5 10712.3   44.02
 10732.3      43 10762.3   43.96 10792.3   46.59 10840.9    48.2
BR U #Mann= 7
   221.7      .2  4484.2      .1  4895.8    .035  5074.5     .07  5099.2      .1
  5799.7      .2  6219.2      .2
BR U Banks=4895.8,5074.5
BR D #Sta/Elev= 179
   221.7   49.02   251.7   48.82   281.7   47.74   321.7   48.22   491.7   47.12
   511.7    46.5   531.7   47.53   841.7   47.16   881.7   46.18   961.7   46.45
  1161.7   46.53  1171.7   46.08  1211.7   46.19  1311.7   45.49  1381.7   44.71
  1471.7   47.25  1571.7   46.71  3121.7   42.24  3151.7    41.6  3161.7   40.92
  3191.7   41.05  3221.7   42.64  3291.7   43.84  3713.8   42.73  3793.8    41.5
  3833.8   42.43  3843.8   42.26  3853.8   42.64  3923.8    41.5  3933.8   40.96
  3963.8   41.86  4243.8   40.86  4263.8   40.07  4283.8   38.24  4293.8   37.74
  4313.8   35.82  4323.8   37.14  4326.8   37.41  4426.8   39.52  4436.8   40.09
  4466.8   43.88  4484.2   45.13  4506.8   46.75  4512.8   46.39 4517.71    46.1
  4517.8    46.1  4518.8   46.04  4526.8   45.56  4556.8   42.71  4594.6   42.19
  4740.6   42.52  4743.8   42.01  4744.6   42.05  4794.6   44.59  4800.7   45.56
  4803.3   45.64  4837.5    46.7  4854.9   46.23  4855.5   46.21  4879.7   47.82
  4895.8   47.93  4905.3   44.76  4910.8   42.93  4940.1   24.46  4968.5   26.87
  4972.3   25.78    4979   26.75  4984.1   26.68  5008.3   26.19  5013.2   25.83
  5017.2   25.34    5021   27.85    5037   31.18  5074.5   41.59 5074.79   41.66
  5074.9   41.69 5075.01   41.72  5076.7   42.16 5076.79   42.18  5076.9   42.21
    5077   42.23 5081.69   43.44  5081.8   43.47 5081.91    43.5  5096.3    47.2
  5097.5   47.51  5099.2   47.45  5162.2   45.07  5162.4   45.06  5213.3   42.45
  5214.3    42.4  5264.1   40.79  5265.3   40.78  5320.1   40.38  5323.9   40.35
  5359.8   41.01  5435.9   42.49  5475.9   43.81  5591.1   43.42  5611.1   43.37
  5641.1   42.53  5661.1   43.32  5681.1   45.26  5688.9   46.55  5708.9    51.4
  5728.9   55.42  5738.9   55.03  5745.3   54.31  5748.9    53.9  5755.7   52.42
  5758.9   51.72  5760.7    51.8  5770.7   52.22  5778.9   52.57  5785.7   52.78
  5799.7   53.22  5800.7   53.25  5815.7   53.72  5820.7   53.87  5830.7   54.18
  5835.7   54.34  5838.9   54.44  5845.7   54.33  5855.7   54.16  5860.7   54.08
  5875.7   53.84  5918.9   53.13  5928.9   52.24  5938.9   50.71  5948.9   48.22
  5968.9   44.31  5988.9   42.89  6018.9   42.97  6048.9   43.37  6148.9   42.72
  6178.9   43.52  6219.2   43.34  6358.9   42.73  6847.1   43.43  6925.7   43.31
  7247.1   42.84    7780   42.23    8330   42.76    8370   43.29    8400    42.8
    8450   43.82    8470   43.41    8520   44.67    8780   46.12    8800   45.79
    8860   45.94    8870   45.72    8890   46.27    8920   45.54    8960    47.9
    9040   49.12    9070   48.06  9122.3    47.9  9202.3   48.23  9222.3    49.3
  9322.3   49.38  9352.3   47.95  9362.3   46.93  9372.3    45.4 10022.3   45.04
 10052.3   44.27 10072.3   44.72 10162.3   44.78 10232.3   44.45 10472.3   44.39
 10542.3   45.07 10582.3   44.39 10602.3   44.45 10672.3   43.72 10712.3   44.24
 10732.3   43.22 10762.3   44.18 10792.3   46.81 10840.9   48.42
BR D #Mann= 7
   221.7      .2  4484.2      .1  4895.8    .035  5074.5     .07  5099.2      .1
  5799.7      .2  6219.2      .2
BR D Banks=4895.8,5074.5
BC Design=,, 0 ,, 0 ,,,,,,
BC HTab HWMax=56.4
BC Use User HTab Curves=0
BC User HTab FreeFlow(D)= 0

Type RM Length L Ch R = 1 ,62973.5 ,51,51,51
BEGIN DESCRIPTION:
Upstream Section of Bridge/Culvert/Weir
END DESCRIPTION:
XS GIS Cut Line= 6
      3140897.43     13866202.24      3141176.38     13861008.09
       3141158.7      13859775.3      3141126.88     13858667.01
       3141317.4     13856876.61      3141761.93     13854880.41
#Sta/Elev= 30
  -678.7   49.42     1.3   50.12   331.3   44.82  2011.3   44.75  2341.3   40.39
  2641.3   43.02  4418.3   38.71  4511.3   39.44  4551.3   46.41  4581.3   45.43
  4634.8   35.78  4684.8   34.49  4688.4   40.16  4898.3   47.33  4902.4   47.34
  4942.9   33.94  5013.7   24.47  5164.3   45.39  5267.4   41.17  5753.6   41.88
  5813.6   58.73  5848.3   60.94  5983.6   59.16  6033.6   45.37  6083.6   41.94
  7496.3   45.32  8416.3   42.93  8999.3   48.73 10543.8    43.4 10710.2   48.03
#Mann= 8 , 1 , 0
  -678.7      .2       0  4418.3      .1       0  4898.3     .07       0
  4902.4    .035       0  5164.3      .1       0  5267.4      .1       0
  5848.3      .2       0  8999.3     .99       0
#XS Ineff= 2 , 0
       0    4555   46.38    9043       0      49
Permanent Ineff=
       F       F
Bank Sta=4902.4,5164.3
XS Rating Curve= 0 ,0
Exp/Cntr=0.5,0.3