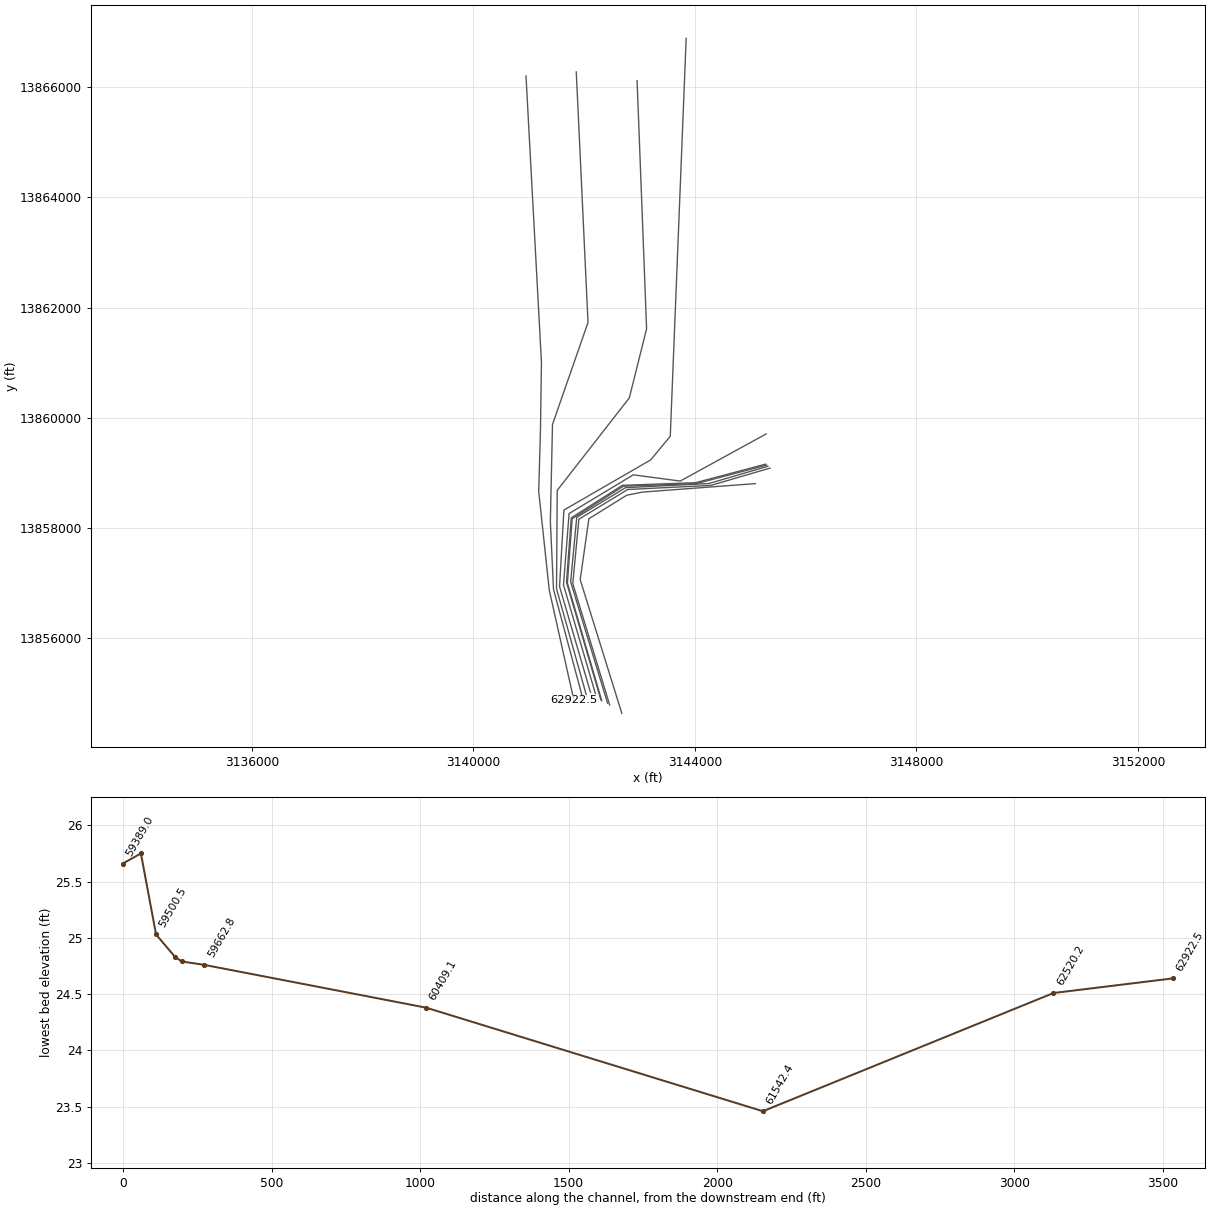
HEC-RAS study H100-00-00.prj: H100-00-00

--- H100-00-00.g01 (geometry) --- (continued)

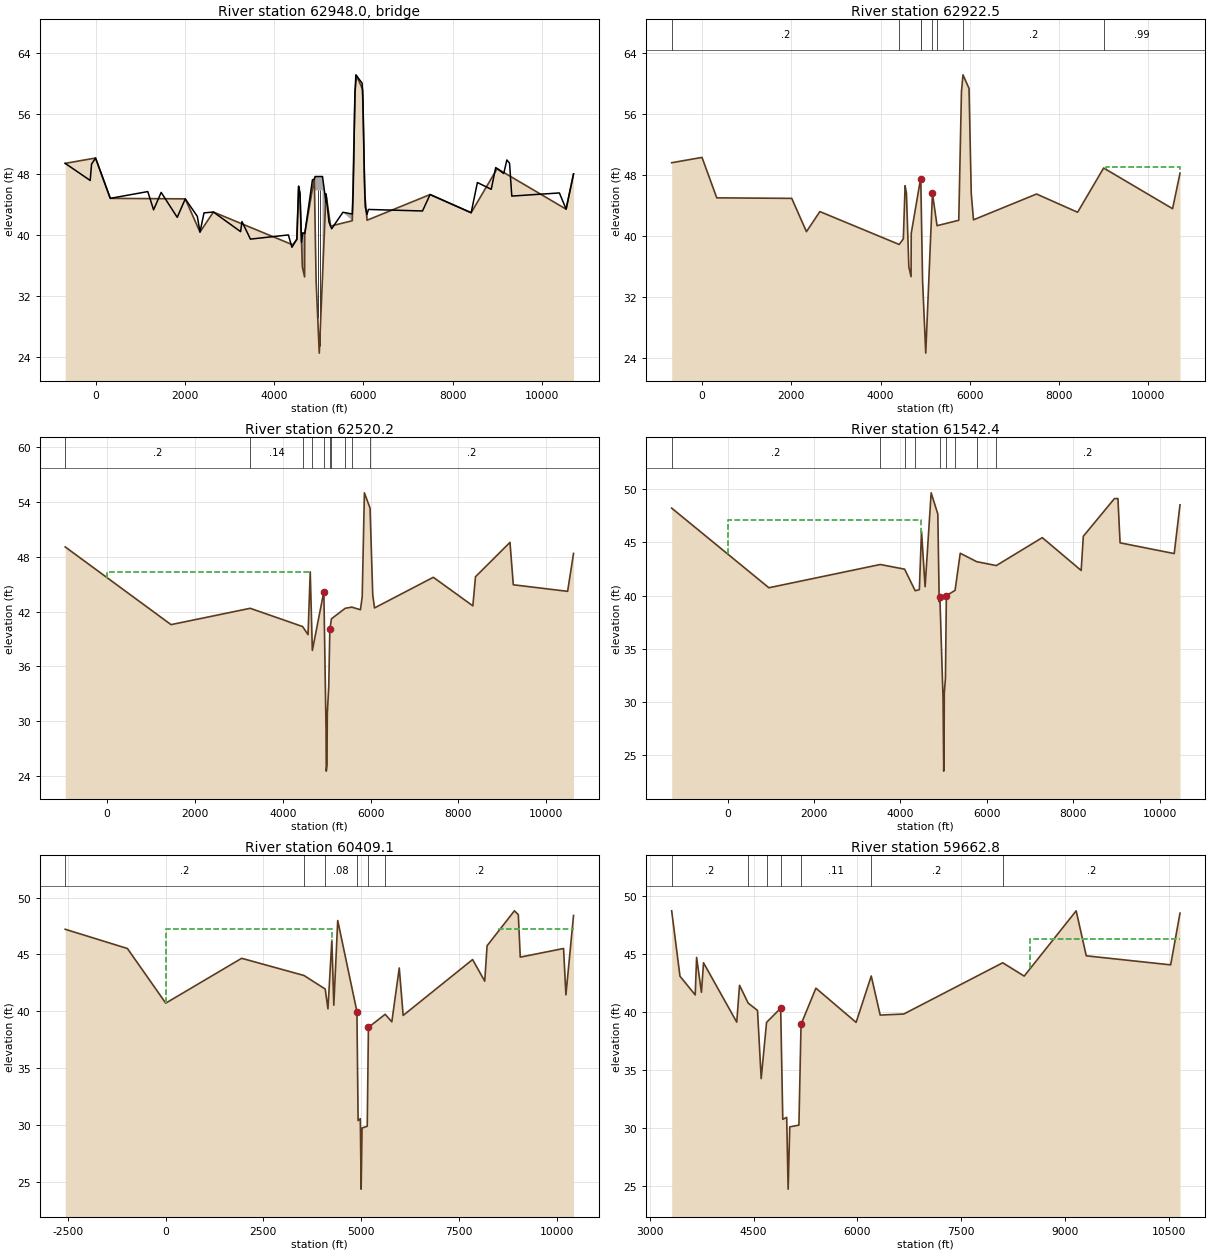
Type RM Length L Ch R = 3 ,62948.0 ,,,
BEGIN DESCRIPTION:
HOMESTEAD ROAD N RAMP
Structure ID: H00-49
END DESCRIPTION:
Bridge Culvert--1,0,-1,-1, 0
Deck Dist Width WeirC Skew NumUp NumDn MinLoCord MaxHiCord MaxSubmerge Is_Ogee
10,31,2.6,0, 60, 60, , , 0.95, 0, 1,1,,
  -678.7  -118.7   -88.7     1.3   331.3  1171.3  1301.3  1471.3  1831.3  2011.3
  2281.3  2341.3  2431.3  2641.3  3251.3  3281.3  3471.3  4321.3  4401.3  4511.3
  4551.3  4581.3  4614.8  4644.8  4684.8  4688.4  4860.4  4902.4 4920.11  4920.2
 5085.49  5085.6  5163.6  5164.3  5231.2  5291.1  5543.6  5753.6  5773.6  5813.6
  5833.6  5973.6  5993.6  6023.6  6043.6  6083.6  6113.6  7326.3  7496.3  8416.3
  8556.3  8866.3  8966.3  9146.3  9216.3  9276.7  9326.7 10393.8 10543.8 10710.2
   49.46   47.21   49.36   50.16   44.86   45.75   43.35   45.64   42.36   44.79
   42.49   40.43   42.95   43.06   40.48   41.81    39.5   40.05   38.43   39.48
   46.45   45.47   39.07   40.34   40.24   40.23   47.29   47.38   47.73   47.73
   47.73   47.73   44.35   45.43   41.74   40.86   43.03    42.8    45.7   58.77
    61.1      60   57.73   47.89   43.74   42.74    43.4    43.2   45.36   42.97
   46.94   46.05   48.91   48.12   49.91   49.48   45.16   45.57   43.44   48.07
   49.46   47.21   49.36   50.16   44.86   45.75   43.35   45.64   42.36   44.79
   42.49   40.43   42.95   43.06   40.48   41.81    39.5   40.05   38.43   39.48
   46.45   45.47   39.07   35.04   34.53    40.2   47.29   47.38   41.52    45.9
    45.9   35.51   43.87   45.43   41.74   40.86   43.03   41.92    45.7   58.77
    61.1      60   57.73   47.89   43.74   41.98    43.4    43.2   45.36   42.97
   46.94   46.05   48.91   48.12   49.91   49.48   45.16   45.57   43.44   48.07
  -678.7  -118.7   -88.7     1.3   331.3  1171.3  1301.3  1471.3  1831.3  2011.3
  2281.3  2341.3  2431.3  2641.3  3251.3  3281.3  3471.3  4321.3  4401.3  4511.3
  4551.3  4581.3  4614.8  4644.8  4684.8  4688.4  4860.4  4902.4 4920.11  4920.2
 5085.49  5085.6  5163.6  5164.3  5231.2  5291.1  5543.6  5753.6  5773.6  5813.6
  5833.6  5973.6  5993.6  6023.6  6043.6  6083.6  6113.6  7326.3  7496.3  8416.3
  8556.3  8866.3  8966.3  9146.3  9216.3  9276.7  9326.7 10393.8 10543.8 10710.2
   49.59   47.34   49.49   50.29   44.99   45.88   43.48   45.77   42.49   44.92
   42.62   40.56   43.08   43.19   40.61   41.94   39.63   40.18   38.56   39.61
   46.58    45.6    39.2   40.34   40.24   40.33   47.42   47.51   47.73   47.73
   47.73   47.73   44.35   45.56   41.87   40.99   43.16    42.8   45.83    58.9
   61.23   60.13   57.86   48.02   43.87   42.74   43.53   43.33   45.49    43.1
   47.07   46.18   49.04   48.25   50.04   49.61   45.29    45.7   43.57    48.2
   49.59   47.34   49.49   50.29   44.99   45.88   43.48   45.77   42.49   44.92
   42.62   40.56   43.08   43.19   40.61   41.94   39.63   40.18   38.56   39.61
   46.58    45.6    39.2   35.17   34.66   40.33   47.42   47.51   41.65   46.03
   46.03   35.64      44   45.56   41.87   40.99   43.16   42.05   45.83    58.9
   61.23   60.13   57.86   48.02   43.87   42.11   43.53   43.33   45.49    43.1
   47.07   46.18   49.04   48.25   50.04   49.61   45.29    45.7   43.57    48.2
Pier Skew, UpSta & Num, DnSta & Num=  ,4979.1, 2 ,4979.1, 2 , 0 , 0 , 0 ,,
       2       2
   26.04    46.9
       2       2
   26.17   47.03
Pier Skew, UpSta & Num, DnSta & Num=  ,5020.3, 2 ,5020.3, 2 , 0 , 0 , 0 ,,
       2       2
   26.02    46.9
       2       2
   26.15   47.03
Abutment Skew #Up #Dn= , 2 , 2
    4920  4930.8
    45.9   37.98
    4920  4930.8
   46.03   38.11
Abutment Skew #Up #Dn= , 2 , 2
  5075.4 5085.69
   34.41    45.9
  5075.4 5085.69
   34.54   46.03
BR Coef= 1 , 1 , 0 ,1.25, 0 ,,,0.8,0,2,0,
WSPro=,,,, 1 ,,,, 0 ,,,, 0 ,,,,-1 ,-1 ,-1 , 0 , 0 , 0 , 0 , 0
BR U #Sta/Elev= 30
  -678.7   49.46     1.3   50.16   331.3   44.86  2011.3   44.79  2341.3   40.43
  2641.3   43.06  4418.3   38.75  4511.3   39.48  4551.3   46.45  4581.3   45.47
  4634.8   35.82  4684.8   34.53  4688.4    40.2  4898.3   47.37  4902.4   47.38
  4942.9   33.98  5013.7   24.51  5164.3   45.43  5267.4   41.21  5753.6   41.92
  5813.6   58.77  5848.3   60.98  5983.6    59.2  6033.6   45.41  6083.6   41.98
  7496.3   45.36  8416.3   42.97  8999.3   48.77 10543.8   43.44 10710.2   48.07
BR U #Mann= 8
  -678.7      .2  4418.3      .1  4898.3     .07  4902.4    .035  5164.3      .1
  5267.4      .1  5848.3      .2  8999.3     .99
BR U Banks=4902.4,5164.3
BR D #Sta/Elev= 30
  -678.7   49.59     1.3   50.29   331.3   44.99  2011.3   44.92  2341.3   40.56
  2641.3   43.19  4418.3   38.88  4511.3   39.61  4551.3   46.58  4581.3    45.6
  4634.8   35.95  4684.8   34.66  4688.4   40.33  4898.3    47.5  4902.4   47.51
  4942.9   34.11  5013.7   24.64  5164.3   45.56  5267.4   41.34  5753.6   42.05
  5813.6    58.9  5848.3   61.11  5983.6   59.33  6033.6   45.54  6083.6   42.11
  7496.3   45.49  8416.3    43.1  8999.3    48.9 10543.8   43.57 10710.2    48.2
BR D #Mann= 8
  -678.7      .2  4418.3      .1  4898.3     .07  4902.4    .035  5164.3      .1
  5267.4      .1  5848.3      .2  8999.3     .99
BR D Banks=4902.4,5164.3
BC Design=,, 0 ,, 0 ,,,,,,
BC HTab HWMax=61.06
BC Use User HTab Curves=0
BC User HTab FreeFlow(D)= 0

Type RM Length L Ch R = 1 ,62922.5 ,402.3,402.3,402.3
BEGIN DESCRIPTION:
Downstream Section of Bridge/Culvert/Weir
END DESCRIPTION:
XS GIS Cut Line= 6
      3140948.42     13866200.91      3141227.36     13861006.77
      3141209.68     13859773.98      3141177.86     13858665.69
      3141368.38     13856875.29      3141812.92     13854879.09
#Sta/Elev= 30
  -678.7   49.59     1.3   50.29   331.3   44.99  2011.3   44.92  2341.3   40.56
  2641.3   43.19  4418.3   38.88  4511.3   39.61  4551.3   46.58  4581.3    45.6
  4634.8   35.95  4684.8   34.66  4688.4   40.33  4898.3    47.5  4902.4   47.51
  4942.9   34.11  5013.7   24.64  5164.3   45.56  5267.4   41.34  5753.6   42.05
  5813.6    58.9  5848.3   61.11  5983.6   59.33  6033.6   45.54  6083.6   42.11
  7496.3   45.49  8416.3    43.1  8999.3    48.9 10543.8   43.57 10710.2    48.2
#Mann= 8 , 1 , 0
  -678.7      .2       0  4418.3      .1       0  4898.3     .07       0
  4902.4    .035       0  5164.3      .1       0  5267.4      .1       0
  5848.3      .2       0  8999.3     .99       0
#XS Ineff= 2 , 0
       0    4555   46.38    9043       0      49
Permanent Ineff=
       F       F
Bank Sta=4902.4,5164.3
XS Rating Curve= 0 ,0
Exp/Cntr=0.5,0.3

Type RM Length L Ch R = 1 ,62520.2 ,1118.6,977.8,479.9
BEGIN DESCRIPTION:
Cross Section 62520.2
END DESCRIPTION:
XS GIS Cut Line= 6
      3141856.19     13866274.64      3142068.38     13861729.06
      3141426.94     13859879.68      3141388.23     13858121.88
      3141444.81     13856891.63      3141976.33     13854900.55
#Sta/Elev= 30
    -952   49.09    1458   40.57    3260   42.36  4453.5   40.36    4577   39.47
    4627   46.36  4675.1   37.74    4937   44.19    4987   29.06    4992   24.51
  5008.6    25.2  5015.4    30.8  5048.3   33.78  5073.3   40.05    5110   41.21
  5422.7   42.36  5573.9   42.49  5770.2    42.2  5810.2   43.62  5860.2   55.02
  5989.1   53.34  6050.2   43.85  6090.2    42.4  7429.6   45.76  8329.6   42.63
  8389.6   45.82  9175.1   49.59  9250.6   44.94 10487.1   44.22 10621.9   48.38
#Mann= 10 , 1 , 0
    -952      .2       0    3260     .14       0  4453.5     .07       0
  4675.1     .07       0    4937    .035       0  5073.3      .1       0
    5110     .12       0  5422.7      .1       0  5573.9     .14       0
  5989.1      .2       0
#XS Ineff= 2 , 0
       0    4627   46.36    9000       0    47.9
Permanent Ineff=
       F       F
Bank Sta=4937,5073.3
XS Rating Curve= 0 ,0
Exp/Cntr=0.3,0.1

Type RM Length L Ch R = 1 ,61542.4 ,1083.6,1133.3,856.3
BEGIN DESCRIPTION:
Cross Section 61542.4
END DESCRIPTION:
XS GIS Cut Line= 6
      3142954.58     13866115.83      3143126.62     13861616.37
      3142814.37     13860361.41      3141512.44     13858684.34
      3141499.69     13856899.47       3142046.9     13854937.93
#Sta/Elev= 30
 -1296.4   48.23   953.6   40.73  3531.4   42.92  4095.4   42.48  4339.7   40.45
  4436.4   40.55  4486.4   46.06  4569.6   40.83  4709.6   49.67  4864.1   47.67
    4896   39.42  4911.7   39.84  4985.8   30.23  5000.5   23.46  5007.7   24.71
    5014   30.86  5040.2   32.18  5061.7   39.99    5263   40.48  5383.1   43.98
  5761.5   43.19    6218   42.82  7281.8   45.45  8181.8   42.36  8231.8   45.58
  8952.7   49.13  9032.7   49.13  9082.7   44.96 10335.5   43.95 10469.5   48.54
#Mann= 9 , 1 , 0
 -1296.4      .2       0  3531.4     .14       0  4095.4      .1       0
  4339.7     .14       0  4911.7    .035       0  5061.7     .07       0
    5263     .12       0  5761.5      .2       0    6218      .2       0
#XS Ineff= 2 , 0
       0    4484   47.07    8550       0   47.12
Permanent Ineff=
       F       F
Bank Sta=4911.7,5061.7
XS Rating Curve= 0 ,0
Exp/Cntr=0.3,0.1

Type RM Length L Ch R = 1 ,60409.1 ,973.8,746.3,9
BEGIN DESCRIPTION:
Cross Section 60409.1
END DESCRIPTION:
XS GIS Cut Line= 6
      3143841.24     13866883.39      3143554.15     13859665.15
       3143199.8      13859236.2      3141632.97     13858326.37
      3141554.57     13856938.67      3142112.21      13855023.3
#Sta/Elev= 30
 -2564.5   47.21  -974.5   45.52     5.5   40.72  1945.5   44.66    3538   43.15
  4080.7   41.96  4150.8   40.22  4250.8   46.26  4300.8   40.54  4400.8   47.98
  4891.5   39.98  4921.9    30.4  4978.2   30.57  4999.3   24.38  5022.8   29.75
    5155    29.9  5185.5   38.59  5613.2   39.74  5783.4   39.08  5973.4   43.81
  6073.4   39.64  7848.2   44.55  8158.2   42.65  8218.2   45.76  8916.4   48.83
  9016.4    48.5  9066.4   44.76   10173   45.52   10233   41.45 10427.8   48.42
#Mann= 6 , 1 , 0
 -2564.5      .2       0    3538     .14       0  4080.7     .08       0
  4891.5    .035       0  5185.5     .08       0  5613.2      .2       0
#XS Ineff= 2 , 0
       0    4249   47.26    8532       0   47.25
Permanent Ineff=
       F       F
Bank Sta=4891.5,5185.5
XS Rating Curve= 0 ,0
Exp/Cntr=0.3,0.1

Type RM Length L Ch R = 1 ,59662.8 ,290.6,75.2,12.1
BEGIN DESCRIPTION:
Cross Section 59662.8
END DESCRIPTION:
XS GIS Cut Line= 6
      3145286.18     13859707.94       3143734.3     13858852.85
      3142885.69     13858965.73      3141727.06     13858263.65
      3141625.13     13856970.03      3142200.86     13855000.85
#Sta/Elev= 30
  3317.2   48.76  3437.2   43.12  3657.2   41.51  3677.2   44.74  3747.2   41.73
  3777.2   44.28  4257.2   39.16  4297.2   42.34  4422.3    40.8  4557.2   40.17
    4610   34.29  4687.5   39.14  4891.5   40.36  4921.9   30.78  4978.2   30.95
  4999.3   24.76  5022.8   30.13    5155   30.28  5185.5   38.97  5400.4   42.09
  5980.9   39.14  6199.6   43.14  6328.9   39.77  6668.9   39.86  8098.5   44.28
  8408.5   43.13  9159.3   48.76  9305.2   44.88   10524    44.1 10658.8   48.56
#Mann= 7 , 1 , 0
  3317.2      .2       0  4422.3     .09       0  4687.5      .1       0
  4891.5    .035       0  5185.5     .11       0  6199.6      .2       0
  8098.5      .2       0
#XS Ineff= 2 , 0
       0                    8499       0    46.3
Permanent Ineff=
       F       F
Bank Sta=4891.5,5185.5
XS Rating Curve= 0 ,0
Exp/Cntr=0.5,0.3

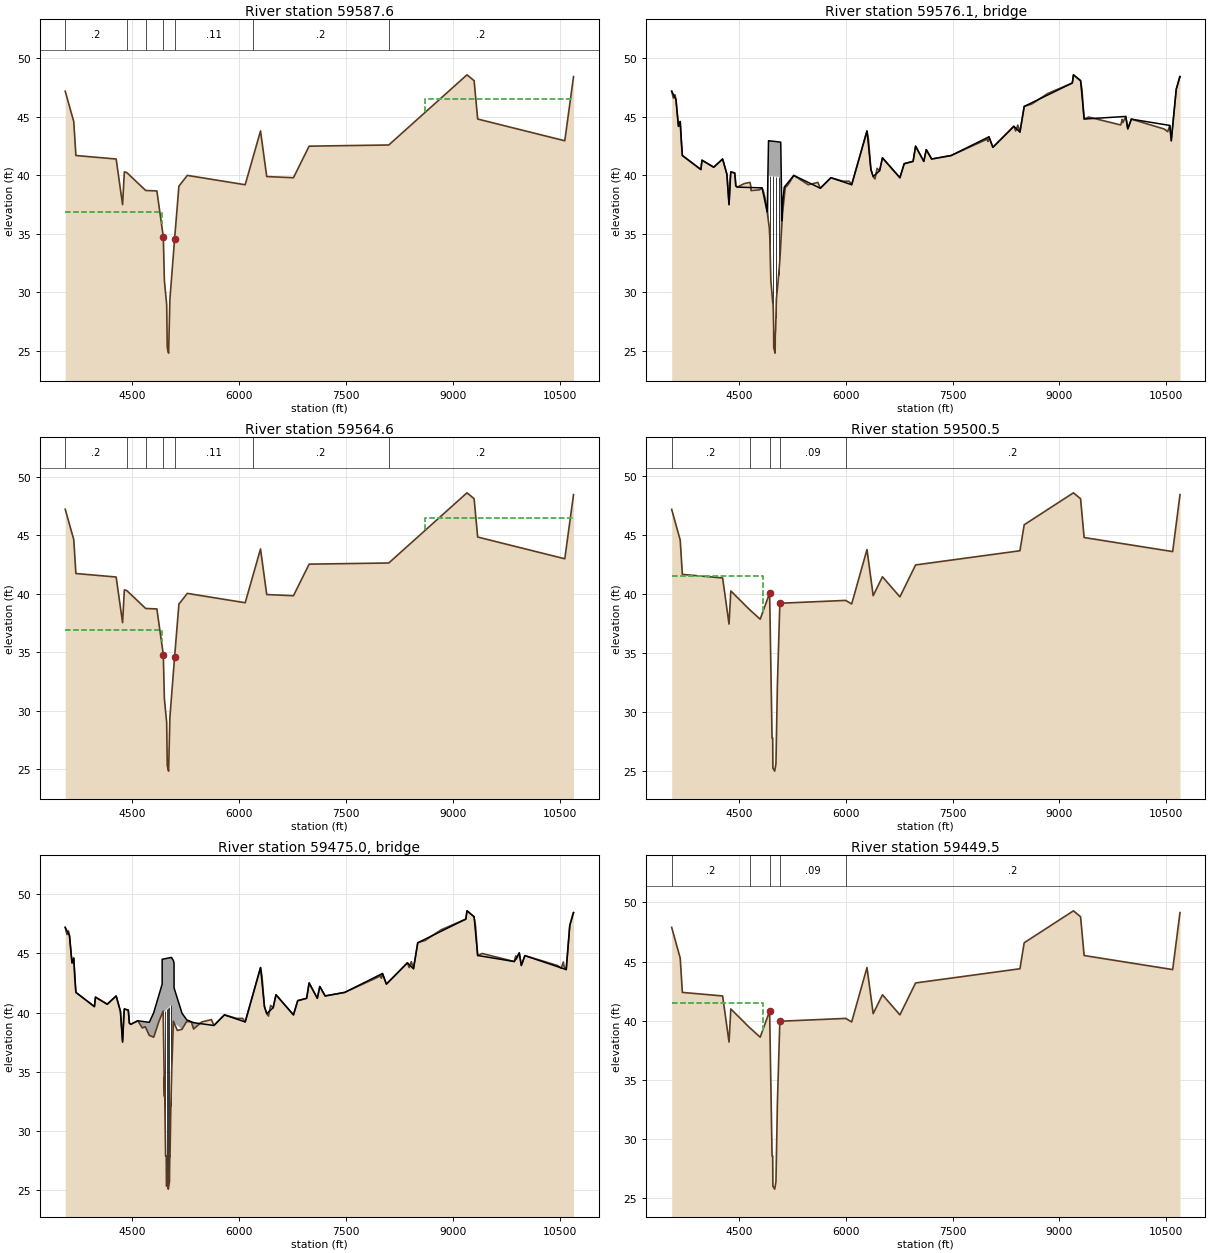
Type RM Length L Ch R = 1 ,59587.6 ,23,23,23
BEGIN DESCRIPTION:
Upstream Section of Bridge/Culvert/Weir
END DESCRIPTION:
XS GIS Cut Line= 6
      3145275.74     13859159.41      3144011.01     13858823.19
      3142690.47     13858775.63      3141766.02     13858185.58
      3141679.78     13857017.41       3142300.4     13854885.67
#Sta/Elev= 30
  3557.9   47.19  3677.9   44.59  3707.9   41.69  4272.9   41.39  4362.9   37.49
  4387.9   40.29  4422.3   40.23  4687.5    38.7 4844.42   38.66 4934.72   34.73
 4949.52      31 4981.92   28.95 4990.02   25.27 5008.72   24.79 5027.22   29.41
 5092.32   34.51 5153.62   39.07  5271.3   39.99  6083.8   39.19  6199.6   41.67
  6298.8   43.79  6385.8   39.89  6760.8   39.79  6980.8   42.49  8098.5   42.59
    9196   48.59    9296   48.09    9346   44.81 10568.5   42.95 10691.2   48.44
#Mann= 7 , 1 , 0
  3557.9      .2       0  4422.3     .09       0  4687.5      .1       0
 4934.72    .035       0 5092.32     .11       0  6199.6      .2       0
  8098.5      .2       0
#XS Ineff= 2 , 0
       0    4910   36.88    8610       0    46.5
Permanent Ineff=
       F       F
Bank Sta=4934.72,5092.32
XS Rating Curve= 0 ,0
Exp/Cntr=0.5,0.3

Type RM Length L Ch R = 3 ,59576.1 ,,,
BEGIN DESCRIPTION:
Pipeline - 40 Degree Skew
END DESCRIPTION:
Bridge Culvert--1,0,-1,-1, 0
Deck Dist Width WeirC Skew NumUp NumDn MinLoCord MaxHiCord MaxSubmerge Is_Ogee
10,3,2.6,0, 60, 60, , , 0.95, 0, 1,1,,
  3557.9  3617.9  3652.9  3677.9  3707.9  3967.9  3982.9  4147.9  4272.9  4332.9
  4362.9  4387.9  4442.9  4457.9    4478 4826.12 4898.82 4916.82    4922 4922.09
 5080.83 5080.94 5088.62 5105.12 5116.52 5137.72 5153.62  5271.3  5643.9    5792
  6083.8  6298.8  6353.8  6385.8  6475.8  6515.8  6760.8  6820.8  6945.8  6980.8
  7095.8  7130.8  7205.8  7480.1  8010.1  8065.1  8360.1  8445.1  8505.1  9180.1
    9196    9296    9346  9929.9  9958.5 10008.5 10548.5 10568.5 10638.5 10691.2
    47.2    46.5    44.2    44.6    41.7    40.5    41.3    40.7    41.4    40.1
    37.5    40.3    40.2    39.1      39   38.93   36.86   42.96   42.96   42.96
   42.85   42.85   42.84   36.13   37.75   38.99   39.11      40    38.9    39.8
    39.2    43.8    40.5    39.9    40.4    41.5    39.8      41    41.2    42.5
    41.2    42.2    41.4    41.7    43.3    42.4    44.2    43.7    45.9    47.9
    48.6    48.1   44.82   45.04   43.98   44.81   44.27   42.96   47.36   48.45
    47.2    46.5    44.2    44.6    41.7    40.5    41.3    40.7    41.4    40.1
    37.5    40.3    40.2    39.1      39   38.93   36.85   36.02   35.79   39.96
   39.85   33.28   34.12   35.88   36.92   38.15   39.08      40    38.9    39.8
    39.2    43.8    40.5    39.9    40.4    41.5    39.8      41    41.2    42.5
    41.2    42.2    41.4    41.7    43.3    42.4    44.2    43.7    45.9    47.9
    48.6    48.1   44.82   45.04   43.98   44.81   44.27   42.96   47.36   48.45
  3557.9  3617.9  3652.9  3677.9  3707.9  3967.9  3982.9  4147.9  4272.9  4332.9
  4362.9  4387.9  4442.9  4457.9    4478 4826.12 4898.82 4916.82    4922 4922.09
 5080.83 5080.94 5088.62 5105.12 5116.52 5137.72 5153.62  5271.3  5643.9    5792
  6083.8  6298.8  6353.8  6385.8  6475.8  6515.8  6760.8  6820.8  6945.8  6980.8
  7095.8  7130.8  7205.8  7480.1  8010.1  8065.1  8360.1  8445.1  8505.1  9180.1
    9196    9296    9346  9929.9  9958.5 10008.5 10548.5 10568.5 10638.5 10691.2
    47.2    46.5    44.2    44.6    41.7    40.5    41.3    40.7    41.4    40.1
    37.5    40.3    40.2    39.1      39   38.93   36.86   42.96   42.96   42.96
   42.85   42.85   42.84   36.13   37.75   38.99   39.11      40    38.9    39.8
    39.2    43.8    40.5    39.9    40.4    41.5    39.8      41    41.2    42.5
    41.2    42.2    41.4    41.7    43.3    42.4    44.2    43.7    45.9    47.9
    48.6    48.1   44.82   45.04   43.98   44.81   44.27   42.96   47.36   48.45
    47.2    46.5    44.2    44.6    41.7    40.5    41.3    40.7    41.4    40.1
    37.5    40.3    40.2    39.1      39   38.93   36.85   36.02   35.79   39.96
   39.85   33.28   34.12   35.88   36.92   38.15   39.08      40    38.9    39.8
    39.2    43.8    40.5    39.9    40.4    41.5    39.8      41    41.2    42.5
    41.2    42.2    41.4    41.7    43.3    42.4    44.2    43.7    45.9    47.9
    48.6    48.1   44.82   45.04   43.98   44.81   44.27   42.96   47.36   48.45
Pier Skew, UpSta & Num, DnSta & Num=  ,4944, 2 ,4944, 2 , 0 , 0 , 0 ,,
     1.4     1.4
   31.24   40.94
     1.4     1.4
   31.24   40.94
Pier Skew, UpSta & Num, DnSta & Num=  ,4981.8, 2 ,4981.8, 2 , 0 , 0 , 0 ,,
     1.4     1.4
   27.81   40.91
     1.4     1.4
   27.81   40.91
Pier Skew, UpSta & Num, DnSta & Num=  ,5021, 2 ,5021, 2 , 0 , 0 , 0 ,,
     1.4     1.4
    26.6   40.89
     1.4     1.4
    26.6   40.89
Pier Skew, UpSta & Num, DnSta & Num=  ,5058.6, 2 ,5058.6, 2 , 0 , 0 , 0 ,,
     1.4     1.4
   30.42   40.87
     1.4     1.4
   30.42   40.87
BR Coef= 1 , 1 , 0 ,1.25, 0 ,,,0.8,0,2,0,
WSPro=,,,, 1 ,,,, 0 ,,,, 0 ,,,,-1 ,-1 ,-1 , 0 , 0 , 0 , 0 , 0
BR U #Sta/Elev= 127
  3557.9    47.2  3582.9    46.6  3602.9    46.9  3617.9    46.5  3652.9    44.2
  3662.9    44.2  3672.9    44.6  3677.9    44.6  3692.9    42.8  3707.9    41.7
  3967.9    40.5  3982.9    41.3  4147.9    40.7  4272.9    41.4  4332.9    40.1
  4362.9    37.5  4377.9    39.7  4387.9    40.3  4422.3   40.24  4442.9    40.2
  4452.9    39.6  4457.9    39.1    4478      39  4577.2    39.3  4657.2    39.4
  4667.2    39.1  4672.2    38.7  4687.5   38.71 4788.32   38.76 4826.12   38.93
 4844.42   38.67 4864.12   38.16 4886.02   37.43 4898.82   36.85 4916.82   36.02
    4922   35.79 4922.09   35.78 4927.22   35.55 4934.72   34.74 4949.52   31.01
 4976.32   29.14 4981.92   28.96 4988.82   27.04 4990.02   25.28 5008.72    24.8
 5010.42   25.33 5011.22   26.29 5017.42   26.86 5027.22   29.42 5052.72   31.04
 5076.12   32.75 5080.83   33.26 5080.94   33.28 5088.62   34.12 5092.32   34.52
 5105.12   35.88 5112.82    36.7 5114.71   36.81 5114.82   36.82 5114.93   36.82
 5116.52   36.92 5137.72   38.15 5152.12   38.99 5153.62   39.08 5168.61   39.04
 5168.72   39.04 5168.83   39.04 5169.72   39.04 5216.82   39.44  5271.3      40
  5474.5    39.2  5609.5    39.4  5643.9    38.9    5792    39.8  5964.1    39.5
  6048.8    39.5  6083.8    39.2  6199.6   41.68  6298.8    43.8  6318.8    43.1
  6353.8    40.5  6385.8    39.9  6410.8    39.7  6440.8    40.6  6475.8    40.4
  6515.8    41.5  6760.8    39.8  6820.8      41  6945.8    41.2  6980.8    42.5
  7095.8    41.2  7130.8    42.2  7205.8    41.4  7480.1    41.7  7985.1    43.1
  7995.1    42.9  8010.1    43.3  8065.1    42.4  8098.5    42.6  8360.1    44.2
  8385.1    43.8  8415.1    44.3  8445.1    43.7  8505.1    45.9  8610.1    46.1
  8835.1      47  9180.1    47.9    9185    48.1    9186   48.14    9196    48.6
    9296    48.1    9316   47.32    9346   44.82  9409.9   44.99  9859.9   44.31
  9879.9   44.79  9889.9   44.52  9929.9   45.04  9958.5   43.98 10008.5   44.81
 10468.5   43.97 10518.5   43.74 10548.5   44.27 10568.5   42.96 10638.5   47.36
 10688.5   48.46 10691.2   48.45
BR U #Mann= 7
  3557.9      .2  4422.3     .09  4687.5      .1 4934.72    .035 5092.32     .11
  6199.6      .2  8098.5      .2
BR U Banks=4934.72,5092.32
BR D #Sta/Elev= 127
  3557.9    47.2  3582.9    46.6  3602.9    46.9  3617.9    46.5  3652.9    44.2
  3662.9    44.2  3672.9    44.6  3677.9    44.6  3692.9    42.8  3707.9    41.7
  3967.9    40.5  3982.9    41.3  4147.9    40.7  4272.9    41.4  4332.9    40.1
  4362.9    37.5  4377.9    39.7  4387.9    40.3  4422.3   40.24  4442.9    40.2
  4452.9    39.6  4457.9    39.1    4478      39  4577.2    39.3  4657.2    39.4
  4667.2    39.1  4672.2    38.7  4687.5   38.71 4788.32   38.76 4826.12   38.93
 4844.42   38.67 4864.12   38.16 4886.02   37.43 4898.82   36.85 4916.82   36.02
    4922   35.79 4922.09   35.78 4927.22   35.55 4934.72   34.74 4949.52   31.01
 4976.32   29.14 4981.92   28.96 4988.82   27.04 4990.02   25.28 5008.72    24.8
 5010.42   25.33 5011.22   26.29 5017.42   26.86 5027.22   29.42 5052.72   31.04
 5076.12   32.75 5080.83   33.26 5080.94   33.28 5088.62   34.12 5092.32   34.52
 5105.12   35.88 5112.82    36.7 5114.71   36.81 5114.82   36.82 5114.93   36.82
 5116.52   36.92 5137.72   38.15 5152.12   38.99 5153.62   39.08 5168.61   39.04
 5168.72   39.04 5168.83   39.04 5169.72   39.04 5216.82   39.44  5271.3      40
  5474.5    39.2  5609.5    39.4  5643.9    38.9    5792    39.8  5964.1    39.5
  6048.8    39.5  6083.8    39.2  6199.6   41.68  6298.8    43.8  6318.8    43.1
  6353.8    40.5  6385.8    39.9  6410.8    39.7  6440.8    40.6  6475.8    40.4
  6515.8    41.5  6760.8    39.8  6820.8      41  6945.8    41.2  6980.8    42.5
  7095.8    41.2  7130.8    42.2  7205.8    41.4  7480.1    41.7  7985.1    43.1
  7995.1    42.9  8010.1    43.3  8065.1    42.4  8098.5    42.6  8360.1    44.2
  8385.1    43.8  8415.1    44.3  8445.1    43.7  8505.1    45.9  8610.1    46.1
  8835.1      47  9180.1    47.9    9185    48.1    9186   48.14    9196    48.6
    9296    48.1    9316   47.32    9346   44.82  9409.9   44.99  9859.9   44.31
  9879.9   44.79  9889.9   44.52  9929.9   45.04  9958.5   43.98 10008.5   44.81
 10468.5   43.97 10518.5   43.74 10548.5   44.27 10568.5   42.96 10638.5   47.36
 10688.5   48.46 10691.2   48.45
BR D #Mann= 7
  3557.9      .2  4422.3     .09  4687.5      .1 4934.72    .035 5092.32     .11
  6199.6      .2  8098.5      .2
BR D Banks=4934.72,5092.32
BC Design=,, 0 ,, 0 ,,,,,,
BC HTab HWMax=48.59
BC Use User HTab Curves=0
BC User HTab FreeFlow(D)= 0

Type RM Length L Ch R = 1 ,59564.6 ,64.1,64.1,64.1
BEGIN DESCRIPTION:
Downstream Section of Bridge/Culvert/Weir
END DESCRIPTION:
XS GIS Cut Line= 6
       3145291.9     13859143.05      3144027.17     13858806.83
      3142706.63     13858759.27      3141782.18     13858169.22
      3141695.94     13857001.05      3142316.56     13854869.31
#Sta/Elev= 30
  3557.9   47.23  3677.9   44.63  3707.9   41.73  4272.9   41.43  4362.9   37.53
  4387.9   40.33  4422.3   40.27  4687.5   38.74 4844.42    38.7 4934.72   34.77
 4949.52   31.04 4981.92   28.99 4990.02   25.31 5008.72   24.83 5027.22   29.45
 5092.32   34.55 5153.62   39.11  5271.3   40.03  6083.8   39.23  6199.6   41.71
  6298.8   43.83  6385.8   39.93  6760.8   39.83  6980.8   42.53  8098.5   42.63
    9196   48.63    9296   48.13    9346   44.85 10568.5   42.99 10691.2   48.48
#Mann= 7 , 1 , 0
  3557.9      .2       0  4422.3     .09       0  4687.5      .1       0
 4934.72    .035       0 5092.32     .11       0  6199.6      .2       0
  8098.5      .2       0
#XS Ineff= 2 , 0
       0    4910   36.88    8610       0    46.5
Permanent Ineff=
       F       F
Bank Sta=4934.72,5092.32
XS Rating Curve= 0 ,0
Exp/Cntr=0.5,0.3

Type RM Length L Ch R = 1 ,59500.5 ,51,51,51
BEGIN DESCRIPTION:
Upstream Section of Bridge/Culvert/Weir
END DESCRIPTION:
XS GIS Cut Line= 6
      3145315.84     13859121.43      3144251.19     13858807.96
      3142746.19     13858732.99      3141864.66     13858194.18
       3141754.9     13857026.01      3142420.99     13854825.01
#Sta/Elev= 30
  3557.9   47.17  3677.9   44.57  3707.9   41.67  4272.9   41.37  4362.9   37.47
  4387.9   40.27  4651.7   38.69  4800.1   37.88  4932.4   40.09  4966.7   27.83
  4975.6   27.84  4978.5   25.28  5003.5   25.03  5021.2   25.66  5041.3   32.27
  5075.9   39.23  6000.3   39.47  6083.8   39.17  6298.8   43.77  6385.8   39.87
  6515.8   41.47  6760.8   39.77  6980.8   42.47  8445.1   43.67  8505.1   45.87
    9196   48.57    9296   48.07    9346   44.79 10588.5    43.6 10691.2   48.42
#Mann= 5 , 1 , 0
  3557.9      .2       0  4651.7     .09       0  4932.4    .035       0
  5075.9     .09       0  6000.3      .2       0
#XS Ineff= 2 , 0
       0    4833    41.5    8612       0   46.11
Permanent Ineff=
       F       F
Bank Sta=4932.4,5075.9
XS Rating Curve= 0 ,0
Exp/Cntr=0.5,0.3

Type RM Length L Ch R = 3 ,59475.0 ,,,
BEGIN DESCRIPTION:
INTERSTATE 610-ACCESS ROAD - 40 Degree Skew
Structure ID: H00-47
END DESCRIPTION:
Bridge Culvert--1,0,-1,-1, 0
Deck Dist Width WeirC Skew NumUp NumDn MinLoCord MaxHiCord MaxSubmerge Is_Ogee
10,31,2.6,0, 60, 60, , , 0.95, 0, 1,1,,
  3557.9  3617.9  3652.9  3677.9  3707.9  3967.9  3982.9  4147.9  4272.9  4332.9
  4362.9  4387.9  4442.9  4457.9    4478  4577.2  4738.2  4800.1 4918.29  4918.4
  5049.4 5049.51  5075.9  5085.3 5085.41  5196.8  5263.1  5359.6  5643.9    5792
  6083.8  6298.8  6353.8  6385.8  6475.8  6515.8  6760.8  6820.8  6945.8  6980.8
  7095.8  7130.8  7205.8  7480.1  8010.1  8065.1  8360.1  8445.1  8505.1  9180.1
    9196    9296    9346  9859.9  9929.9  9958.5 10008.5 10588.5 10638.5 10691.2
    47.2    46.5    44.2    44.6    41.7    40.5    41.3    40.7    41.4    40.1
    37.5    40.3    40.2    39.1      39    39.3   39.17   39.99    42.4    44.5
   44.66   44.66    44.4   44.18   42.08   39.94   39.38   39.14    38.9    39.8
    39.2    43.8    40.5    39.9    40.4    41.5    39.8      41    41.2    42.5
    41.2    42.2    41.4    41.7    43.3    42.4    44.2    43.7    45.9    47.9
    48.6    48.1   44.82   44.31   45.04   43.98   44.81   43.63   47.36   48.45
    47.2    46.5    44.2    44.6    41.7    40.5    41.3    40.7    41.4    40.1
    37.5    40.3    40.2    39.1      39    39.3   38.06   37.91   39.91   39.91
   40.66   34.29   39.26   39.13   39.13   38.58   39.25    38.6    38.9    39.8
    39.2    43.8    40.5    39.9    40.4    41.5    39.8      41    41.2    42.5
    41.2    42.2    41.4    41.7    43.3    42.4    44.2    43.7    45.9    47.9
    48.6    48.1   44.82   44.31   45.04   43.98   44.81   43.63   47.36   48.45
  3557.9  3617.9  3652.9  3677.9  3707.9  3967.9  3982.9  4147.9  4272.9  4332.9
  4362.9  4387.9  4442.9  4457.9  4577.2  4733.3  4800.1 4918.29  4918.4  5049.4
 5049.51  5075.9  5085.3 5085.41  5131.2  5263.1  5359.6    5792  6083.8  6298.8
  6353.8  6385.8  6475.8  6515.8  6760.8  6820.8  6945.8  6980.8  7095.8  7130.8
  7205.8  7480.1  8010.1  8065.1  8360.1  8445.1  8505.1  9180.1    9196    9296
    9346  9859.9  9929.9  9958.5 10008.5 10518.5 10548.5 10588.5 10638.5 10691.2
    47.9    47.2    44.9    45.3    42.4    41.2      42    41.4    42.1    40.8
    38.2      41    40.9    39.8      40   39.11   39.99    42.4    44.5   44.66
   44.66    44.4   44.18   42.08   40.98   39.95    39.3    40.5    39.9    44.5
    41.2    40.6    41.1    42.2    40.5    41.7    41.9    43.2    41.9    42.9
    42.1    42.4      44    43.1    44.9    44.4    46.6    48.6    49.3    48.8
   45.52   45.01   45.74   44.68   45.51   44.44   44.97   44.33   48.06   49.15
    47.9    47.2    44.9    45.3    42.4    41.2      42    41.4    42.1    40.8
    38.2      41    40.9    39.8      40   38.82   38.61   40.61   40.61   41.36
   34.99   39.96   39.83   39.83   39.19   39.95    39.3    40.5    39.9    44.5
    41.2    40.6    41.1    42.2    40.5    41.7    41.9    43.2    41.9    42.9
    42.1    42.4      44    43.1    44.9    44.4    46.6    48.6    49.3    48.8
   45.52   45.01   45.74   44.68   45.51   44.44   44.97   44.33   48.06   49.15
Pier Skew, UpSta & Num, DnSta & Num=  ,4962.4, 2 ,4962.4, 2 , 0 , 0 , 0 ,,
     1.4     1.4
   28.43   41.56
     1.4     1.4
   29.13   42.26
Pier Skew, UpSta & Num, DnSta & Num=  ,4981.2, 2 ,4981.2, 2 , 0 , 0 , 0 ,,
     1.4     1.4
   24.39   41.57
     1.4     1.4
   25.09   42.27
Pier Skew, UpSta & Num, DnSta & Num=  ,5001, 2 ,5001, 2 , 0 , 0 , 0 ,,
     1.4     1.4
   25.05    41.6
     1.4     1.4
   25.75    42.3
Pier Skew, UpSta & Num, DnSta & Num=  ,5019.9, 2 ,5019.9, 2 , 0 , 0 , 0 ,,
     1.4     1.4
   24.62   41.63
     1.4     1.4
   25.32   42.33
Pier Skew, UpSta & Num, DnSta & Num=  ,5040.7, 2 ,5040.7, 2 , 0 , 0 , 0 ,,
     1.4     1.4
   30.84   41.65
     1.4     1.4
   31.54   42.35
Abutment Skew #Up #Dn= , 2 , 2
 4933.43 4974.36
   40.52   27.87
 4933.43 4974.36
   41.22   28.57
Abutment Skew #Up #Dn= , 2 , 2
 5021.79  5049.6
   26.12   40.66
 5021.79  5049.6
   26.82   41.36
BR Coef= 1 , 1 , 0 ,1.25, 0 ,,,0.8,0,2,0,
WSPro=,,,, 1 ,,,, 0 ,,,, 0 ,,,,-1 ,-1 ,-1 , 0 , 0 , 0 , 0 , 0
BR U #Sta/Elev= 129
  3557.9    47.2  3582.9    46.6  3602.9    46.9  3617.9    46.5  3652.9    44.2
  3662.9    44.2  3672.9    44.6  3677.9    44.6  3692.9    42.8  3707.9    41.7
  3967.9    40.5  3982.9    41.3  4147.9    40.7  4272.9    41.4  4332.9    40.1
  4362.9    37.5  4377.9    39.7  4387.9    40.3  4442.9    40.2  4452.9    39.6
  4457.9    39.1    4478      39  4577.2    39.3  4640.5   38.69  4651.7   38.72
  4678.2   38.78  4681.6   38.79  4733.3   38.12  4738.2   38.06  4800.1   37.91
  4801.3   37.93  4870.1   39.19  4870.5    39.2  4913.8   39.84 4918.29   39.91
  4918.4   39.91 4918.51   39.91  4932.4   40.12 4933.54   39.68 4933.63   39.65
  4951.2    32.9  4951.5   34.55  4966.7   27.86 4974.36   27.87  4975.6   27.87
  4977.5   26.61  4978.5   25.31  5001.3   26.27  5003.5   25.06  5021.2   25.69
 5021.79   26.12  5022.6   26.72  5025.9   27.86  5028.3   27.81  5041.3    32.3
  5049.4   34.27 5049.51   34.29  5052.8   35.09  5064.3   37.17  5075.9   39.26
 5085.19   39.13  5085.3   39.13 5085.41   39.13  5131.2   38.49  5131.9   38.48
  5194.9   38.58  5196.8   38.58  5263.1   39.25  5265.5   39.25  5325.5   39.18
  5329.6   39.18  5359.6    38.6  5474.5    39.2  5483.3   39.21  5609.5    39.4
  5643.9    38.9    5792    39.8  5964.1    39.5  6000.3    39.5  6048.8    39.5
  6083.8    39.2  6298.8    43.8  6318.8    43.1  6353.8    40.5  6385.8    39.9
  6410.8    39.7  6440.8    40.6  6475.8    40.4  6515.8    41.5  6760.8    39.8
  6820.8      41  6945.8    41.2  6980.8    42.5  7095.8    41.2  7130.8    42.2
  7205.8    41.4  7480.1    41.7  7985.1    43.1  7995.1    42.9  8010.1    43.3
  8065.1    42.4  8360.1    44.2  8385.1    43.8  8415.1    44.3  8445.1    43.7
  8505.1    45.9  8610.1    46.1  8835.1      47  9180.1    47.9    9186   48.14
    9196    48.6    9296    48.1    9316   47.32    9346   44.82  9409.9   44.99
  9859.9   44.31  9879.9   44.79  9889.9   44.52  9929.9   45.04  9958.5   43.98
 10008.5   44.81 10468.5   43.97 10518.5   43.74 10548.5   44.27 10558.5   43.87
 10588.5   43.63 10638.5   47.36 10688.5   48.46 10691.2   48.45
BR U #Mann= 5
  3557.9      .2  4651.7     .09  4932.4    .035  5075.9     .09  6000.3      .2
BR U Banks=4932.4,5075.9
BR D #Sta/Elev= 129
  3557.9    47.9  3582.9    47.3  3602.9    47.6  3617.9    47.2  3652.9    44.9
  3662.9    44.9  3672.9    45.3  3677.9    45.3  3692.9    43.5  3707.9    42.4
  3967.9    41.2  3982.9      42  4147.9    41.4  4272.9    42.1  4332.9    40.8
  4362.9    38.2  4377.9    40.4  4387.9      41  4442.9    40.9  4452.9    40.3
  4457.9    39.8    4478    39.7  4577.2      40  4640.5   39.39  4651.7   39.42
  4678.2   39.48  4681.6   39.49  4733.3   38.82  4738.2   38.76  4800.1   38.61
  4801.3   38.63  4870.1   39.89  4870.5    39.9  4913.8   40.54 4918.29   40.61
  4918.4   40.61 4918.51   40.61  4932.4   40.82 4933.54   40.38 4933.63   40.35
  4951.2    33.6  4951.5   35.25  4966.7   28.56 4974.36   28.57  4975.6   28.57
  4977.5   27.31  4978.5   26.01  5001.3   26.97  5003.5   25.76  5021.2   26.39
 5021.79   26.82  5022.6   27.42  5025.9   28.56  5028.3   28.51  5041.3      33
  5049.4   34.97 5049.51   34.99  5052.8   35.79  5064.3   37.87  5075.9   39.96
 5085.19   39.83  5085.3   39.83 5085.41   39.83  5131.2   39.19  5131.9   39.18
  5194.9   39.28  5196.8   39.28  5263.1   39.95  5265.5   39.95  5325.5   39.88
  5329.6   39.88  5359.6    39.3  5474.5    39.9  5483.3   39.91  5609.5    40.1
  5643.9    39.6    5792    40.5  5964.1    40.2  6000.3    40.2  6048.8    40.2
  6083.8    39.9  6298.8    44.5  6318.8    43.8  6353.8    41.2  6385.8    40.6
  6410.8    40.4  6440.8    41.3  6475.8    41.1  6515.8    42.2  6760.8    40.5
  6820.8    41.7  6945.8    41.9  6980.8    43.2  7095.8    41.9  7130.8    42.9
  7205.8    42.1  7480.1    42.4  7985.1    43.8  7995.1    43.6  8010.1      44
  8065.1    43.1  8360.1    44.9  8385.1    44.5  8415.1      45  8445.1    44.4
  8505.1    46.6  8610.1    46.8  8835.1    47.7  9180.1    48.6    9186   48.84
    9196    49.3    9296    48.8    9316   48.02    9346   45.52  9409.9   45.69
  9859.9   45.01  9879.9   45.49  9889.9   45.22  9929.9   45.74  9958.5   44.68
 10008.5   45.51 10468.5   44.67 10518.5   44.44 10548.5   44.97 10558.5   44.57
 10588.5   44.33 10638.5   48.06 10688.5   49.16 10691.2   49.15
BR D #Mann= 5
  3557.9      .2  4651.7     .09  4932.4    .035  5075.9     .09  6000.3      .2
BR D Banks=4932.4,5075.9
BC Design=,, 0 ,, 0 ,,,,,,
BC HTab HWMax=48.57
BC Use User HTab Curves=0
BC User HTab FreeFlow(D)= 0

Type RM Length L Ch R = 1 ,59449.5 ,60.5,60.5,60.5
BEGIN DESCRIPTION:
Downstream Section of Bridge/Culvert/Weir
END DESCRIPTION:
XS GIS Cut Line= 6
      3145354.24     13859087.86      3144289.59      13858774.4
      3142784.59     13858699.43      3141903.06     13858160.62
       3141793.3     13856992.45      3142459.38     13854791.44
#Sta/Elev= 30
  3557.9   47.89  3677.9   45.29  3707.9   42.39  4272.9   42.09  4362.9   38.19
  4387.9   40.99  4651.7   39.41  4800.1    38.6  4932.4   40.81  4966.7   28.55
  4975.6   28.56  4978.5      26  5003.5   25.75  5021.2   26.38  5041.3   32.99
  5075.9   39.95  6000.3   40.19  6083.8   39.89  6298.8   44.49  6385.8   40.59
  6515.8   42.19  6760.8   40.49  6980.8   43.19  8445.1   44.39  8505.1   46.59
    9196   49.29    9296   48.79    9346   45.51 10588.5   44.32 10691.2   49.14
#Mann= 5 , 1 , 0
  3557.9      .2       0  4651.7     .09       0  4932.4    .035       0
  5075.9     .09       0  6000.3      .2       0
#XS Ineff= 2 , 0
       0    4833    41.5    8612       0   46.11
Permanent Ineff=
       F       F
Bank Sta=4932.4,5075.9
XS Rating Curve= 0 ,0
Exp/Cntr=0.5,0.3

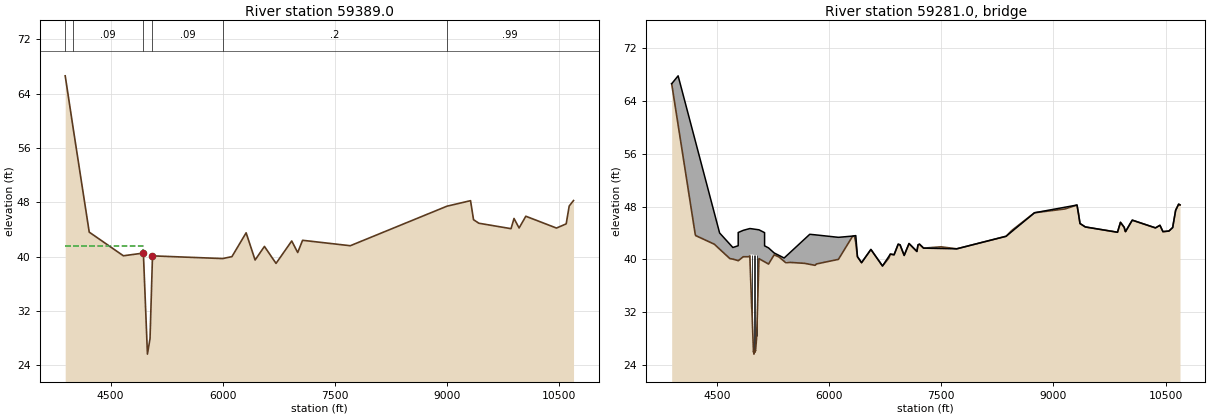
Type RM Length L Ch R = 1 ,59389.0 ,216,216,216
BEGIN DESCRIPTION:
Upstream Section of Bridge/Culvert/Weir
END DESCRIPTION:
XS GIS Cut Line= 6
      3145092.54     13858806.48      3143050.95     13858652.77
      3142765.78     13858594.85      3142084.06     13858169.24
      3141927.26     13857063.79      3142679.45     13854638.81
#Sta/Elev= 30
  3893.2   66.61  3999.9   58.89  4214.6   43.61  4671.5   40.13  4938.8   40.53
  4993.2   25.66  5027.8   27.94  5060.8   40.12    6000   39.72  6123.5   40.01
  6313.2   43.51  6433.2   39.51  6558.2   41.51  6713.2   39.01  6923.2   42.31
  7003.2   40.61  7068.2   42.41  7706.5   41.61  8999.9   47.43    9315   48.24
    9355   45.44  9426.5   44.92  9856.5   44.12  9896.5   45.62  9964.5   44.22
 10054.5   45.95 10464.5   44.21 10594.5   44.83 10634.5   47.45 10692.6   48.26
#Mann= 6 , 1 , 0
  3893.2      .2       0  3999.9     .09       0  4938.8    .015       0
  5060.8     .09       0    6000      .2       0  8999.9     .99       0
#XS Ineff= 2 , 0
       0    4930    41.6    5070       0      40
Permanent Ineff=
       F       F
Bank Sta=4938.8,5060.8
XS Rating Curve= 0 ,0
Exp/Cntr=0.5,0.3

Type RM Length L Ch R = 3 ,59281.0 ,,,
BEGIN DESCRIPTION:
INTERSTATE 610 - 40 Degree Skew
Structure ID: H00-46
END DESCRIPTION:
Bridge Culvert--1,0,-1,-1, 0
Deck Dist Width WeirC Skew NumUp NumDn MinLoCord MaxHiCord MaxSubmerge Is_Ogee
10,196,2.6,0, 60, 60, , , 0.95, 0, 1,1,,
  3893.2  3979.5  4214.6  4463.3  4534.5  4671.5  4711.8 4782.99  4783.1  4850.5
  4938.8 4948.71  4948.8 5047.32 5047.43  5060.8  5135.9 5136.01  5188.8  5263.1
  5397.5  5740.1  5812.1  6123.5  6313.2  6338.2  6356.1  6378.2  6433.2  6558.2
  6713.2  6818.2  6868.2  6923.2  6948.2  7003.2  7068.2  7173.2  7188.2  7208.2
  7263.2  7706.5  8366.5  8746.5    9315    9355  9426.5  9856.5  9896.5  9946.5
  9964.5 10054.5 10364.5 10424.5 10464.5 10544.5 10594.5 10634.5 10674.5 10692.6
    66.6    67.8   57.72   47.05      44    42.3    41.8   42.07   44.07    44.4
   44.67   44.66   44.66    44.5    44.5   44.48   44.05   42.05   41.74   40.98
   40.21    43.8   43.72   43.34   43.53   43.57    43.6    40.4    39.5    41.5
      39    40.8    40.7    42.3    42.2    40.6    42.4    41.2    42.2    42.3
    41.7    41.6    43.5   47.06   48.23   45.43   44.91   44.11   45.61   44.85
   44.21   45.94   44.77   45.16    44.2   44.29   44.82   47.44   48.36   48.25
    66.6   60.35    43.6    42.3   41.55   40.12   40.04   39.81   39.81    40.4
   40.52    37.4   40.76    40.6   34.96   40.11   39.63   39.63   39.29   40.68
   39.71   39.25    39.1      40    43.5    43.5   42.43    40.4    39.5    41.5
      39    40.8    40.7    42.3    42.2    40.6    42.4    41.2    42.2    42.3
    41.7    41.6    43.5   47.06   48.23   45.43   44.91   44.11   45.61   44.85
   44.21   45.94   44.77   45.16    44.2   44.29   44.82   47.44   48.36   48.25
  3893.2  3979.5  4214.6  4463.3  4534.5  4671.5  4711.8 4782.99  4783.1  4850.5
  4938.8 4948.71  4948.8 5047.32 5047.43  5060.8  5135.9 5136.01  5188.8  5263.1
  5397.5  5740.1  5812.1  6123.5  6313.2  6338.2  6356.1  6378.2  6433.2  6558.2
  6713.2  6818.2  6868.2  6923.2  6948.2  7003.2  7068.2  7173.2  7188.2  7208.2
  7263.2  7706.5  8366.5  8746.5    9315    9355  9426.5  9856.5  9896.5  9946.5
  9964.5 10054.5 10364.5 10424.5 10464.5 10544.5 10594.5 10634.5 10674.5 10692.6
    66.6    67.8   57.72   47.05      44    42.3    41.8   42.07   44.07    44.4
   44.67   44.66   44.66    44.5    44.5   44.48   44.05   42.05   41.74   40.98
   40.21    43.8   43.72   43.34   43.53   43.57    43.6    40.4    39.5    41.5
      39    40.8    40.7    42.3    42.2    40.6    42.4    41.2    42.2    42.3
    41.7    41.6    43.5   47.06   48.23   45.43   44.91   44.11   45.61   44.85
   44.21   45.94   44.77   45.16    44.2   44.29   44.82   47.44   48.36   48.25
    66.5   60.25    43.5    42.2   41.45   40.02   39.94   39.71   39.71    40.3
   40.42    37.3   40.66    40.5   34.86   40.01   39.53   39.53   39.19   40.58
   39.61   39.15      39    39.9    43.4    43.4   42.33    40.3    39.4    41.4
    38.9    40.7    40.6    42.2    42.1    40.5    42.3    41.1    42.1    42.2
    41.6    41.5    43.4   46.96   48.13   45.33   44.81   44.01   45.51   44.75
   44.11   45.84   44.67   45.06    44.1   44.19   44.72   47.34   48.26   48.15
Pier Skew, UpSta & Num, DnSta & Num=  ,4972.2, 2 ,4972.2, 2 , 0 , 0 , 0 ,,
     1.4     1.4
   29.42   41.72
     1.4     1.4
   29.32   41.62
Pier Skew, UpSta & Num, DnSta & Num=  ,4991.4, 2 ,4991.4, 2 , 0 , 0 , 0 ,,
     1.4     1.4
   24.89   41.69
     1.4     1.4
   24.79   41.59
Pier Skew, UpSta & Num, DnSta & Num=  ,5011.3, 2 ,5011.3, 2 , 0 , 0 , 0 ,,
     1.4     1.4
   25.15   41.66
     1.4     1.4
   25.05   41.56
Pier Skew, UpSta & Num, DnSta & Num=  ,5029, 2 ,5029, 2 , 0 , 0 , 0 ,,
     1.4     1.4
   27.11   41.63
     1.4     1.4
   27.01   41.53
Abutment Skew #Up #Dn= , 2 , 2
  4948.6  4990.3
   40.76   26.08
  4948.6  4990.3
   40.66   25.98
Abutment Skew #Up #Dn= , 2 , 2
 5026.64 5047.52
   27.77    40.6
 5026.64 5047.52
   27.67    40.5
BR Coef= 1 , 1 , 0 ,1.25, 0 ,,,0.8,0,2,0,
WSPro=,,,, 1 ,,,, 0 ,,,, 0 ,,,,-1 ,-1 ,-1 , 0 , 0 , 0 , 0 , 0
BR U #Sta/Elev= 108
  3893.2    66.6  3974.5   60.72  3979.5   60.35  3999.9   58.88  4208.2    43.8
  4214.6    43.6  4463.3    42.3  4534.5   41.55  4671.5   40.12  4711.3   40.04
  4711.8   40.04  4782.5   39.81 4782.99   39.81  4783.1   39.81 4783.21   39.81
  4784.9    39.8  4850.5    40.4  4851.8    40.4    4917    40.4  4922.2    40.4
  4933.5   40.48  4938.8   40.52 4948.71    37.4  4948.8   37.37  4963.9   32.62
  4965.8   32.52  4987.4   26.13  4988.8   25.92  4990.3   26.08  4990.9   26.15
  4993.2   25.65  4999.7   26.04  5008.4   25.94  5009.1   26.15  5014.6   26.15
  5014.7   26.12 5026.64   27.77  5027.8   27.93  5037.7   31.21 5047.32   34.92
 5047.43   34.96  5060.8   40.11  5061.6    40.1 5135.79   39.63  5135.9   39.63
 5136.01   39.63  5188.8   39.29  5189.6    39.3    5258   40.58  5263.1   40.68
  5326.7   40.38  5331.8   40.33  5397.5   39.71  5419.6    39.5  5477.6   39.54
  5672.1    39.4  5740.1   39.25  5812.1    39.1  5828.1    39.3    5832   39.31
    6000   39.71  6123.5      40  6159.9   40.67  6313.2    43.5  6338.2    43.5
  6353.2    42.7  6356.1   42.43  6378.2    40.4  6433.2    39.5  6558.2    41.5
  6713.2      39  6798.2    40.2  6818.2    40.8  6868.2    40.7  6923.2    42.3
  6948.2    42.2  7003.2    40.6  7068.2    42.4  7173.2    41.2  7188.2    42.2
  7208.2    42.3  7263.2    41.7  7496.5    41.9  7706.5    41.6  8366.5    43.5
  8446.5   44.41  8746.5   47.06  8999.9   47.42    9155   47.64    9315   48.23
    9335   46.99    9355   45.43  9426.5   44.91  9856.5   44.11  9896.5   45.61
  9946.5   44.85  9956.5   44.26  9964.5   44.21 10024.5    45.4 10054.5   45.94
 10364.5   44.77 10424.5   45.16 10464.5    44.2 10544.5   44.29 10594.5   44.82
 10634.5   47.44 10674.5   48.36 10692.6   48.25
BR U #Mann= 6
  3893.2      .2  3999.9     .09  4938.8    .015  5060.8     .09    6000      .2
  8999.9     .99
BR U Banks=4938.8,5060.8
BR D #Sta/Elev= 108
  3893.2    66.5  3974.5   60.62  3979.5   60.25  3999.9   58.78  4208.2    43.7
  4214.6    43.5  4463.3    42.2  4534.5   41.45  4671.5   40.02  4711.3   39.94
  4711.8   39.94  4782.5   39.71 4782.99   39.71  4783.1   39.71 4783.21   39.71
  4784.9    39.7  4850.5    40.3  4851.8    40.3    4917    40.3  4922.2    40.3
  4933.5   40.38  4938.8   40.42 4948.71    37.3  4948.8   37.27  4963.9   32.52
  4965.8   32.42  4987.4   26.03  4988.8   25.82  4990.3   25.98  4990.9   26.05
  4993.2   25.55  4999.7   25.94  5008.4   25.84  5009.1   26.05  5014.6   26.05
  5014.7   26.02 5026.64   27.67  5027.8   27.83  5037.7   31.11 5047.32   34.82
 5047.43   34.86  5060.8   40.01  5061.6      40 5135.79   39.53  5135.9   39.53
 5136.01   39.53  5188.8   39.19  5189.6    39.2    5258   40.48  5263.1   40.58
  5326.7   40.28  5331.8   40.23  5397.5   39.61  5419.6    39.4  5477.6   39.44
  5672.1    39.3  5740.1   39.15  5812.1      39  5828.1    39.2    5832   39.21
    6000   39.61  6123.5    39.9  6159.9   40.57  6313.2    43.4  6338.2    43.4
  6353.2    42.6  6356.1   42.33  6378.2    40.3  6433.2    39.4  6558.2    41.4
  6713.2    38.9  6798.2    40.1  6818.2    40.7  6868.2    40.6  6923.2    42.2
  6948.2    42.1  7003.2    40.5  7068.2    42.3  7173.2    41.1  7188.2    42.1
  7208.2    42.2  7263.2    41.6  7496.5    41.8  7706.5    41.5  8366.5    43.4
  8446.5   44.31  8746.5   46.96  8999.9   47.32    9155   47.54    9315   48.13
    9335   46.89    9355   45.33  9426.5   44.81  9856.5   44.01  9896.5   45.51
  9946.5   44.75  9956.5   44.16  9964.5   44.11 10024.5    45.3 10054.5   45.84
 10364.5   44.67 10424.5   45.06 10464.5    44.1 10544.5   44.19 10594.5   44.72
 10634.5   47.34 10674.5   48.26 10692.6   48.15
BR D #Mann= 6
  3893.2      .2  3999.9     .09  4938.8    .015  5060.8     .09    6000      .2
  8999.9     .99
BR D Banks=4938.8,5060.8
BC Design=,, 0 ,, 0 ,,,,,,
BC HTab HWMax=66.61
BC Use User HTab Curves=0
BC User HTab FreeFlow(D)= 0