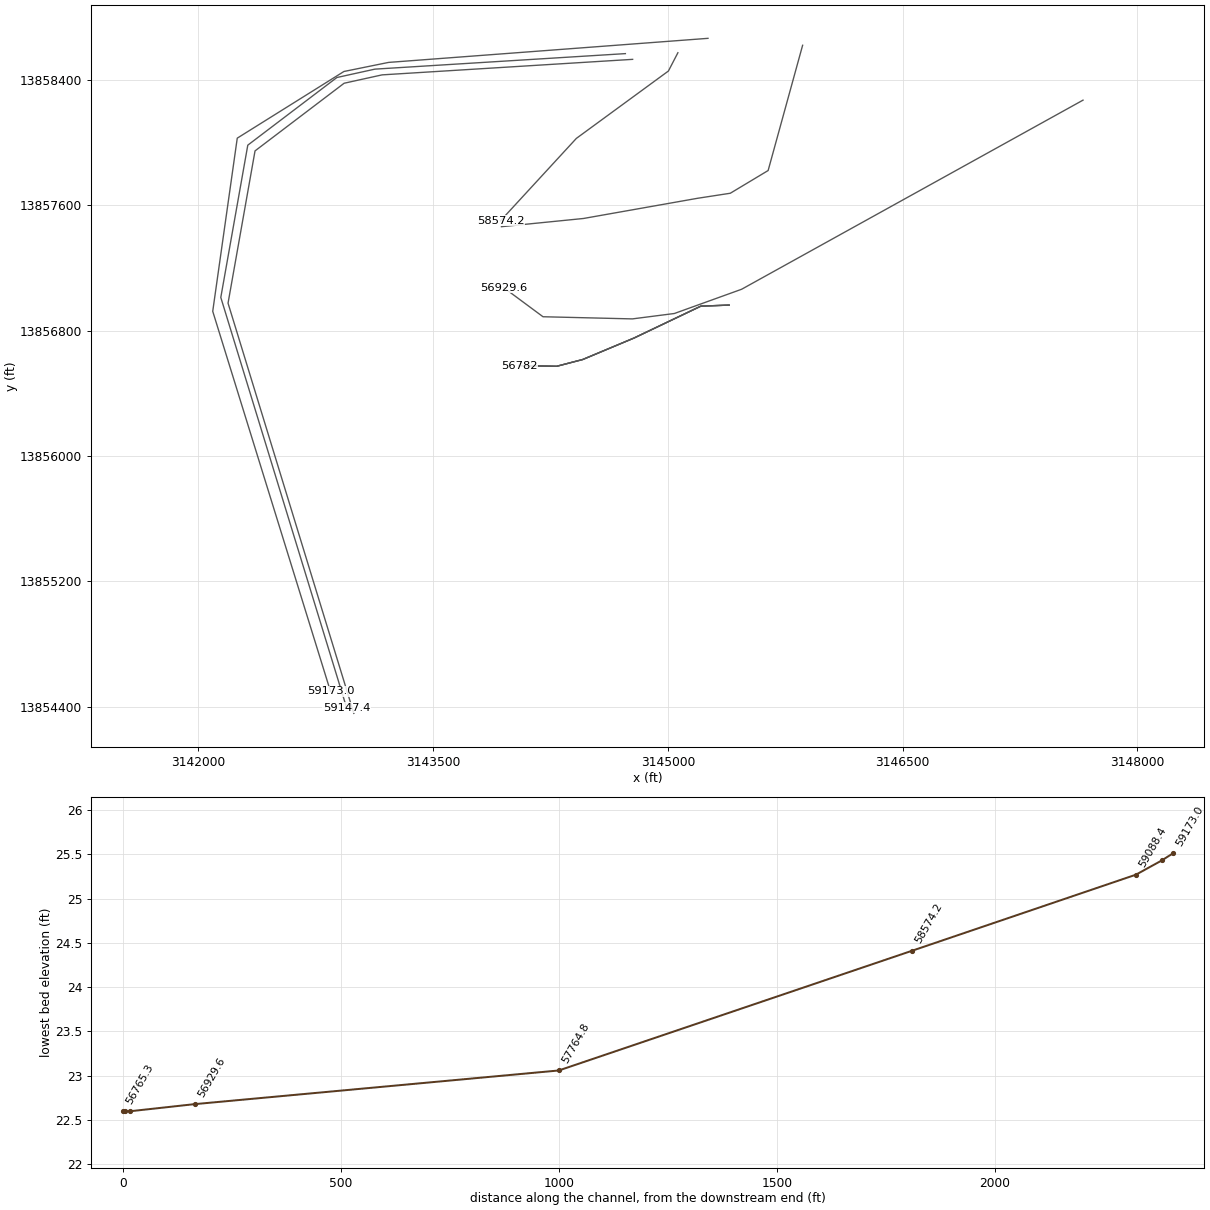
HEC-RAS study H100-00-00.prj: H100-00-00

--- H100-00-00.g01 (geometry) --- (continued)

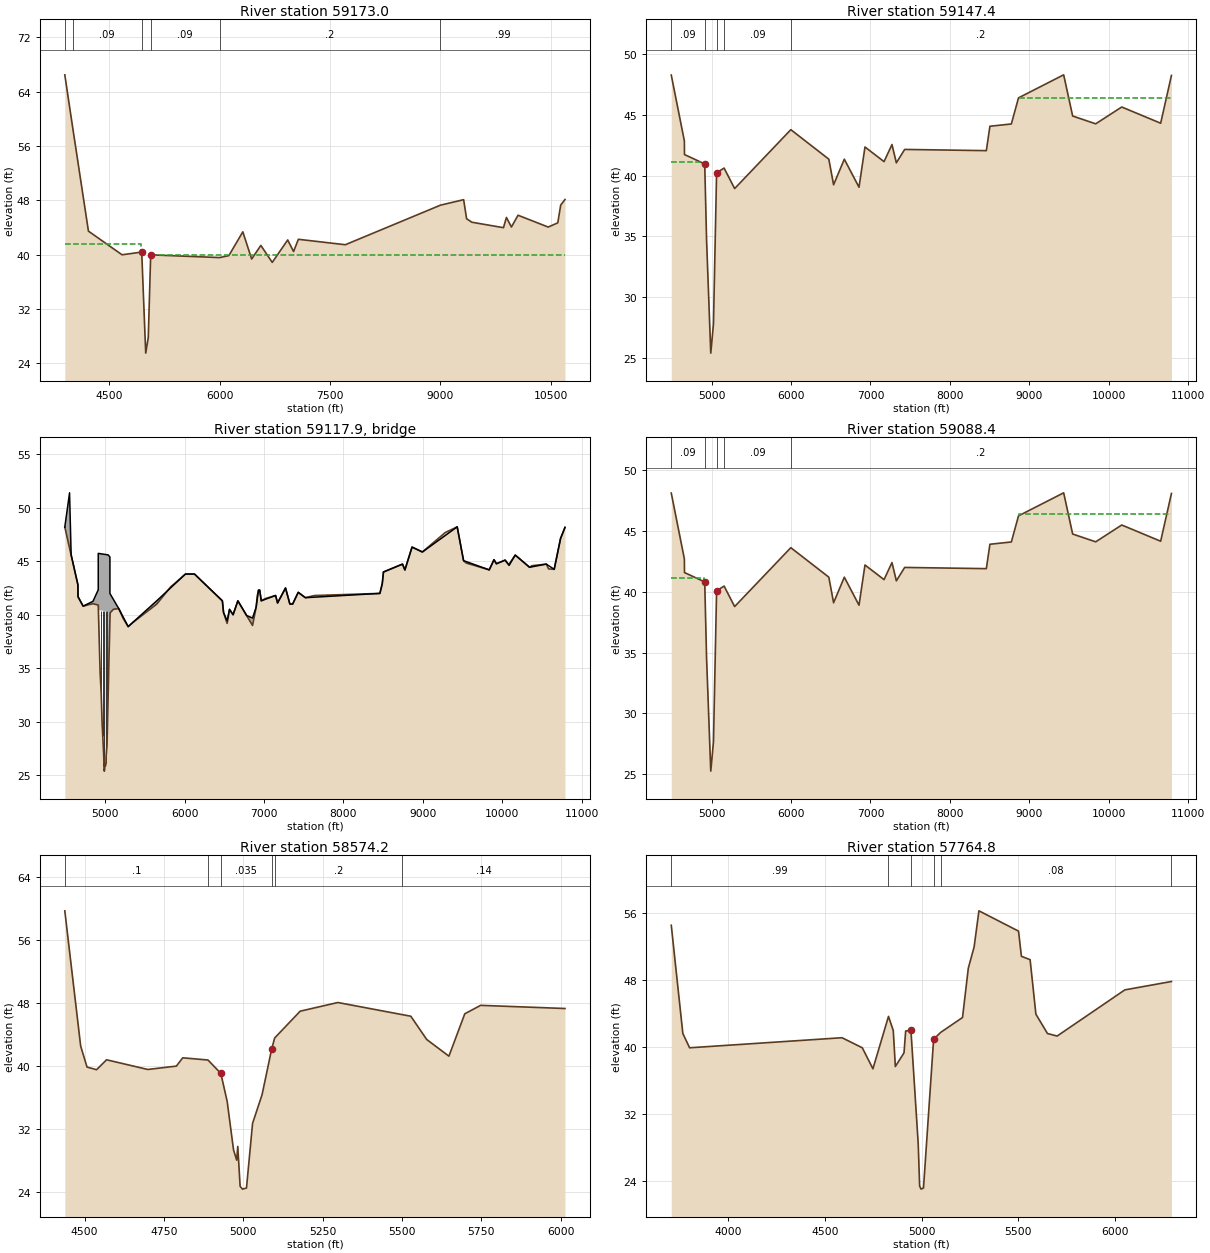
Type RM Length L Ch R = 1 ,59173.0 ,25.6,25.6,25.6
BEGIN DESCRIPTION:
Downstream Section of Bridge/Culvert/Weir
END DESCRIPTION:
XS GIS Cut Line= 6
      3145256.63       13858666.      3143215.03     13858512.29
      3142929.86     13858454.37      3142248.14     13858028.76
      3142091.34     13856923.31      3142843.53     13854498.34
#Sta/Elev= 30
  3893.2   66.46  3999.9   58.74  4214.6   43.46  4671.5   39.98  4938.8   40.38
  4993.2   25.51  5027.8   27.79  5060.8   39.97    6000   39.57  6123.5   39.86
  6313.2   43.36  6433.2   39.36  6558.2   41.36  6713.2   38.86  6923.2   42.16
  7003.2   40.46  7068.2   42.26  7706.5   41.46  8999.9   47.28    9315   48.09
    9355   45.29  9426.5   44.77  9856.5   43.97  9896.5   45.47  9964.5   44.07
 10054.5    45.8 10464.5   44.06 10594.5   44.68 10634.5    47.3 10692.6   48.11
#Mann= 6 , 1 , 0
  3893.2      .2       0  3999.9     .09       0  4938.8    .015       0
  5060.8     .09       0    6000      .2       0  8999.9     .99       0
#XS Ineff= 2 , 0
       0    4930    41.6    5070       0      40
Permanent Ineff=
       F       F
Bank Sta=4938.8,5060.8
XS Rating Curve= 0 ,0
Exp/Cntr=0.5,0.3

Type RM Length L Ch R = 1 ,59147.4 ,59,59,59
BEGIN DESCRIPTION:
Upstream Section of Bridge/Culvert/Weir
END DESCRIPTION:
XS GIS Cut Line= 6
      3144728.69     13858568.44      3143127.67     13858469.37
      3142884.83     13858415.91      3142315.44     13857984.01
      3142142.96     13857011.84      3142946.86     13854393.07
#Sta/Elev= 30
  4492.4   48.24  4657.4   42.84    4659   41.72  4913.6   40.95  4937.1   34.67
  4989.7   25.43  5023.7   27.82    5063   40.22  5157.3   40.61  5290.3   38.93
  5997.6   43.76    6476   41.34    6536   39.24    6671   41.34    6856   39.04
    6931   42.34    7171   41.14    7271   42.54    7326   41.04    7431   42.14
  8458.8   42.04  8503.8   44.04  8773.8   44.23  8863.8   46.37  9432.3   48.26
  9545.6   44.88  9835.6   44.24 10163.3   45.62 10653.3   44.29 10789.2   48.21
#Mann= 5 , 1 , 0
  4492.4     .09       0  4913.6    .035       0    5063     .07       0
  5157.3     .09       0  5997.6      .2       0
#XS Ineff= 2 , 0
       0    4910    41.1    8870       0    46.4
Permanent Ineff=
       F       F
Bank Sta=4913.6,5063
XS Rating Curve= 0 ,0
Exp/Cntr=0.5,0.3

Type RM Length L Ch R = 3 ,59117.9 ,,,
BEGIN DESCRIPTION:
IH 610-ACCESS ROAD EAST - 40 Degree Skew
Structure ID: H00-45
END DESCRIPTION:
Bridge Culvert--1,0,-1,-1, 0
Deck Dist Width WeirC Skew NumUp NumDn MinLoCord MaxHiCord MaxSubmerge Is_Ogee
10,39,2.6,0, 60, 60, , , 0.95, 0, 1,1,,
  4492.4  4552.3  4572.3  4657.4    4659  4723.4  4846.9 4913.49  4913.6 4922.83
 4922.92 5037.85 5037.96  5060.4 5060.51    5063  5170.9  5290.3  5648.7  6010.6
  6125.6    6476    6491    6536    6566    6611    6671  6781.9    6856    6901
    6931    6946    6966    7146    7171    7271    7326    7361    7431    7521
  8458.8  8488.8  8503.8  8743.8  8773.8  8863.8  8993.8  9432.3  9512.3  9835.6
  9895.6  9925.6 10035.6 10085.6 10163.3 10343.3 10553.3 10653.3 10733.3 10789.2
    48.2    51.4    45.6   42.81   41.69   40.81   41.26   42.34   45.74   45.73
   45.73    45.6    45.6    45.4      42   41.96   40.59    38.9    41.3   43.81
   43.81   41.31   40.21   39.44   40.51   40.01   41.31   39.93    39.7   40.71
   42.31   42.31   41.31   41.81   41.11   42.51   41.01   41.01    42.1    41.6
      42    42.9      44   44.74   44.19   46.33   45.87   48.22   45.06    44.2
   45.15   44.77   45.11   44.63   45.58   44.44   44.74   44.25   47.13   48.17
    48.2   46.24   45.59    42.8   41.68    40.8   41.03   40.91   40.91   38.46
   40.43    40.3   32.59   39.41   39.44   40.18   40.58   38.89   40.99    43.8
    43.8    41.3    40.2    39.2    40.5      40    41.3   39.92      39    40.7
    42.3    42.3    41.3    41.8    41.1    42.5      41      41    42.1    41.6
      42    42.9      44   44.74   44.19   46.33   45.87   48.22   45.06    44.2
   45.15   44.77   45.11   44.63   45.58   44.44   44.74   44.25   47.13   48.17
  4492.4  4552.3  4572.3  4657.4    4659  4723.4  4846.9 4913.49  4913.6 4922.83
 4922.92 5037.85 5037.96  5060.4 5060.51    5063  5170.9  5290.3  5648.7  6010.6
  6125.6    6476    6491    6536    6566    6611    6671  6781.9    6856    6901
    6931    6946    6966    7146    7171    7271    7326    7361    7431    7521
  8458.8  8488.8  8503.8  8743.8  8773.8  8863.8  8993.8  9432.3  9512.3  9835.6
  9895.6  9925.6 10035.6 10085.6 10163.3 10343.3 10553.3 10653.3 10733.3 10789.2
    48.2    51.4    45.6   42.81   41.69   40.81   41.26   42.34   45.74   45.73
   45.73    45.6    45.6    45.4      42   41.96   40.59    38.9    41.3   43.81
   43.81   41.31   40.21   39.44   40.51   40.01   41.31   39.93    39.7   40.71
   42.31   42.31   41.31   41.81   41.11   42.51   41.01   41.01    42.1    41.6
      42    42.9      44   44.74   44.19   46.33   45.87   48.22   45.06    44.2
   45.15   44.77   45.11   44.63   45.58   44.44   44.74   44.25   47.13   48.17
    48.1   46.14   45.49    42.7   41.58    40.7   40.93   40.81   40.81   38.36
   40.33    40.2   32.49   39.31   39.34   40.08   40.48   38.79   40.89    43.7
    43.7    41.2    40.1    39.1    40.4    39.9    41.2   39.82    38.9    40.6
    42.2    42.2    41.2    41.7      41    42.4    40.9    40.9      42    41.5
    41.9    42.8    43.9   44.64   44.09   46.23   45.77   48.12   44.96    44.1
   45.05   44.67   45.01   44.53   45.48   44.34   44.64   44.15   47.03   48.07
Pier Skew, UpSta & Num, DnSta & Num=  ,4951.6, 2 ,4951.6, 2 , 0 , 0 , 0 ,,
     1.4     1.4
   31.26    41.4
     1.4     1.4
   31.16    41.3
Pier Skew, UpSta & Num, DnSta & Num=  ,4970.7, 2 ,4970.7, 2 , 0 , 0 , 0 ,,
     1.4     1.4
   27.53   41.38
     1.4     1.4
   27.43   41.28
Pier Skew, UpSta & Num, DnSta & Num=  ,4989.8, 2 ,4989.8, 2 , 0 , 0 , 0 ,,
     1.4     1.4
   24.46   41.36
     1.4     1.4
   24.36   41.26
Pier Skew, UpSta & Num, DnSta & Num=  ,5009.5, 2 ,5009.5, 2 , 0 , 0 , 0 ,,
     1.4     1.4
   25.08   41.33
     1.4     1.4
   24.98   41.23
Pier Skew, UpSta & Num, DnSta & Num=  ,5028.6, 2 ,5028.6, 2 , 0 , 0 , 0 ,,
     1.4     1.4
   28.21   41.32
     1.4     1.4
   28.11   41.22
Abutment Skew #Up #Dn= , 2 , 2
 4922.72 4985.45
   40.43   26.16
 4922.72 4985.45
   40.33   26.06
Abutment Skew #Up #Dn= , 2 , 2
 5033.65 5038.05
   31.14    40.3
 5033.65 5038.05
   31.04    40.2
BR Coef= 1 , 1 , 0 ,1.25, 0 ,,,0.8,0,2,0,
WSPro=,,,, 1 ,,,, 0 ,,,, 0 ,,,,-1 ,-1 ,-1 , 0 , 0 , 0 , 0 , 0
BR U #Sta/Elev= 139
  4492.4    48.2  4552.3   46.24  4562.3   45.91  4572.3   45.59  4582.3   45.26
  4607.3   44.44  4632.3   43.62  4635.2   43.53  4655.2   42.87  4657.4    42.8
  4658.9   41.75    4659   41.68  4723.4    40.8  4726.4   40.81  4787.1   40.94
  4789.5   40.94  4846.9   41.03    4848   41.03  4899.9   40.94 4913.49   40.91
  4913.6   40.91  4913.7   40.91 4913.81   40.88 4922.83   38.46 4922.92   38.44
  4937.1   34.63  4950.4   32.71    4962   29.91  4981.1   27.11 4985.45   26.16
  4986.7   25.89  4989.2    26.1  4989.7   25.39    4997   26.03  5004.8   25.89
  5010.8   26.17  5012.4   26.77  5023.7   27.78 5033.65   31.14  5037.2   32.34
 5037.85   32.56 5037.96   32.59  5042.8   34.21  5049.3   36.13 5060.29   39.38
  5060.4   39.41 5060.51   39.44    5063   40.18  5101.2   40.49  5105.3   40.52
  5157.3   40.57  5168.7   40.58  5170.9   40.58  5229.1   39.64  5229.3   39.64
  5286.7   38.93  5290.3   38.89  5344.3   39.25  5585.2   40.63  5645.2   40.97
  5648.7   40.99  5649.9      41  5737.7   41.81  5823.7    42.6  5827.7   42.63
  5837.7   42.69  5842.7   42.72  5852.7   42.79  5861.5   42.84  5866.5   42.87
  5881.5   42.97  5886.5      43  5896.5   43.07  5911.5   43.16  5916.5    43.2
  5926.5   43.26  5936.5   43.32  5941.5   43.36  5946.5   43.39  5956.5   43.45
  5966.5   43.52  5981.5   43.61  5992.9   43.69  5997.6   43.72  5997.9   43.72
  6010.6    43.8  6125.6    43.8    6175   43.45  6300.1   42.55    6476    41.3
    6491    40.2    6536    39.2    6566    40.5    6611      40    6671    41.3
  6781.9   39.92    6856      39    6901    40.7    6916    41.8    6931    42.3
    6946    42.3    6966    41.3  7003.3   41.47    7011    41.5    7146    41.8
    7171    41.1    7271    42.5  7322.5    41.1    7326      41    7361      41
  7429.6   42.08    7431    42.1    7521    41.6  7633.8    41.8  8458.8      42
  8488.8    42.9  8503.8      44  8743.8   44.74  8773.8   44.19  8863.8   46.33
  8993.8   45.87  9282.3   47.69  9432.3   48.22  9512.3   45.06  9545.6   44.84
  9835.6    44.2  9895.6   45.15  9925.6   44.77 10035.6   45.11 10085.6   44.63
 10093.3   44.82 10163.3   45.58 10343.3   44.44 10373.3   44.59 10553.3   44.74
 10583.3   44.29 10653.3   44.25 10733.3   47.13 10789.2   48.17
BR U #Mann= 5
  4492.4     .09  4913.6    .035    5063     .07  5157.3     .09  5997.6      .2
BR U Banks=4913.6,5063
BR D #Sta/Elev= 139
  4492.4    48.1  4552.3   46.14  4562.3   45.81  4572.3   45.49  4582.3   45.16
  4607.3   44.34  4632.3   43.52  4635.2   43.43  4655.2   42.77  4657.4    42.7
  4658.9   41.65    4659   41.58  4723.4    40.7  4726.4   40.71  4787.1   40.84
  4789.5   40.84  4846.9   40.93    4848   40.93  4899.9   40.84 4913.49   40.81
  4913.6   40.81  4913.7   40.81 4913.81   40.78 4922.83   38.36 4922.92   38.34
  4937.1   34.53  4950.4   32.61    4962   29.81  4981.1   27.01 4985.45   26.06
  4986.7   25.79  4989.2      26  4989.7   25.29    4997   25.93  5004.8   25.79
  5010.8   26.07  5012.4   26.67  5023.7   27.68 5033.65   31.04  5037.2   32.24
 5037.85   32.46 5037.96   32.49  5042.8   34.11  5049.3   36.03 5060.29   39.28
  5060.4   39.31 5060.51   39.34    5063   40.08  5101.2   40.39  5105.3   40.42
  5157.3   40.47  5168.7   40.48  5170.9   40.48  5229.1   39.54  5229.3   39.54
  5286.7   38.83  5290.3   38.79  5344.3   39.15  5585.2   40.53  5645.2   40.87
  5648.7   40.89  5649.9    40.9  5737.7   41.71  5823.7    42.5  5827.7   42.53
  5837.7   42.59  5842.7   42.62  5852.7   42.69  5861.5   42.74  5866.5   42.77
  5881.5   42.87  5886.5    42.9  5896.5   42.97  5911.5   43.06  5916.5    43.1
  5926.5   43.16  5936.5   43.22  5941.5   43.26  5946.5   43.29  5956.5   43.35
  5966.5   43.42  5981.5   43.51  5992.9   43.59  5997.6   43.62  5997.9   43.62
  6010.6    43.7  6125.6    43.7    6175   43.35  6300.1   42.45    6476    41.2
    6491    40.1    6536    39.1    6566    40.4    6611    39.9    6671    41.2
  6781.9   39.82    6856    38.9    6901    40.6    6916    41.7    6931    42.2
    6946    42.2    6966    41.2  7003.3   41.37    7011    41.4    7146    41.7
    7171      41    7271    42.4  7322.5      41    7326    40.9    7361    40.9
  7429.6   41.98    7431      42    7521    41.5  7633.8    41.7  8458.8    41.9
  8488.8    42.8  8503.8    43.9  8743.8   44.64  8773.8   44.09  8863.8   46.23
  8993.8   45.77  9282.3   47.59  9432.3   48.12  9512.3   44.96  9545.6   44.74
  9835.6    44.1  9895.6   45.05  9925.6   44.67 10035.6   45.01 10085.6   44.53
 10093.3   44.72 10163.3   45.48 10343.3   44.34 10373.3   44.49 10553.3   44.64
 10583.3   44.19 10653.3   44.15 10733.3   47.03 10789.2   48.07
BR D #Mann= 5
  4492.4     .09  4913.6    .035    5063     .07  5157.3     .09  5997.6      .2
BR D Banks=4913.6,5063
BC Design=,, 0 ,, 0 ,,,,,,
BC HTab HWMax=48.26
BC Use User HTab Curves=0
BC User HTab FreeFlow(D)= 0

Type RM Length L Ch R = 1 ,59088.4 ,514.2,514.2,514.2
BEGIN DESCRIPTION:
Downstream Section of Bridge/Culvert/Weir
END DESCRIPTION:
XS GIS Cut Line= 6
      3144774.98     13858531.85      3143173.95     13858432.79
      3142931.11     13858379.33      3142361.72     13857947.43
      3142189.24     13856975.26      3142993.14     13854356.48
#Sta/Elev= 30
  4492.4   48.08  4657.4   42.68    4659   41.56  4913.6   40.79  4937.1   34.51
  4989.7   25.27  5023.7   27.66    5063   40.06  5157.3   40.45  5290.3   38.77
  5997.6    43.6    6476   41.18    6536   39.08    6671   41.18    6856   38.88
    6931   42.18    7171   40.98    7271   42.38    7326   40.88    7431   41.98
  8458.8   41.88  8503.8   43.88  8773.8   44.07  8863.8   46.21  9432.3    48.1
  9545.6   44.72  9835.6   44.08 10163.3   45.46 10653.3   44.13 10789.2   48.05
#Mann= 5 , 1 , 0
  4492.4     .09       0  4913.6    .035       0    5063     .07       0
  5157.3     .09       0  5997.6      .2       0
#XS Ineff= 2 , 0
       0    4910    41.1    8870       0    46.4
Permanent Ineff=
       F       F
Bank Sta=4913.6,5063
XS Rating Curve= 0 ,0
Exp/Cntr=0.5,0.3

Type RM Length L Ch R = 1 ,58574.2 ,1002.8,809.4,714.7
BEGIN DESCRIPTION:
Cross Section 58574.2
END DESCRIPTION:
XS GIS Cut Line= 4
      3145064.26       13858574.      3145003.65     13858457.26
      3144415.41     13858027.26      3143930.38     13857500.95
#Sta/Elev= 30
  4437.6   59.74  4487.6   42.57  4507.6   39.91  4537.6   39.57  4569.2   40.83
  4699.2    39.6  4789.2   40.03  4809.2   41.08  4888.7    40.8  4929.2   39.11
  4949.2   35.54  4969.2    29.4  4979.2   28.09  4982.6   29.83    4990   24.77
  4997.4   24.41    5010   24.55  5029.2   32.76  5059.2   36.41  5089.2   42.16
  5098.7   43.59  5179.2      47  5297.8    48.1  5499.7   46.57  5527.8   46.36
  5577.8   43.41  5647.8   41.29  5697.8   46.67  5747.8   47.74  6013.5   47.34
#Mann= 6 , 1 , 0
  4437.6      .1       0  4888.7     .07       0  4929.2    .035       0
  5089.2     .07       0  5098.7      .2       0  5499.7     .14       0
Bank Sta=4929.2,5089.2
XS Rating Curve= 0 ,0
Exp/Cntr=0.3,0.1

Type RM Length L Ch R = 1 ,57764.8 ,932.8,835.2,823.2
BEGIN DESCRIPTION:
Cross Section 57764.8
END DESCRIPTION:
XS GIS Cut Line= 6
      3145861.46     13858621.73      3145641.01      13857822.1
      3145399.25     13857677.05      3145189.73     13857644.81
      3144460.43     13857515.88      3143936.62      13857463.5
#Sta/Elev= 30
  3703.7    54.5  3763.7    41.6  3798.7    39.9  4588.1    41.1  4693.1    39.9
  4748.1    37.4  4828.7   43.64  4853.5   41.95  4864.2   37.67  4909.1    39.3
  4917.6    41.9  4944.9   41.99  4982.6   28.48    4990   23.42  4997.4   23.06
    5010    23.2  5062.4   40.92  5098.7   41.73  5212.1   43.51  5242.1   49.39
  5272.1   51.91  5297.1   56.22  5502.1    53.8  5517.1    50.8  5562.1    50.4
  5592.1    43.9  5652.1    41.6  5702.1    41.3  6052.7    46.8  6294.1    47.8
#Mann= 6 , 1 , 0
  3703.7     .99       0  4828.7     .07       0  4944.9    .035       0
  5062.4     .07       0  5098.7     .08       0  6294.1     .14       0
Bank Sta=4944.9,5062.4
XS Rating Curve= 0 ,0
Exp/Cntr=0.3,0.1

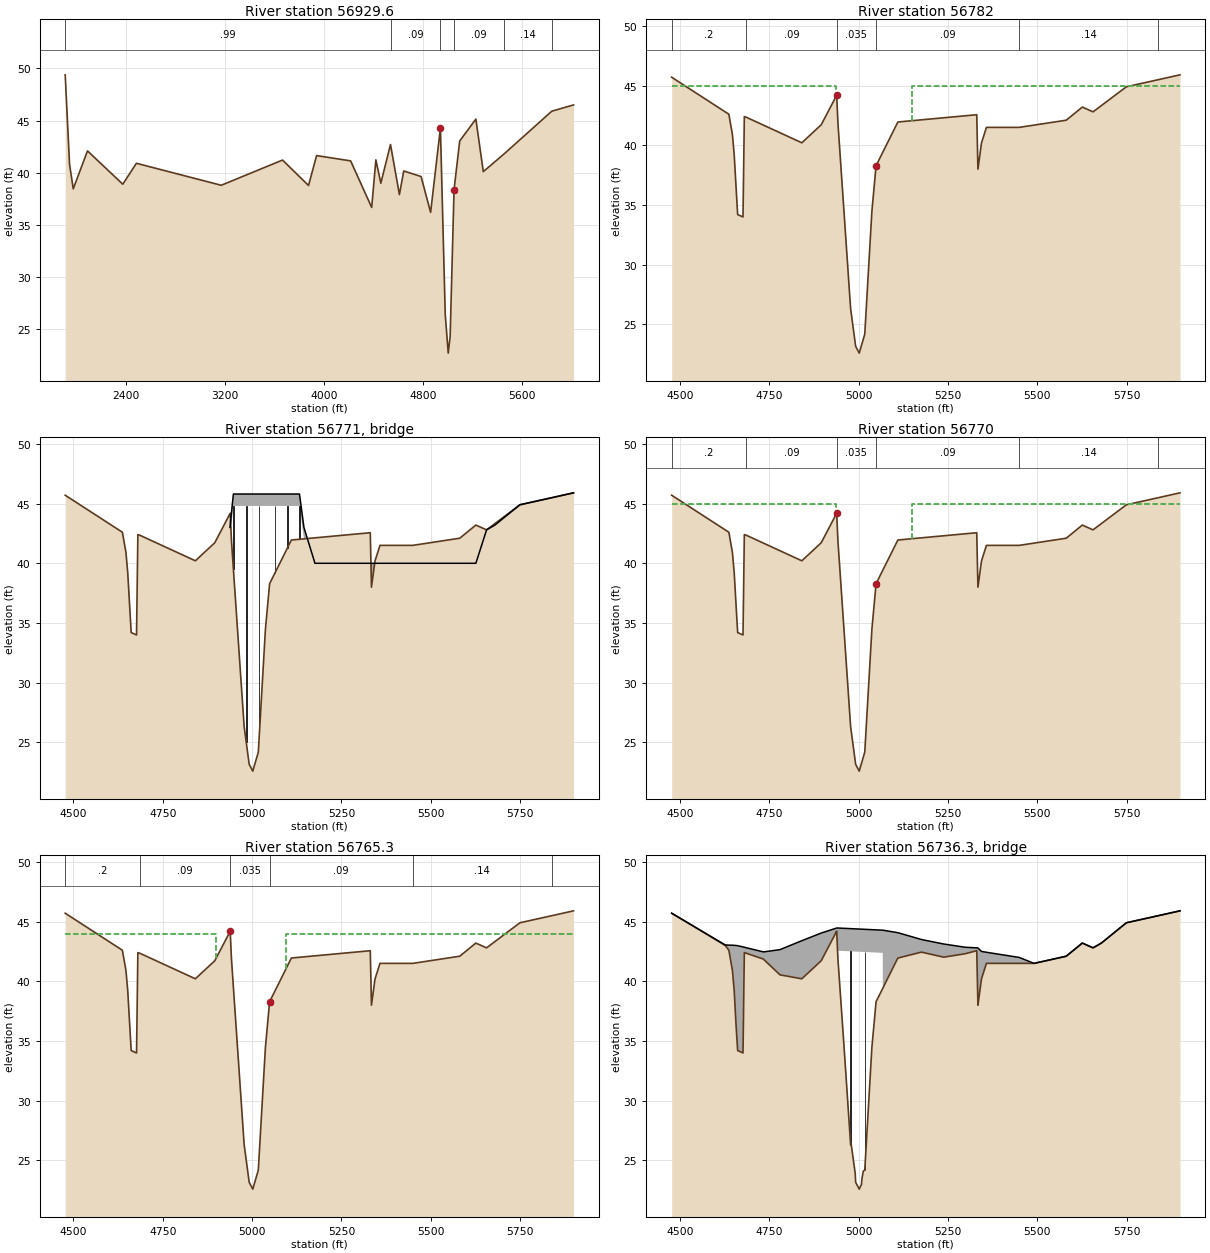
Type RM Length L Ch R = 1 ,56929.6 ,64,147.6,209
BEGIN DESCRIPTION:
Cross Section 56929.6
END DESCRIPTION:
XS GIS Cut Line= 6
      3147653.55     13858271.45      3145471.48     13857064.07
      3145041.49     13856909.27      3144773.17     13856874.87
      3144202.14     13856888.63      3143951.02     13857074.39
#Sta/Elev= 30
  1908.8   49.39  1943.8   40.81  1973.8   38.45  2088.8   42.09  2373.8   38.89
  2483.8    40.9  3168.8   38.79  3663.8   41.21  3873.8   38.77  3938.8   41.64
  4213.8   41.13  4383.8   36.66  4417.6   41.23  4457.6   38.99  4535.7    42.7
  4607.6    37.9  4642.6   40.16  4782.6   39.63  4859.6   36.19  4938.7   44.27
  4977.7    26.4  5001.8   22.68  5017.3   24.27  5048.9   38.37  5094.6   43.04
  5225.1   45.14  5285.1    40.1  5449.2   41.76  5838.2    45.9  6013.7    46.5
#Mann= 6 ,-1 , 0
  1908.8     .99       0  4535.7     .09       0  4938.7    .035       0
  5048.9     .09       0  5449.2     .14       0  5838.2      .2       0
Bank Sta=4938.7,5048.9
XS Rating Curve= 0 ,0
Exp/Cntr=0.3,0.1

Type RM Length L Ch R = 1 ,56782   ,12,12,12
BEGIN DESCRIPTION:
Upstream Section of Waterline
END DESCRIPTION:
XS GIS Cut Line= 6
      3145391.83     13856963.01      3145211.12     13856956.31
      3144783.68     13856752.61      3144456.42      13856615.7
      3144289.45     13856572.28      3144048.97     13856576.84
#Sta/Elev= 30
    4477    45.7    4637    42.6    4647    40.9    4652    39.2  4661.6    34.2
  4676.6      34  4680.3    42.4  4685.7   42.35  4841.2   40.21  4895.5   41.72
  4938.7   44.19  4942.2   41.87  4977.7   26.32  4991.8   23.17  5001.8    22.6
  5017.3   24.19  5037.2   34.47  5048.9   38.29  5109.9   41.95  5330.6   42.56
  5333.9      38  5343.9    40.2  5357.7    41.5  5449.2    41.5    5581    42.1
    5626    43.2    5656    42.8  5749.3    44.9  5838.2   45.49  5899.3    45.9
#Mann= 6 ,-1 , 0
    4477      .2       0  4685.7     .09       0  4938.7    .035       0
  5048.9     .09       0  5449.2     .14       0  5838.2      .2       0
#XS Ineff= 2 , 0
       0    4938      45    5150       0      45
Permanent Ineff=
       F       F
Bank Sta=4938.7,5048.9
XS Rating Curve= 0 ,0
Exp/Cntr=0.5,0.3

Type RM Length L Ch R = 3 ,56771   ,,,
BEGIN DESCRIPTION:
Proposed 12-in waterline
END DESCRIPTION:
Bridge Culvert--1,0,-1,-1, 0
Deck Dist Width WeirC Skew NumUp NumDn MinLoCord MaxHiCord MaxSubmerge Is_Ogee
10,1,2.6,0, 44, 46, , , 0.95, 0, 0,1,,
    4938 4947.54  4959.8  4969.1    4971  4979.1  4990.6  4991.8  5001.8    5008
  5009.4  5013.1  5017.3    5033  5037.2  5048.9 5057.71  5057.8 5067.59  5067.8
  5100.2  5109.9  5111.9 5132.54    5145  5175.8  5238.6  5296.8  5298.6  5330.6
  5333.7  5333.9  5343.7  5343.9  5357.7  5449.2    5491    5581    5626    5656
  5679.3  5749.3  5838.2  5899.3
      43    45.8    45.8    45.8    45.8    45.8    45.8    45.8    45.8    45.8
    45.8    45.8    45.8    45.8    45.8    45.8    45.8    45.8    45.8    45.8
    45.8    45.8    45.8    45.8      43      40      40      40      40      40
      40      40      40      40      40      40      40      40      40    42.8
    43.2    44.9   45.49    45.9
      42    44.8    44.8    44.8    44.8    44.8    44.8    44.8    44.8    44.8
    44.8    44.8    44.8    44.8    44.8    44.8    44.8    44.8    44.8    44.8
    44.8    44.8    44.8    44.8      42      38      38      38      38      38
      38      38      38      38      38      38      38      38      38    42.8
    43.2    44.9   45.49    45.9
    4938  4938.7 4947.54  4959.8  4969.1    4971  4979.1  4990.6  4991.8  5001.8
    5008  5009.4  5013.1  5017.3    5033  5037.2  5048.9 5057.71  5057.8 5067.59
  5067.8  5100.2  5109.9  5111.9 5132.54    5145  5175.8  5238.4  5238.6  5296.8
  5298.6  5330.6  5333.7  5333.9  5343.7  5343.9  5357.7  5449.2    5491    5581
    5626    5656  5679.3  5749.3  5838.2  5899.3
      43      43    45.8    45.8    45.8    45.8    45.8    45.8    45.8    45.8
    45.8    45.8    45.8    45.8    45.8    45.8    45.8    45.8    45.8    45.8
    45.8    45.8    45.8    45.8    45.8      43      40      40      40      40
      40      40      40      40      40      40      40      40      40      40
      40    42.8    43.2    44.9   45.49    45.9
      42      42    44.8    44.8    44.8    44.8    44.8    44.8    44.8    44.8
    44.8    44.8    44.8    44.8    44.8    44.8    44.8    44.8    44.8    44.8
    44.8    44.8    44.8    44.8    44.8      42      38      38      38      38
      38      38      38      38      38      38      38      38      38      38
      38    42.8    43.2    44.9   45.49    45.9
Pier Skew, UpSta & Num, DnSta & Num=  ,4947.54, 2 ,4947.54, 2 , 0 , 0 , 0 ,,
     1.5     1.5
    22.5    45.9
     1.5     1.5
    22.5    45.9
Pier Skew, UpSta & Num, DnSta & Num=  ,4983.54, 2 ,4983.54, 2 , 0 , 0 , 0 ,,
     1.5     1.5
    22.5    45.9
     1.5     1.5
    22.5    45.9
Pier Skew, UpSta & Num, DnSta & Num=  ,5019.54, 2 ,5019.54, 2 , 0 , 0 , 0 ,,
     1.5     1.5
    22.5    45.9
     1.5     1.5
    22.5    45.9
Pier Skew, UpSta & Num, DnSta & Num=  ,5064.54, 2 ,5064.54, 2 , 0 , 0 , 0 ,,
     1.5     1.5
    22.5    45.9
     1.5     1.5
    22.5    45.9
Pier Skew, UpSta & Num, DnSta & Num=  ,5098.54, 2 ,5098.54, 2 , 0 , 0 , 0 ,,
     1.5     1.5
    22.5    45.9
     1.5     1.5
    22.5    45.9
Pier Skew, UpSta & Num, DnSta & Num=  ,5132, 2 ,5132, 2 , 0 , 0 , 0 ,,
     1.5     1.5
    22.5    45.9
     1.5     1.5
    22.5    45.9
BR Coef=-1 , 0 , 0 ,1.25, 0 ,,,0.8,-1,2,0,
WSPro=,,,, 1 ,,,, 0 ,,,, 0 ,,,,-1 ,-1 ,-1 , 0 , 0 , 0 , 0 , 0
BC Design=,, 0 ,, 0 ,,,,,,
BC HTab HWMax=49.39
BC Use User HTab Curves=0
BC User HTab FreeFlow(D)= 0

Type RM Length L Ch R = 1 ,56770   ,4.7,4.7,4.7
BEGIN DESCRIPTION:
Downstream Section of Waterline
END DESCRIPTION:
XS GIS Cut Line= 6
      3145391.83     13856963.01      3145211.12     13856956.31
      3144783.68     13856752.61      3144456.42      13856615.7
      3144289.45     13856572.28      3144048.97     13856576.84
#Sta/Elev= 30
    4477    45.7    4637    42.6    4647    40.9    4652    39.2  4661.6    34.2
  4676.6      34  4680.3    42.4  4685.7   42.35  4841.2   40.21  4895.5   41.72
  4938.7   44.19  4942.2   41.87  4977.7   26.32  4991.8   23.17  5001.8    22.6
  5017.3   24.19  5037.2   34.47  5048.9   38.29  5109.9   41.95  5330.6   42.56
  5333.9      38  5343.9    40.2  5357.7    41.5  5449.2    41.5    5581    42.1
    5626    43.2    5656    42.8  5749.3    44.9  5838.2   45.49  5899.3    45.9
#Mann= 6 ,-1 , 0
    4477      .2       0  4685.7     .09       0  4938.7    .035       0
  5048.9     .09       0  5449.2     .14       0  5838.2      .2       0
#XS Ineff= 2 , 0
       0    4938      45    5150       0      45
Permanent Ineff=
       F       F
Bank Sta=4938.7,5048.9
XS Rating Curve= 0 ,0
Exp/Cntr=0.5,0.3

Type RM Length L Ch R = 1 ,56765.3 ,58,58,58
BEGIN DESCRIPTION:
Upstream Section of Bridge/Culvert/Weir
END DESCRIPTION:
XS GIS Cut Line= 6
      3145391.83     13856963.01      3145211.12     13856956.31
      3144783.68     13856752.61      3144456.42      13856615.7
      3144289.45     13856572.28      3144048.97     13856576.84
#Sta/Elev= 30
    4477    45.7    4637    42.6    4647    40.9    4652    39.2  4661.6    34.2
  4676.6      34  4680.3    42.4  4685.7   42.35  4841.2   40.21  4895.5   41.72
  4938.7   44.19  4942.2   41.87  4977.7   26.32  4991.8   23.17  5001.8    22.6
  5017.3   24.19  5037.2   34.47  5048.9   38.29  5109.9   41.95  5330.6   42.56
  5333.9      38  5343.9    40.2  5357.7    41.5  5449.2    41.5    5581    42.1
    5626    43.2    5656    42.8  5749.3    44.9  5838.2   45.49  5899.3    45.9
#Mann= 6 ,-1 , 0
    4477      .2       0  4685.7     .09       0  4938.7    .035       0
  5048.9     .09       0  5449.2     .14       0  5838.2      .2       0
#XS Ineff= 2 , 0
       0    4900      44    5095       0      44
Permanent Ineff=
       F       F
Bank Sta=4938.7,5048.9
XS Rating Curve= 0 ,0
Exp/Cntr=0.5,0.3

Type RM Length L Ch R = 3 ,56736.3 ,,,
BEGIN DESCRIPTION:
LIBERTY ROAD
Structure ID: H00-44
END DESCRIPTION:
Bridge Culvert--1,0,-1,-1, 0
Deck Dist Width WeirC Skew NumUp NumDn MinLoCord MaxHiCord MaxSubmerge Is_Ogee
10,38,2.6,0, 33, 33, , , 0.95, 0, 1,1,,
    4477    4627    4637    4647    4652    4657  4661.6  4676.6  4680.3  4733.8
    4780  4841.2  4895.5  4938.7  4942.2 5067.59  5067.8  5109.9  5175.6  5238.6
  5298.6  5330.6  5333.9  5343.9  5357.7  5449.2    5491    5581    5626    5656
  5679.3  5749.3  5899.3
    45.7   43.04   43.03   43.02   43.01      43   42.98   42.88   42.85   42.46
   42.65    43.4   44.04   44.46   44.46   44.28   44.28   44.07    43.5   43.12
   42.85    42.8   42.79    42.5   42.43      42    41.5    42.1    43.2    42.8
    43.2    44.9    45.9
    45.7      43    42.6    40.9    39.2    36.4    34.2      34    42.4   41.85
   40.54   40.21   41.72   44.19   42.56   42.38   39.42   41.95   42.44   42.02
   42.31   42.56      38    40.2    41.5    41.5    41.5    42.1    43.2    42.8
    43.2    44.9    45.9
    4477    4627    4637    4647    4652    4657  4661.6  4676.6  4680.3  4733.8
    4780  4841.2  4895.5  4938.7  4942.2 5067.59  5067.8  5109.9  5175.6  5238.6
  5298.6  5330.6  5333.9  5343.9  5357.7  5449.2    5491    5581    5626    5656
  5679.3  5749.3  5899.3
    45.7   43.04   43.03   43.02   43.01      43   42.98   42.88   42.85   42.46
   42.65    43.4   44.04   44.46   44.46   44.28   44.28   44.07    43.5   43.12
   42.85    42.8   42.79    42.5   42.43      42    41.5    42.1    43.2    42.8
    43.2    44.9    45.9
    45.6    42.9    42.5    40.8    39.1    36.3    34.1    33.9    42.3   41.75
   40.44   40.11   41.62   44.09   42.46   42.28   39.32   41.85   42.34   41.92
   42.21   42.46    37.9    40.1    41.4    41.4    41.4      42    43.1    42.7
    43.1    44.8    45.8
Pier Skew, UpSta & Num, DnSta & Num=  ,4977.7, 2 ,4977.7, 2 , 0 , 0 , 0 ,,
     1.4     1.4
   25.36   43.52
     1.4     1.4
   25.26   43.42
Pier Skew, UpSta & Num, DnSta & Num=  ,5017.3, 2 ,5017.3, 2 , 0 , 0 , 0 ,,
     1.4     1.4
   23.18   43.47
     1.4     1.4
   23.08   43.37
Abutment Skew #Up #Dn= , 2 , 2
  4937.8  4969.1
   44.15   30.16
  4937.8  4969.1
   44.05   30.06
Abutment Skew #Up #Dn= , 2 , 2
  5033.1 5067.79
   32.35   42.38
  5033.1 5067.79
   32.25   42.28
BR Coef= 1 , 1 , 0 ,1.25, 0 ,,,0.8,0,2,0,
WSPro=,,,, 1 ,,,, 0 ,,,, 0 ,,,,-1 ,-1 ,-1 , 0 , 0 , 0 , 0 , 0
BR U #Sta/Elev= 73
    4477    45.7  4509.5   45.12    4627      43    4637    42.6    4647    40.9
    4652    39.2    4657    36.4  4659.5    35.2  4661.6    34.2  4676.6      34
  4680.3    42.4  4685.7   42.35  4733.5   41.86  4733.8   41.85  4779.4   40.56
    4780   40.54  4838.9   40.22  4841.2   40.21  4871.5   41.05  4895.5   41.72
  4901.8   42.08 4937.49   44.12  4937.6   44.13 4937.71   44.13  4937.8   44.14
 4937.91   44.14    4938   44.15  4938.7   44.19  4942.2   41.87  4959.8   34.31
  4969.1   30.16  4977.7   26.32  4979.1   26.41  4990.6    23.9  4991.8   23.17
  5001.8    22.6    5008   22.99  5009.4   23.48  5013.1   24.11  5017.3   24.19
    5033    32.3  5037.2   34.47  5048.9   38.29 5057.49   38.81  5057.6   38.81
 5057.71   38.82  5057.8   38.82 5067.59   39.41  5067.8   39.42  5100.2   41.37
  5109.9   41.95  5111.9   41.96  5175.6   42.44  5175.8   42.44  5238.4   42.02
  5238.6   42.02  5296.8    42.3  5298.6   42.31  5330.6   42.56  5333.7   38.28
  5333.9      38  5343.7   40.16  5343.9    40.2  5357.7    41.5  5449.2    41.5
    5491    41.5    5581    42.1    5626    43.2    5656    42.8  5679.3    43.2
  5749.3    44.9  5838.2   45.49  5899.3    45.9
BR U #Mann= 6
    4477      .2  4685.7     .09  4938.7    .035  5048.9     .09  5449.2     .14
  5838.2      .2
BR U Banks=4938.7,5048.9
BR D #Sta/Elev= 73
    4477    45.6  4509.5   45.02    4627    42.9    4637    42.5    4647    40.8
    4652    39.1    4657    36.3  4659.5    35.1  4661.6    34.1  4676.6    33.9
  4680.3    42.3  4685.7   42.25  4733.5   41.76  4733.8   41.75  4779.4   40.46
    4780   40.44  4838.9   40.12  4841.2   40.11  4871.5   40.95  4895.5   41.62
  4901.8   41.98 4937.49   44.02  4937.6   44.03 4937.71   44.03  4937.8   44.04
 4937.91   44.04    4938   44.05  4938.7   44.09  4942.2   41.77  4959.8   34.21
  4969.1   30.06  4977.7   26.22  4979.1   26.31  4990.6    23.8  4991.8   23.07
  5001.8    22.5    5008   22.89  5009.4   23.38  5013.1   24.01  5017.3   24.09
    5033    32.2  5037.2   34.37  5048.9   38.19 5057.49   38.71  5057.6   38.71
 5057.71   38.72  5057.8   38.72 5067.59   39.31  5067.8   39.32  5100.2   41.27
  5109.9   41.85  5111.9   41.86  5175.6   42.34  5175.8   42.34  5238.4   41.92
  5238.6   41.92  5296.8    42.2  5298.6   42.21  5330.6   42.46  5333.7   38.18
  5333.9    37.9  5343.7   40.06  5343.9    40.1  5357.7    41.4  5449.2    41.4
    5491    41.4    5581      42    5626    43.1    5656    42.7  5679.3    43.1
  5749.3    44.8  5838.2   45.39  5899.3    45.8
BR D #Mann= 6
    4477      .2  4685.7     .09  4938.7    .035  5048.9     .09  5449.2     .14
  5838.2      .2
BR D Banks=4938.7,5048.9
BC Design=,, 0 ,, 0 ,,,,,,
BC HTab HWMax=45.9
BC Use User HTab Curves=0
BC User HTab FreeFlow(D)= 0