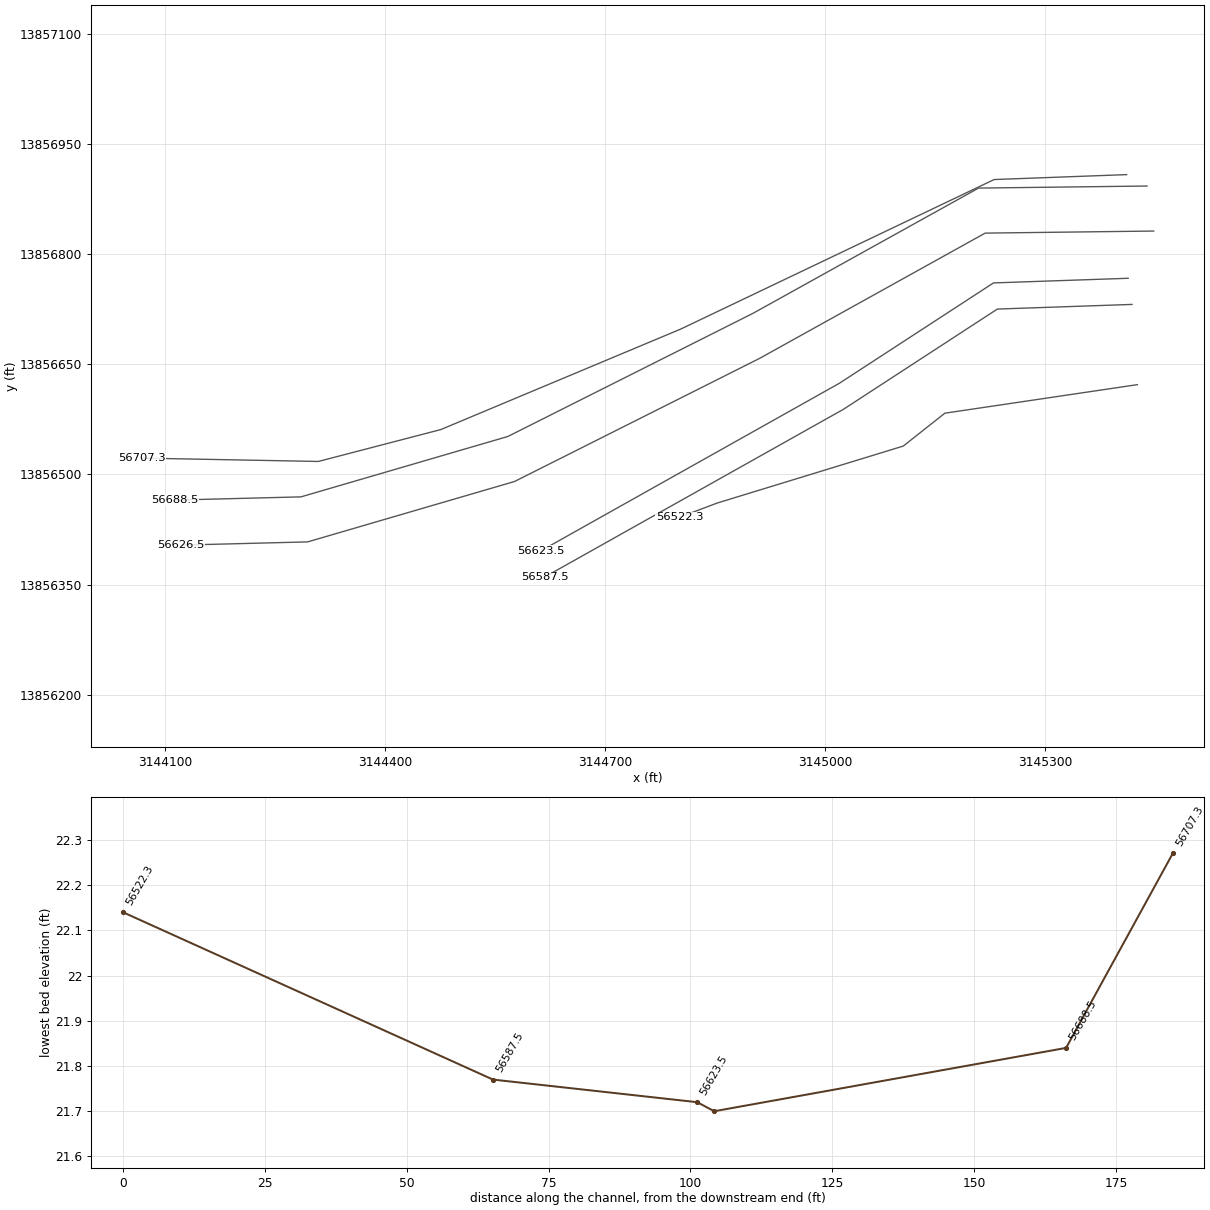
HEC-RAS study H100-00-00.prj: H100-00-00

--- H100-00-00.g01 (geometry) --- (continued)

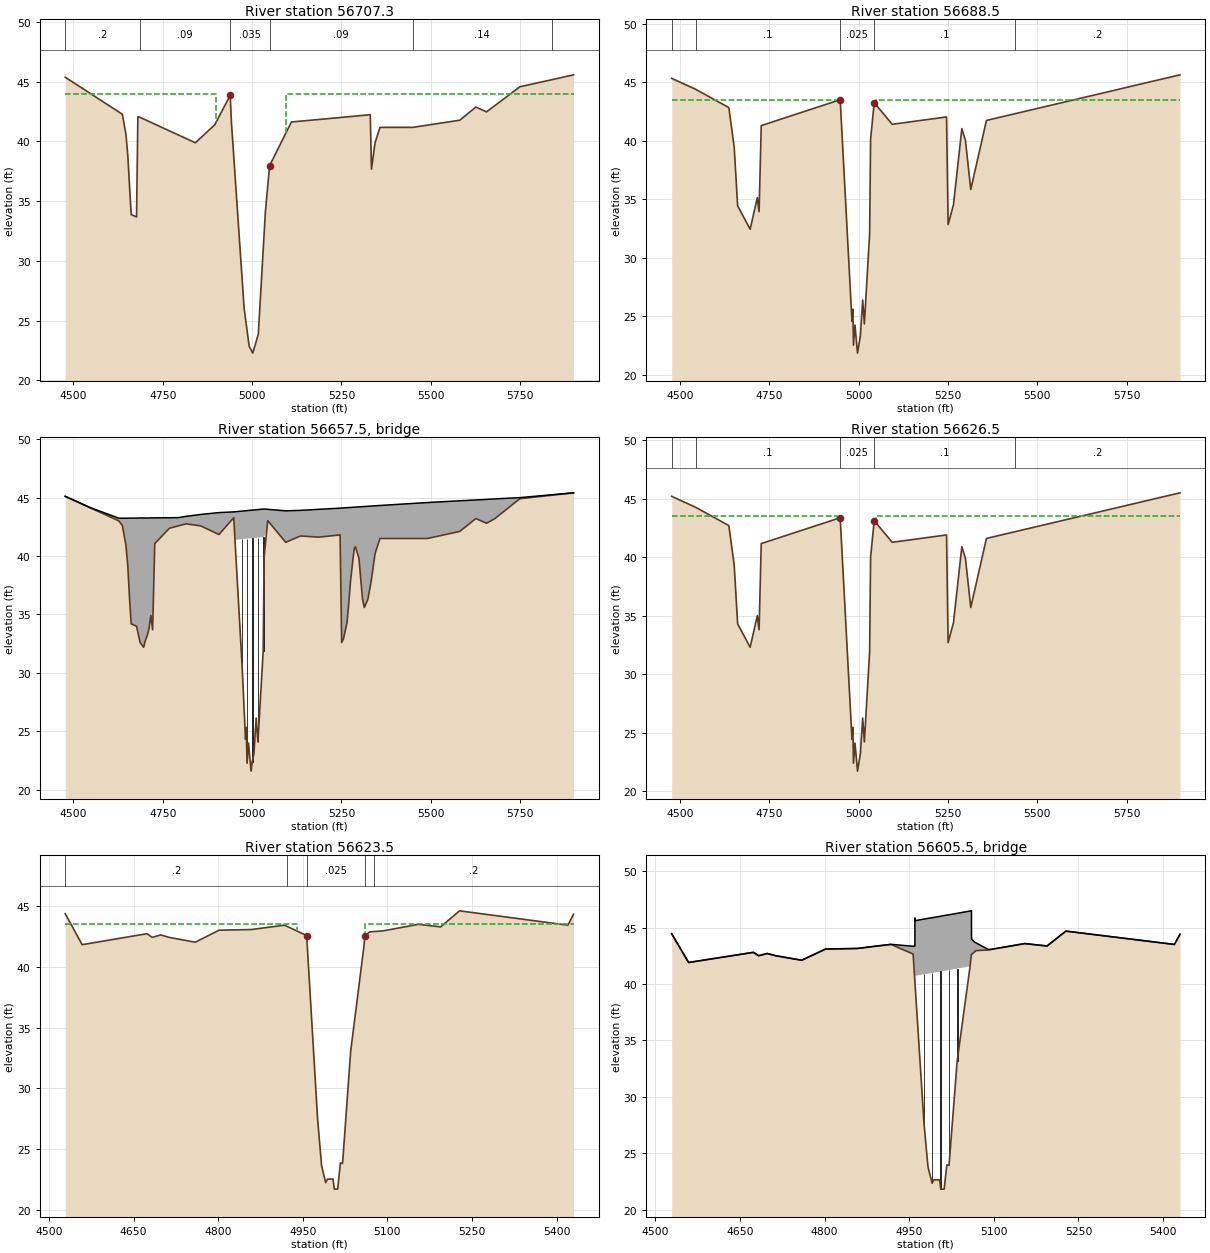
Type RM Length L Ch R = 1 ,56707.3 ,18.8,18.8,18.8
BEGIN DESCRIPTION:
Downstream Section of Bridge/Culvert/Weir
END DESCRIPTION:
XS GIS Cut Line= 6
      3145411.39      13856908.4      3145230.68     13856901.71
      3144803.24     13856698.01      3144475.98      13856561.1
      3144309.01     13856517.68      3144068.53     13856522.24
#Sta/Elev= 30
    4477   45.37    4637   42.27    4647   40.57    4652   38.87  4661.6   33.87
  4676.6   33.67  4680.3   42.07  4685.7   42.02  4841.2   39.88  4895.5   41.39
  4938.7   43.86  4942.2   41.54  4977.7   25.99  4991.8   22.84  5001.8   22.27
  5017.3   23.86  5037.2   34.14  5048.9   37.96  5109.9   41.62  5330.6   42.23
  5333.9   37.67  5343.9   39.87  5357.7   41.17  5449.2   41.17    5581   41.77
    5626   42.87    5656   42.47  5749.3   44.57  5838.2   45.16  5899.3   45.57
#Mann= 6 , 1 , 0
    4477      .2       0  4685.7     .09       0  4938.7    .035       0
  5048.9     .09       0  5449.2     .14       0  5838.2      .2       0
#XS Ineff= 2 , 0
       0    4900      44    5095       0      44
Permanent Ineff=
       F       F
Bank Sta=4938.7,5048.9
XS Rating Curve= 0 ,0
Exp/Cntr=0.5,0.3

Type RM Length L Ch R = 1 ,56688.5 ,62,62,62
BEGIN DESCRIPTION:
Upstream Section of Bridge/Culvert/Weir
END DESCRIPTION:
XS GIS Cut Line= 6
       3145439.2     13856892.86      3145209.43     13856890.07
      3144901.64     13856719.37      3144567.54     13856551.73
      3144285.33     13856469.45      3144112.61     13856465.04
#Sta/Elev= 30
    4477   45.33  4544.4   44.39    4637   42.83    4652   39.43  4661.6   34.43
  4696.6   32.43  4716.6   35.13  4721.6   33.93  4727.6   41.29  4948.5    43.5
  4981.5   24.56  4983.8   25.59  4985.7   22.52  4989.9   24.24    4997   21.84
  5005.1   23.34  5011.4   26.38  5016.2   24.34  5030.9   32.07  5033.6   40.12
  5043.7   43.25  5094.1    41.4  5246.1   42.03  5250.5   32.83  5265.5   34.53
  5288.9   41.03  5298.9   40.03  5313.9   35.83  5357.7   41.73  5899.3   45.63
#Mann= 5 , 1 , 0
    4477      .2       0  4544.4      .1       0  4948.5    .025       0
  5043.7      .1       0    5438      .2       0
#XS Ineff= 2 , 0
       0    4940    43.5    5050       0    43.5
Permanent Ineff=
       F       F
Bank Sta=4948.5,5043.7
XS Rating Curve= 0 ,0
Exp/Cntr=0.5,0.3

Type RM Length L Ch R = 3 ,56657.5 ,,,
BEGIN DESCRIPTION:
UNION PACIFIC RAILROAD
Structure ID: H00-43
END DESCRIPTION:
Bridge Culvert--1,0,-1,-1, 0
Deck Dist Width WeirC Skew NumUp NumDn MinLoCord MaxHiCord MaxSubmerge Is_Ogee
10,42,2.6,0, 52, 52, , , 0.95, 0, 1,1,,
    4477  4544.4    4627    4637    4647    4652    4657  4661.6  4676.6  4686.6
  4696.6  4701.6  4706.6  4711.6  4716.6  4721.6  4727.6  4768.5    4793  4815.6
  4856.5  4907.1  4948.5    4952  5033.6  5041.2  5043.7  5094.1  5135.5  5186.4
  5246.1  5250.5  5255.5  5265.5  5270.5  5275.5  5285.5  5288.9  5298.9  5308.9
  5313.9  5323.9  5333.9  5343.9  5357.7    5491    5581    5626    5656  5679.3
  5749.3  5899.3
    45.1   44.17   43.23   43.23   43.23   43.23   43.24   43.24   43.24   43.25
   43.25   43.25   43.25   43.25   43.26   43.26   43.26   43.27   43.28   43.39
   43.55   43.71   43.77   43.78   44.02      44   43.99   43.86    43.9   43.99
   44.09    44.1   44.11   44.13   44.14   44.15   44.17   44.18    44.2   44.22
   44.23   44.25   44.27   44.29   44.32   44.57   44.72   44.79   44.84   44.88
   44.99    45.4
    45.1   44.16      43    42.6    40.9    39.2    36.4    34.2      34    32.6
    32.2    32.8    33.2    33.8    34.9    33.7   41.06   42.37   42.57   42.75
   42.57   41.83   43.27   41.38   41.62   42.25   43.02   41.17   41.71   41.61
    41.8    32.6    32.9    34.3      36    37.9    40.6    40.8    39.8    36.3
    35.6    36.3      38    40.2    41.5    41.5    42.1    43.2    42.8    43.2
    44.9    45.4
    4477  4544.4    4627    4637    4647    4652    4657  4661.6  4676.6  4686.6
  4696.6  4701.6  4706.6  4711.6  4716.6  4721.6  4727.6  4768.5    4793  4815.6
  4856.5  4907.1  4948.5    4952  5033.6  5041.2  5043.7  5094.1  5135.5  5186.4
  5246.1  5250.5  5255.5  5265.5  5270.5  5275.5  5285.5  5288.9  5298.9  5308.9
  5313.9  5323.9  5333.9  5343.9  5357.7    5491    5581    5626    5656  5679.3
  5749.3  5899.3
    45.1   44.17   43.23   43.23   43.23   43.23   43.24   43.24   43.24   43.25
   43.25   43.25   43.25   43.25   43.26   43.26   43.26   43.27   43.28   43.39
   43.55   43.71   43.77   43.78   44.02      44   43.99   43.86    43.9   43.99
   44.09    44.1   44.11   44.13   44.14   44.15   44.17   44.18    44.2   44.22
   44.23   44.25   44.27   44.29   44.32   44.57   44.72   44.79   44.84   44.88
   44.99    45.4
    45.1   44.16      43    42.6    40.9    39.2    36.4    34.2      34    32.6
    32.2    32.8    33.2    33.8    34.9    33.7   41.06   42.37   42.57   42.75
   42.57   41.83   43.27   41.38   41.62   42.25   43.02   41.17   41.71   41.61
    41.8    32.6    32.9    34.3      36    37.9    40.6    40.8    39.8    36.3
    35.6    36.3      38    40.2    41.5    41.5    42.1    43.2    42.8    43.2
    44.9    45.4
Pier Skew, UpSta & Num, DnSta & Num=  ,4971.7, 2 ,4971.7, 2 , 0 , 0 , 0 ,,
       2       2
   29.09   42.44
       2       2
   29.09   42.44
Pier Skew, UpSta & Num, DnSta & Num=  ,4985.7, 2 ,4985.7, 2 , 0 , 0 , 0 ,,
       2       2
    21.7   42.49
       2       2
    21.7   42.49
Pier Skew, UpSta & Num, DnSta & Num=  ,5000.2, 2 ,5000.2, 2 , 0 , 0 , 0 ,,
       2       2
   21.15   42.53
       2       2
   21.15   42.53
Pier Skew, UpSta & Num, DnSta & Num=  ,5016.2, 2 ,5016.2, 2 , 0 , 0 , 0 ,,
       2       2
   23.54   42.58
       2       2
   23.54   42.58
Pier Skew, UpSta & Num, DnSta & Num=  ,5030.9, 2 ,5030.9, 2 , 0 , 0 , 0 ,,
       2       2
   30.31   42.63
       2       2
   30.31   42.63
BR Coef= 1 , 1 , 0 ,1.25, 0 ,,,0.8,-1,2,0,
WSPro=,,,, 1 ,,,, 0 ,,,, 0 ,,,,-1 ,-1 ,-1 , 0 , 0 , 0 , 0 , 0
BR U #Sta/Elev= 78
    4477    45.1  4544.4   44.16    4627      43    4637    42.6    4647    40.9
    4652    39.2    4657    36.4  4661.6    34.2  4676.6      34  4686.6    32.6
  4696.6    32.2  4701.6    32.8  4706.6    33.2  4711.6    33.8  4716.6    34.9
  4721.6    33.7  4727.6   41.06  4768.5   42.37    4793   42.57  4815.6   42.75
  4836.3   42.66  4856.5   42.57    4904   41.88  4907.1   41.83  4948.5   43.27
 4951.21   41.81  4951.3   41.76  4951.4   41.71    4952   41.38  4971.7   30.75
  4981.5   24.33  4983.8   25.36  4985.7   22.29  4989.9   24.01    4997   21.61
  5000.2    22.4  5005.1   23.11  5011.4   26.15  5016.2   24.11  5030.5   31.63
  5030.9   31.84  5033.6   39.89  5041.2   42.25 5041.29   42.27  5041.4   42.31
  5043.7   43.02    5086   41.47  5094.1   41.17  5135.5   41.71  5137.5   41.71
  5186.4   41.61  5189.7   41.62  5245.2    41.8  5246.1    41.8  5250.5    32.6
  5255.5    32.9  5265.5    34.3  5270.5      36  5275.5    37.9  5285.5    40.6
  5288.9    40.8  5298.9    39.8  5308.9    36.3  5313.9    35.6  5323.9    36.3
  5333.9      38  5343.6   40.13  5343.9    40.2  5357.7    41.5  5443.6    41.5
    5491    41.5    5581    42.1    5626    43.2    5656    42.8  5679.3    43.2
  5749.3    44.9  5753.6   44.91  5899.3    45.4
BR U #Mann= 5
    4477      .2  4544.4      .1  4948.5    .025  5043.7      .1    5438      .2
BR U Banks=4948.5,5043.7
BR D #Sta/Elev= 78
    4477    45.1  4544.4   44.16    4627      43    4637    42.6    4647    40.9
    4652    39.2    4657    36.4  4661.6    34.2  4676.6      34  4686.6    32.6
  4696.6    32.2  4701.6    32.8  4706.6    33.2  4711.6    33.8  4716.6    34.9
  4721.6    33.7  4727.6   41.06  4768.5   42.37    4793   42.57  4815.6   42.75
  4836.3   42.66  4856.5   42.57    4904   41.88  4907.1   41.83  4948.5   43.27
 4951.21   41.81  4951.3   41.76  4951.4   41.71    4952   41.38  4971.7   30.75
  4981.5   24.33  4983.8   25.36  4985.7   22.29  4989.9   24.01    4997   21.61
  5000.2    22.4  5005.1   23.11  5011.4   26.15  5016.2   24.11  5030.5   31.63
  5030.9   31.84  5033.6   39.89  5041.2   42.25 5041.29   42.27  5041.4   42.31
  5043.7   43.02    5086   41.47  5094.1   41.17  5135.5   41.71  5137.5   41.71
  5186.4   41.61  5189.7   41.62  5245.2    41.8  5246.1    41.8  5250.5    32.6
  5255.5    32.9  5265.5    34.3  5270.5      36  5275.5    37.9  5285.5    40.6
  5288.9    40.8  5298.9    39.8  5308.9    36.3  5313.9    35.6  5323.9    36.3
  5333.9      38  5343.6   40.13  5343.9    40.2  5357.7    41.5  5443.6    41.5
    5491    41.5    5581    42.1    5626    43.2    5656    42.8  5679.3    43.2
  5749.3    44.9  5753.6   44.91  5899.3    45.4
BR D #Mann= 5
    4477      .2  4544.4      .1  4948.5    .025  5043.7      .1    5438      .2
BR D Banks=4948.5,5043.7
BC Design=,, 0 ,, 0 ,,,,,,
BC HTab HWMax=45.63
BC Use User HTab Curves=0
BC User HTab FreeFlow(D)= 0

Type RM Length L Ch R = 1 ,56626.5 ,3,3,3
BEGIN DESCRIPTION:
Downstream Section of Bridge/Culvert/Weir
END DESCRIPTION:
XS GIS Cut Line= 6
      3145448.27     13856831.53      3145218.49     13856828.73
       3144910.7     13856658.03       3144576.6     13856490.39
      3144294.39     13856408.11      3144121.68     13856403.71
#Sta/Elev= 30
    4477   45.19  4544.4   44.25    4637   42.69    4652   39.29  4661.6   34.29
  4696.6   32.29  4716.6   34.99  4721.6   33.79  4727.6   41.15  4948.5   43.36
  4981.5   24.42  4983.8   25.45  4985.7   22.38  4989.9    24.1    4997    21.7
  5005.1    23.2  5011.4   26.24  5016.2    24.2  5030.9   31.93  5033.6   39.98
  5043.7   43.11  5094.1   41.26  5246.1   41.89  5250.5   32.69  5265.5   34.39
  5288.9   40.89  5298.9   39.89  5313.9   35.69  5357.7   41.59  5899.3   45.49
#Mann= 5 , 1 , 0
    4477      .2       0  4544.4      .1       0  4948.5    .025       0
  5043.7      .1       0    5438      .2       0
#XS Ineff= 2 , 0
       0    4940    43.5    5050       0    43.5
Permanent Ineff=
       F       F
Bank Sta=4948.5,5043.7
XS Rating Curve= 0 ,0
Exp/Cntr=0.5,0.3

Type RM Length L Ch R = 1 ,56623.5 ,36,36,36
BEGIN DESCRIPTION:
Upstream Section of Bridge/Culvert/Weir
END DESCRIPTION:
XS GIS Cut Line= 4
      3145413.46      13856767.2      3145229.78     13856760.87
      3145019.86     13856624.33      3144612.27     13856395.78
#Sta/Elev= 30
  4528.7   44.36  4558.7   41.81  4673.7   42.71    4683   42.41    4698   42.61
    4713   42.41  4759.3   42.01  4801.6      43  4858.3   43.05  4917.7   43.41
  4956.9   42.56  4976.3   27.49  4983.3   23.68  4990.6   22.25  4993.8   22.54
  5003.6   22.55    5006   21.72  5011.9   21.72  5016.7   23.87  5020.6   23.83
    5035   33.06  5057.9   41.46  5060.1   42.49  5068.3   42.86  5092.1   42.94
  5155.1   43.48  5194.5   43.27    5228   44.59  5420.2   43.41  5430.2   44.31
#Mann= 5 , 1 , 0
  4528.7      .2       0  4922.8      .1       0  4956.9    .025       0
  5060.1      .1       0  5076.2      .2       0
#XS Ineff= 2 , 0
       0    4940    43.5    5060       0    43.5
Permanent Ineff=
       F       F
Bank Sta=4956.9,5060.1
XS Rating Curve= 0 ,0
Exp/Cntr=0.5,0.3

Type RM Length L Ch R = 3 ,56605.5 ,,,
BEGIN DESCRIPTION:
ACCESS ROAD
Structure ID: H00-42
END DESCRIPTION:
Bridge Culvert--1,0,-1,-1, 0
Deck Dist Width WeirC Skew NumUp NumDn MinLoCord MaxHiCord MaxSubmerge Is_Ogee
10,16,2.6,0, 51, 51, , , 0.95, 0, 1,1,,
  4528.7  4558.7  4673.7    4683    4698    4713  4759.3  4801.6  4804.2  4850.4
  4858.3  4890.8  4917.7  4956.9 4959.97 4960.08 4960.19 4960.31  4960.4  4960.5
  4960.8  4976.3  4983.3  4990.6  4993.8  5003.6    5006  5011.9  5016.7  5020.6
    5035  5057.9  5060.1  5060.2 5060.26 5060.37 5060.48 5060.59  5060.7    5066
  5068.3  5089.3  5092.1  5152.6  5155.1  5191.8  5194.5  5227.2    5228  5420.2
  5430.2
   44.45    41.9    42.8    42.5    42.7    42.5    42.1   43.09    43.1   43.14
   43.15   43.35   43.51   43.34   43.35   45.85   45.85    45.8   45.77   45.73
   45.61   45.75   45.81   45.87    45.9   45.98   46.01   46.06    46.1   46.13
   46.26   46.46   46.48   46.48   46.48   46.48   43.98   43.97   43.97    43.7
   43.64   43.08   43.04   43.56   43.58   43.38   43.37   44.66   44.68    43.5
    44.4
   44.45    41.9    42.8    42.5    42.7    42.5    42.1   43.09   43.09   43.13
   43.14   43.34    43.5   42.65   40.27   40.18   40.09      40   40.87   40.83
   40.71   40.85   40.91   40.97      41   41.08   41.11   41.16    41.2   41.23
   41.36   41.56   42.58   42.58   42.59   42.59    42.6    42.6   42.61   42.85
   42.95   43.01   43.03   43.55   43.57   43.37   43.36   44.65   44.68    43.5
    44.4
  4528.7  4558.7  4673.7    4683    4698    4713  4759.3  4801.6  4804.2  4850.4
  4858.3  4890.8  4917.7  4956.9 4959.97 4960.08 4960.19 4960.31  4960.4  4960.5
  4960.8  4976.3  4983.3  4990.6  4993.8  5003.6    5006  5011.9  5016.7  5020.6
    5035  5057.9  5060.1  5060.2 5060.26 5060.37 5060.48 5060.59  5060.7    5066
  5068.3  5089.3  5092.1  5152.6  5155.1  5191.8  5194.5  5227.2    5228  5420.2
  5430.2
   44.45    41.9    42.8    42.5    42.7    42.5    42.1   43.09    43.1   43.14
   43.15   43.35   43.51   43.34   43.35   45.85   45.85    45.8   45.77   45.73
   45.61   45.75   45.81   45.87    45.9   45.98   46.01   46.06    46.1   46.13
   46.26   46.46   46.48   46.48   46.48   46.48   43.98   43.97   43.97    43.7
   43.64   43.08   43.04   43.56   43.58   43.38   43.37   44.66   44.68    43.5
    44.4
   44.35    41.8    42.7    42.4    42.6    42.4      42   42.99   42.99   43.03
   43.04   43.24    43.4   42.55   40.17   40.08   39.99    39.9   40.77   40.73
   40.61   40.75   40.81   40.87    40.9   40.98   41.01   41.06    41.1   41.13
   41.26   41.46   42.48   42.48   42.49   42.49    42.5    42.5   42.51   42.75
   42.85   42.91   42.93   43.45   43.47   43.27   43.26   44.55   44.58    43.4
    44.3
Pier Skew, UpSta & Num, DnSta & Num=  ,4976.3, 2 ,4976.3, 2 , 0 , 0 , 0 ,,
     1.3     1.3
   26.23   41.86
     1.3     1.3
   26.13   41.76
Pier Skew, UpSta & Num, DnSta & Num=  ,4990.6, 2 ,4990.6, 2 , 0 , 0 , 0 ,,
     1.3     1.3
    21.4   41.98
     1.3     1.3
    21.3   41.88
Pier Skew, UpSta & Num, DnSta & Num=  ,5006, 2 ,5006, 2 , 0 , 0 , 0 ,,
     1.3     1.3
   20.81   42.12
     1.3     1.3
   20.71   42.02
Pier Skew, UpSta & Num, DnSta & Num=  ,5020.6, 2 ,5020.6, 2 , 0 , 0 , 0 ,,
     1.3     1.3
   22.93   42.24
     1.3     1.3
   22.83   42.14
Pier Skew, UpSta & Num, DnSta & Num=  ,5035, 2 ,5035, 2 , 0 , 0 , 0 ,,
     1.3     1.3
   31.73   42.37
     1.3     1.3
   31.63   42.27
BR Coef= 1 , 1 , 0 ,1.25, 0 ,,,0.8,-1,2,0,
WSPro=,,,, 1 ,,,, 0 ,,,, 0 ,,,,-1 ,-1 ,-1 , 0 , 0 , 0 , 0 , 0
BR U #Sta/Elev= 51
  4528.7   44.45  4558.7    41.9  4673.7    42.8    4683    42.5    4698    42.7
    4713    42.5  4759.3    42.1  4801.6   43.09  4804.2   43.09  4850.4   43.13
  4858.3   43.14  4890.8   43.34  4917.7    43.5  4956.9   42.65 4959.97   40.27
 4960.08   40.18 4960.19   40.09 4960.31      40  4960.4   39.93  4960.5   39.85
  4960.8   39.62  4976.3   27.58  4983.3   23.77  4990.6   22.34  4993.8   22.63
  5003.6   22.64    5006   21.81  5011.9   21.81  5016.7   23.96  5020.6   23.92
    5035   33.15  5057.9   41.55  5060.1   42.58  5060.2   42.58 5060.26   42.59
 5060.37   42.59 5060.48    42.6 5060.59    42.6  5060.7   42.61    5066   42.85
  5068.3   42.95  5089.3   43.01  5092.1   43.03  5152.6   43.55  5155.1   43.57
  5191.8   43.37  5194.5   43.36  5227.2   44.65    5228   44.68  5420.2    43.5
  5430.2    44.4
BR U #Mann= 5
  4528.7      .2  4922.8      .1  4956.9    .025  5060.1      .1  5076.2      .2
BR U Banks=4956.9,5060.1
BR D #Sta/Elev= 51
  4528.7   44.35  4558.7    41.8  4673.7    42.7    4683    42.4    4698    42.6
    4713    42.4  4759.3      42  4801.6   42.99  4804.2   42.99  4850.4   43.03
  4858.3   43.04  4890.8   43.24  4917.7    43.4  4956.9   42.55 4959.97   40.17
 4960.08   40.08 4960.19   39.99 4960.31    39.9  4960.4   39.83  4960.5   39.75
  4960.8   39.52  4976.3   27.48  4983.3   23.67  4990.6   22.24  4993.8   22.53
  5003.6   22.54    5006   21.71  5011.9   21.71  5016.7   23.86  5020.6   23.82
    5035   33.05  5057.9   41.45  5060.1   42.48  5060.2   42.48 5060.26   42.49
 5060.37   42.49 5060.48    42.5 5060.59    42.5  5060.7   42.51    5066   42.75
  5068.3   42.85  5089.3   42.91  5092.1   42.93  5152.6   43.45  5155.1   43.47
  5191.8   43.27  5194.5   43.26  5227.2   44.55    5228   44.58  5420.2    43.4
  5430.2    44.3
BR D #Mann= 5
  4528.7      .2  4922.8      .1  4956.9    .025  5060.1      .1  5076.2      .2
BR D Banks=4956.9,5060.1
BC Design=,, 0 ,, 0 ,,,,,,
BC HTab HWMax=44.59
BC Use User HTab Curves=0
BC User HTab FreeFlow(D)= 0

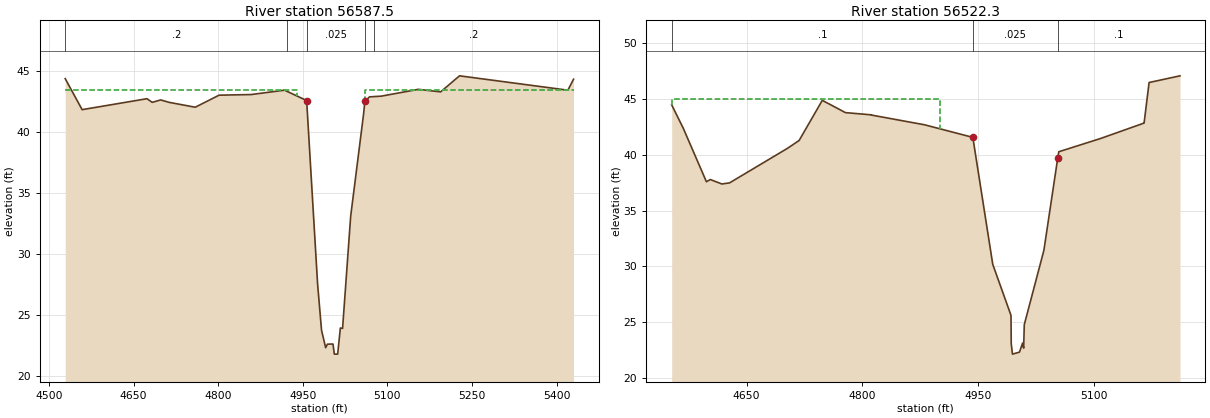
Type RM Length L Ch R = 1 ,56587.5 ,65.2,65.2,65.2
BEGIN DESCRIPTION:
Downstream Section of Bridge/Culvert/Weir
END DESCRIPTION:
XS GIS Cut Line= 4
      3145418.76     13856731.59      3145235.08     13856725.27
      3145025.16     13856588.73      3144617.57     13856360.17
#Sta/Elev= 30
  4528.7   44.41  4558.7   41.86  4673.7   42.76    4683   42.46    4698   42.66
    4713   42.46  4759.3   42.06  4801.6   43.05  4858.3    43.1  4917.7   43.46
  4956.9   42.61  4976.3   27.54  4983.3   23.73  4990.6    22.3  4993.8   22.59
  5003.6    22.6    5006   21.77  5011.9   21.77  5016.7   23.92  5020.6   23.88
    5035   33.11  5057.9   41.51  5060.1   42.54  5068.3   42.91  5089.3   42.97
  5155.1   43.53  5194.5   43.32    5228   44.64  5420.2   43.46  5430.2   44.36
#Mann= 5 , 1 , 0
  4528.7      .2       0  4922.8      .1       0  4956.9    .025       0
  5060.1      .1       0  5076.2      .2       0
#XS Ineff= 2 , 0
       0    4940    43.5    5060       0    43.5
Permanent Ineff=
       F       F
Bank Sta=4956.9,5060.1
XS Rating Curve= 0 ,0
Exp/Cntr=0.5,0.3

Type RM Length L Ch R = 1 ,56522.3 ,129.4,130.7,106.9
BEGIN DESCRIPTION:
Cross Section 56522.3
END DESCRIPTION:
XS GIS Cut Line= 5
      3145426.03     13856622.31      3145163.49     13856583.44
      3145106.75     13856538.65      3144852.92     13856461.01
      3144801.48     13856441.61
#Sta/Elev= 30
  4553.1    44.5  4568.1    42.4  4598.1    37.6  4603.1    37.8  4618.1    37.4
  4628.1    37.5  4703.1    40.6  4718.1    41.3  4748.1    44.9  4778.1    43.8
  4811.7    43.6  4811.8   43.58  4880.4   42.71    4943   41.58  4968.8   30.19
  4992.4   25.62  4992.7   23.09  4994.3   22.14  5003.4   22.32  5007.4   23.13
  5008.8   22.68  5009.6   24.78    5035   31.45  5052.9   39.72  5054.3   40.29
  5108.4   41.48  5164.6   42.86  5164.7   42.86  5171.2    46.5  5211.2    47.1
#Mann= 3 , 1 , 0
  4553.1      .1       0    4943    .025       0  5052.9      .1       0
#XS Ineff= 2 , 0
       0    4900      45               0
Permanent Ineff=
       F       F
Bank Sta=4943,5052.9
XS Rating Curve= 0 ,0
Exp/Cntr=0.5,0.3