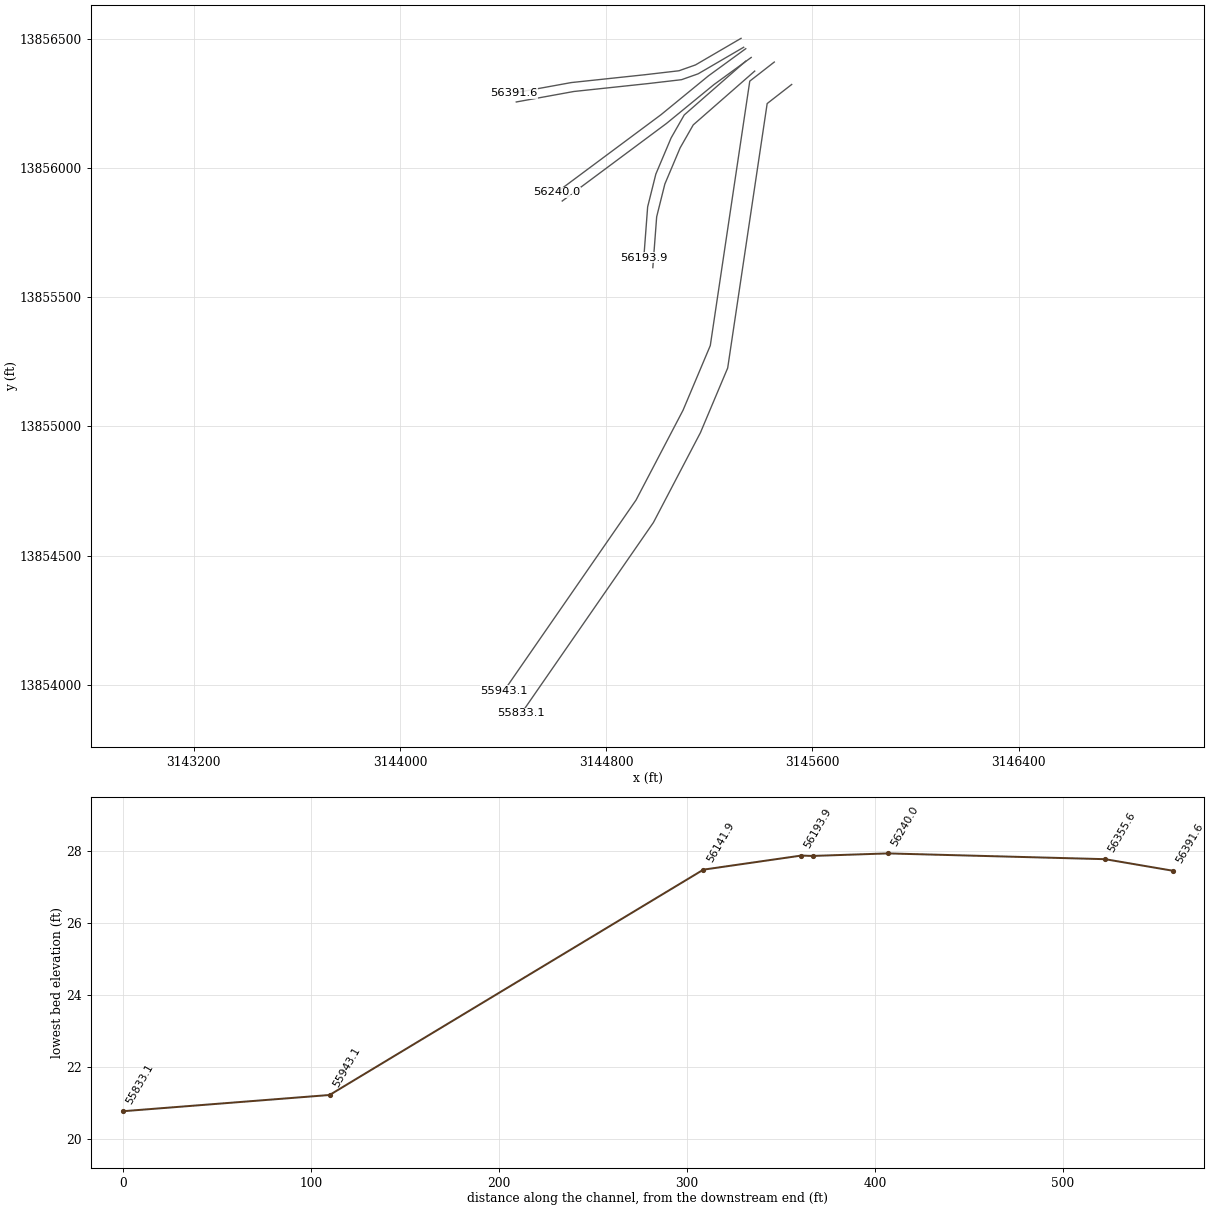
HEC-RAS study H100-00-00.prj: H100-00-00

--- H100-00-00.g01 (geometry) --- (continued)

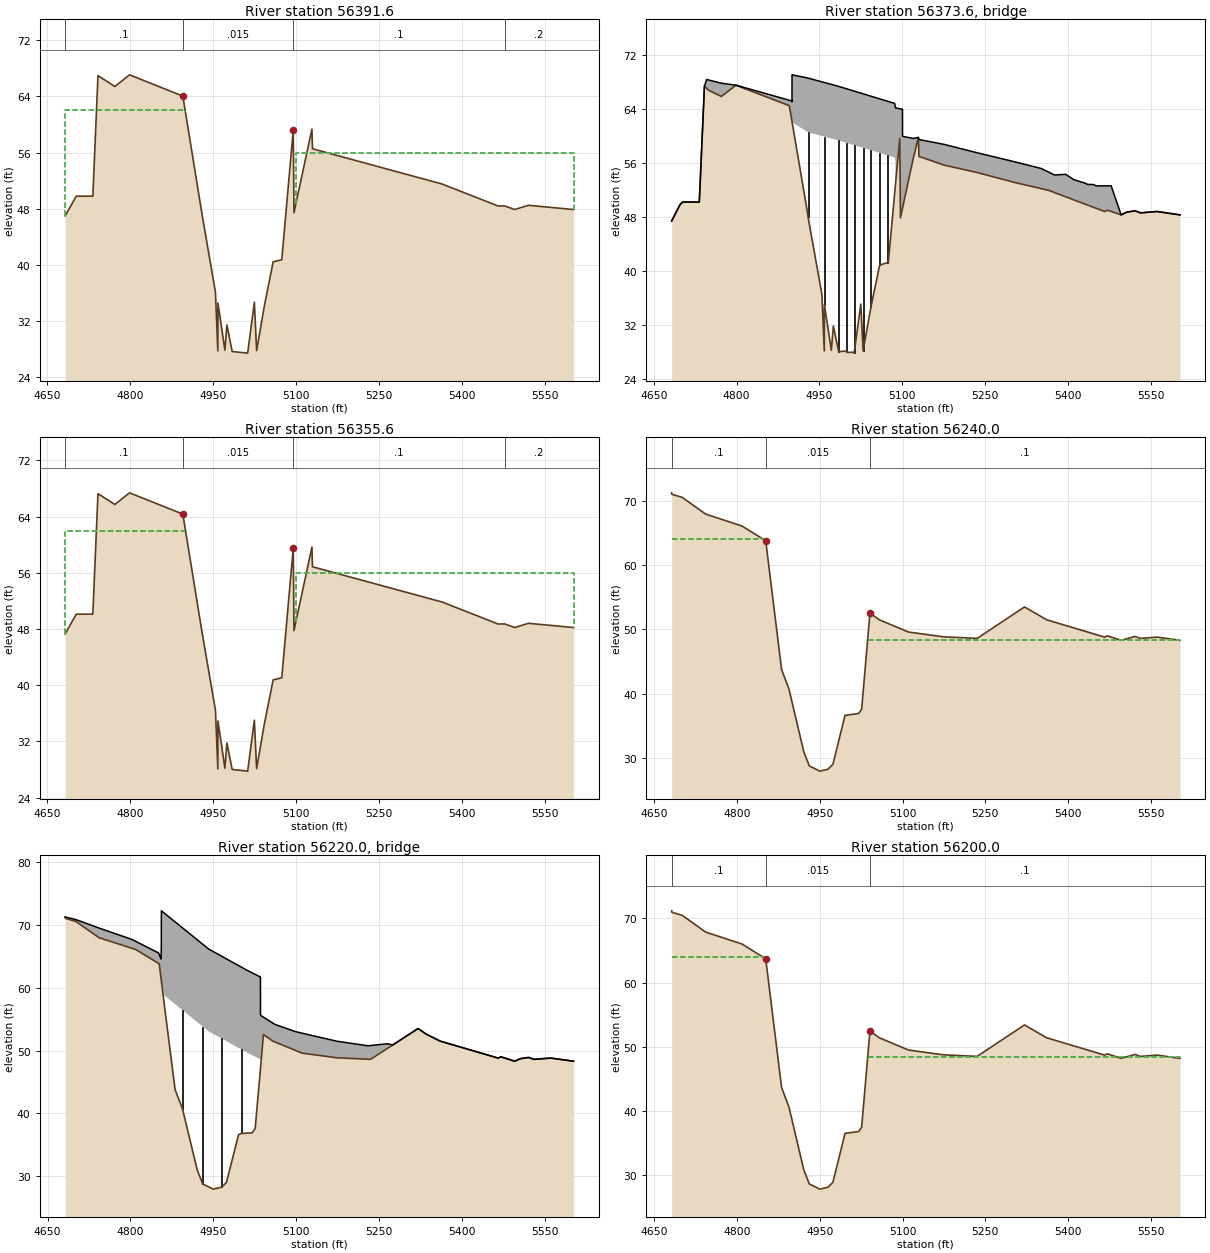
Type RM Length L Ch R = 1 ,56391.6 ,36,36,36
BEGIN DESCRIPTION:
Upstream Section of Bridge/Culvert/Weir
END DESCRIPTION:
XS GIS Cut Line= 6
        3145323.     13856503.77      3145146.37     13856400.82
      3145082.01      13856378.1      3144950.88     13856362.85
      3144664.23     13856332.36      3144440.97     13856291.76
#Sta/Elev= 30
  4682.5   46.99  4702.5   49.79  4732.5   49.79  4741.8   66.95  4772.4   65.41
  4798.9   67.07  4895.4   64.04  4929.5   47.51  4954.4   36.11  4958.7   27.77
  4958.9   34.59  4971.5   27.86  4975.1   31.45  4984.7   27.67  5012.7   27.44
  5024.8   34.69  5028.9    27.8  5043.1   34.25  5058.8   40.43  5074.4   40.74
  5095.2   59.19  5096.5   47.45    5129   59.34    5130   56.54  5364.6   51.52
  5465.9   48.39  5477.8    48.4  5495.9   47.89  5520.9   48.49  5602.4   47.89
#Mann= 4 , 1 , 0
  4682.5      .1       0  4895.4    .015       0  5095.2      .1       0
  5477.8      .2       0
#XS Ineff= 2 , 0
       0    4900      62    5100       0      56
Permanent Ineff=
       F       F
Bank Sta=4895.4,5095.2
XS Rating Curve= 0 ,0
Exp/Cntr=0.5,0.3

Type RM Length L Ch R = 3 ,56373.6 ,,,
BEGIN DESCRIPTION:
RAILROAD
Structure ID: H00-41
END DESCRIPTION:
Bridge Culvert--1,0,-1,-1, 0
Deck Dist Width WeirC Skew NumUp NumDn MinLoCord MaxHiCord MaxSubmerge Is_Ogee
10,16,2.6,0, 48, 48, , , 0.95, 0, 1,1,,
  4682.5  4697.5  4702.5  4732.5  4741.8  4745.8  4749.1  4772.4  4798.9  4895.4
  4899.8  4899.9  4900.2  4900.3 4900.51  4928.6  4984.7  5086.1 5087.49  5087.6
  5095.2  5096.5  5100.2 5100.31  5119.7    5129    5130  5175.6  5234.3  5303.3
  5351.1  5364.6  5375.5  5395.5  5410.5  5430.5  5435.5  5445.5  5450.5  5465.9
  5470.9  5477.8  5495.9  5505.9  5520.9    5531    5561  5602.4
    47.4    49.8    50.2    50.2   67.36   68.33   68.26   67.78   67.49   65.26
   65.17   65.02   65.02   69.02   69.02   68.55   67.31   64.79   64.17   64.12
      64   63.98   63.92   59.92   59.61   59.76   59.45   58.73   57.51   56.15
   55.17   54.63    54.2    54.3    53.5      53    52.8    52.8    52.6    52.6
    52.6    52.6    48.3    48.7    48.9    48.6    48.8    48.3
    47.4    49.8    50.2    50.2   67.36   67.02   66.74   65.82   67.48   64.45
   62.33   62.28   62.14   62.09   61.99   60.55   59.31   56.79   56.17   52.86
    59.6   47.86   49.26   49.31   56.66   59.75   56.95   55.66   54.59   53.09
   52.19   51.93   51.59   50.98   50.51   49.89   49.74   49.43   49.28    48.8
      49   48.81    48.3    48.7    48.9    48.6    48.8    48.3
  4682.5  4697.5  4702.5  4732.5  4741.8  4745.8  4749.1  4772.4  4798.9  4895.4
  4899.8  4899.9  4900.2  4900.3 4900.51  4928.6  4984.7  5086.1 5087.49  5087.6
  5095.2  5096.5  5100.2 5100.31  5119.7    5129    5130  5175.6  5234.3  5303.3
  5351.1  5364.6  5375.5  5395.5  5410.5  5430.5  5435.5  5445.5  5450.5  5465.9
  5470.9  5477.8  5495.9  5505.9  5520.9    5531    5561  5602.4
    47.4    49.8    50.2    50.2   67.36   68.33   68.26   67.78   67.49   65.26
   65.17   65.02   65.02   69.02   69.02   68.55   67.31   64.79   64.17   64.12
      64   63.98   63.92   59.92   59.61   59.76   59.45   58.73   57.51   56.15
   55.17   54.63    54.2    54.3    53.5      53    52.8    52.8    52.6    52.6
    52.6    52.6    48.3    48.7    48.9    48.6    48.8    48.3
    47.3    49.7    50.1    50.1   67.26   66.92   66.64   65.72   67.38   64.35
   62.23   62.18   62.04   61.99   61.89   60.45   59.21   56.69   56.07   52.76
    59.5   47.76   49.16   49.21   56.56   59.65   56.85   55.56   54.49   52.99
   52.09   51.83   51.49   50.88   50.41   49.79   49.64   49.33   49.18    48.7
    48.9   48.71    48.2    48.6    48.8    48.5    48.7    48.2
Pier Skew, UpSta & Num, DnSta & Num=  ,4929.5, 2 ,4929.5, 2 , 0 , 0 , 0 ,,
       2       2
   46.46   61.56
       2       2
   46.36   61.46
Pier Skew, UpSta & Num, DnSta & Num=  ,4958.9, 2 ,4958.9, 2 , 0 , 0 , 0 ,,
       2       2
   28.73   60.92
       2       2
   28.63   60.82
Pier Skew, UpSta & Num, DnSta & Num=  ,4984.7, 2 ,4984.7, 2 , 0 , 0 , 0 ,,
       2       2
   27.08   60.33
       2       2
   26.98   60.23
Pier Skew, UpSta & Num, DnSta & Num=  ,4999.6, 2 ,4999.6, 2 , 0 , 0 , 0 ,,
       2       2
   26.95   59.96
       2       2
   26.85   59.86
Pier Skew, UpSta & Num, DnSta & Num=  ,5012.7, 2 ,5012.7, 2 , 0 , 0 , 0 ,,
       2       2
    26.9   59.64
       2       2
    26.8   59.54
Pier Skew, UpSta & Num, DnSta & Num=  ,5028.9, 2 ,5028.9, 2 , 0 , 0 , 0 ,,
       2       2
   27.66   59.22
       2       2
   27.56   59.12
Pier Skew, UpSta & Num, DnSta & Num=  ,5043.1, 2 ,5043.1, 2 , 0 , 0 , 0 ,,
       2       2
   33.21   58.87
       2       2
   33.11   58.77
Pier Skew, UpSta & Num, DnSta & Num=  ,5058.8, 2 ,5058.8, 2 , 0 , 0 , 0 ,,
       2       2
   39.45   58.48
       2       2
   39.35   58.38
Pier Skew, UpSta & Num, DnSta & Num=  ,5073.5, 2 ,5073.5, 2 , 0 , 0 , 0 ,,
       2       2
   40.22   58.13
       2       2
   40.12   58.02
Abutment Skew #Up #Dn= , 2 , 2
  5074.4 5087.69
   41.15   56.17
  5074.4 5087.69
   41.05   56.07
BR Coef= 1 , 1 , 0 ,1.25, 0 ,,,0.8,0,2,0,
WSPro=,,,, 1 ,,,, 0 ,,,, 0 ,,,,-1 ,-1 ,-1 , 0 , 0 , 0 , 0 , 0
BR U #Sta/Elev= 78
  4682.5    47.4  4697.5    49.8  4702.5    50.2  4732.5    50.2  4741.8   67.36
  4745.8   67.02  4749.1   66.74  4772.4   65.82  4798.9   67.48  4895.4   64.45
  4899.8   62.33  4899.9   62.28 4900.01   62.23 4900.09   62.19  4900.2   62.14
  4900.3   62.09  4900.4   62.04 4900.51   61.99  4928.6   48.47  4929.5   47.92
  4936.7   44.62  4954.4   36.52  4958.7   28.18  4958.9      35  4971.5   28.27
  4975.1   31.86  4984.7   28.08  4987.6   28.09  4999.1   28.15  4999.6   27.95
  5010.3   27.98  5012.7   27.85  5024.8    35.1  5028.1   29.55  5028.9   28.21
  5043.1   34.66  5058.8   40.84  5059.1   40.87  5073.5   41.25  5074.3   41.16
  5074.4   41.15  5086.1   51.53 5087.49   52.76  5087.6   52.86  5087.8   53.04
  5095.2    59.6  5096.5   47.86 5100.09   49.22  5100.2   49.26 5100.31   49.31
  5119.7   56.66    5129   59.75    5130   56.95  5175.6   55.66  5177.3   55.63
  5229.2   54.68  5234.3   54.59    5303    53.1  5303.3   53.09  5351.1   52.19
  5364.6   51.93  5375.5   51.59  5395.5   50.98  5410.5   50.51  5430.5   49.89
  5435.5   49.74  5445.5   49.43  5450.5   49.28  5465.9    48.8  5470.9      49
  5475.5   48.87  5477.8   48.81  5495.9    48.3  5505.9    48.7  5520.9    48.9
    5531    48.6    5561    48.8  5602.4    48.3
BR U #Mann= 4
  4682.5      .1  4895.4    .015  5095.2      .1  5477.8      .2
BR U Banks=4895.4,5095.2
BR D #Sta/Elev= 78
  4682.5    47.3  4697.5    49.7  4702.5    50.1  4732.5    50.1  4741.8   67.26
  4745.8   66.92  4749.1   66.64  4772.4   65.72  4798.9   67.38  4895.4   64.35
  4899.8   62.23  4899.9   62.18 4900.01   62.13 4900.09   62.09  4900.2   62.04
  4900.3   61.99  4900.4   61.94 4900.51   61.89  4928.6   48.37  4929.5   47.82
  4936.7   44.52  4954.4   36.42  4958.7   28.08  4958.9    34.9  4971.5   28.17
  4975.1   31.76  4984.7   27.98  4987.6   27.99  4999.1   28.05  4999.6   27.85
  5010.3   27.88  5012.7   27.75  5024.8      35  5028.1   29.45  5028.9   28.11
  5043.1   34.56  5058.8   40.74  5059.1   40.77  5073.5   41.15  5074.3   41.06
  5074.4   41.05  5086.1   51.43 5087.49   52.66  5087.6   52.76  5087.8   52.94
  5095.2    59.5  5096.5   47.76 5100.09   49.12  5100.2   49.16 5100.31   49.21
  5119.7   56.56    5129   59.65    5130   56.85  5175.6   55.56  5177.3   55.53
  5229.2   54.58  5234.3   54.49    5303      53  5303.3   52.99  5351.1   52.09
  5364.6   51.83  5375.5   51.49  5395.5   50.88  5410.5   50.41  5430.5   49.79
  5435.5   49.64  5445.5   49.33  5450.5   49.18  5465.9    48.7  5470.9    48.9
  5475.5   48.77  5477.8   48.71  5495.9    48.2  5505.9    48.6  5520.9    48.8
    5531    48.5    5561    48.7  5602.4    48.2
BR D #Mann= 4
  4682.5      .1  4895.4    .015  5095.2      .1  5477.8      .2
BR D Banks=4895.4,5095.2
BC Design=,, 0 ,, 0 ,,,,,,
BC HTab HWMax=67.07
BC Use User HTab Curves=0
BC User HTab FreeFlow(D)= 0

Type RM Length L Ch R = 1 ,56355.6 ,115.6,115.6,115.6
BEGIN DESCRIPTION:
Downstream Section of Bridge/Culvert/Weir
END DESCRIPTION:
XS GIS Cut Line= 6
      3145333.19     13856469.24      3145156.57      13856366.3
      3145092.21     13856343.58      3144961.08     13856328.33
      3144674.43     13856297.84      3144451.16     13856257.23
#Sta/Elev= 30
  4682.5   47.31  4702.5   50.11  4732.5   50.11  4741.8   67.27  4772.4   65.73
  4798.9   67.39  4895.4   64.36  4929.5   47.83  4954.4   36.43  4958.7   28.09
  4958.9   34.91  4971.5   28.18  4975.1   31.77  4984.7   27.99  5012.7   27.76
  5024.8   35.01  5028.9   28.12  5043.1   34.57  5058.8   40.75  5074.4   41.06
  5095.2   59.51  5096.5   47.77    5129   59.66    5130   56.86  5364.6   51.84
  5465.9   48.71  5477.8   48.72  5495.9   48.21  5520.9   48.81  5602.4   48.21
#Mann= 4 , 1 , 0
  4682.5      .1       0  4895.4    .015       0  5095.2      .1       0
  5477.8      .2       0
#XS Ineff= 2 , 0
       0    4900      62    5100       0      56
Permanent Ineff=
       F       F
Bank Sta=4895.4,5095.2
XS Rating Curve= 0 ,0
Exp/Cntr=0.5,0.3

Type RM Length L Ch R = 1 ,56240.0 ,40,40,40
BEGIN DESCRIPTION:
Upstream Section of Bridge/Culvert/Weir
END DESCRIPTION:
XS GIS Cut Line= 4
       3145341.2     13856463.64      3145196.28     13856358.24
      3145012.61     13856207.97      3144608.17      13855907.4
#Sta/Elev= 30
    4682   71.26  4682.3   71.04  4701.2   70.55  4743.5   67.95  4809.4   66.09
  4852.3   63.79    4881   43.75  4894.3   40.72  4921.2   30.93  4931.2   28.73
  4950.2   27.92  4965.1   28.22    4974   28.99  4995.9   36.61  5020.6   36.89
    5026   37.58    5041   52.54  5057.9   51.49  5110.8   49.58  5173.6   48.84
    5235   48.59  5320.9   53.49  5360.9   51.49  5465.9   48.79  5470.9   48.99
  5495.9   48.29  5520.9   48.89    5531   48.59    5561   48.79  5602.4   48.29
#Mann= 3 , 1 , 0
    4682      .1       0  4852.3    .015       0    5041      .1       0
#XS Ineff= 2 , 0
       0    4850      64    5037       0   48.36
Permanent Ineff=
       F       F
Bank Sta=4852.3,5041
XS Rating Curve= 0 ,0
Exp/Cntr=0.5,0.3

Type RM Length L Ch R = 3 ,56220.0 ,,,
BEGIN DESCRIPTION:
MASTER RETARDER
Structure ID: H00-40
END DESCRIPTION:
Bridge Culvert--1,0,-1,-1, 0
Deck Dist Width WeirC Skew NumUp NumDn MinLoCord MaxHiCord MaxSubmerge Is_Ogee
10,20,2.6,0, 59, 59, , , 0.95, 0, 1,1,,
    4682  4682.3    4701  4701.2  4743.5  4746.4    4803  4809.4  4851.2  4852.3
  4855.4 4855.51  4855.6  4855.7 4855.99  4856.1 4856.21  4861.8    4881  4894.3
  4921.2  4931.2  4941.8  4950.2  4965.1    4974  4995.9  5001.3  5011.7  5020.6
    5026 5035.39  5035.5 5035.61  5036.8 5036.89    5037    5041  5057.9  5061.5
  5099.4  5110.8  5173.6  5175.3  5230.1    5235  5265.2  5275.2  5320.9  5335.9
  5360.9  5465.9  5470.9  5495.9  5505.9  5520.9    5531    5561  5602.4
   71.27   71.26   70.87   70.86    69.5   69.41   67.69    67.4   65.53   65.28
   64.57   64.86   65.11   65.37   66.15   72.25   72.25   71.85   70.49   69.54
   67.63   66.91   66.16   65.75   65.03   64.59   63.53   63.27   62.76   62.37
   62.13   61.71   61.71   55.61   55.54   55.54   55.53   55.31   54.37   54.17
      53   52.77   51.49   51.46   50.76    50.8   51.08    50.9    53.5    52.6
    51.5    48.8      49    48.3    48.7    48.9    48.6    48.8    48.3
   71.27   71.05   70.57   70.56   67.96   67.88   66.28    66.1   63.86    63.8
    61.6   61.52   61.46   61.38   61.18    61.1   61.02   58.75   57.39   56.44
   54.53   53.81   53.06   52.65   51.93   51.49   50.43   50.17   49.66   49.27
   49.03   48.61   48.61   48.61   48.54   48.54   48.56   52.55    51.5   51.37
      50   49.59   48.85   48.84   48.62    48.6   50.32   50.89    53.5    52.6
    51.5    48.8      49    48.3    48.7    48.9    48.6    48.8    48.3
    4682  4682.3    4701  4701.2  4743.5  4746.4    4803  4809.4  4851.2  4852.3
  4855.4 4855.51  4855.6  4855.7 4855.99  4856.1 4856.21  4861.8    4881  4894.3
  4921.2  4931.2  4941.8  4950.2  4965.1    4974  4995.9  5001.3  5011.7  5020.6
    5026 5035.39  5035.5 5035.61  5036.8 5036.89    5037    5041  5057.9  5061.5
  5099.4  5110.8  5173.6  5175.3  5230.1    5235  5265.2  5275.2  5320.9  5335.9
  5360.9  5465.9  5470.9  5495.9  5505.9  5520.9    5531    5561  5602.4
   71.27   71.26   70.87   70.86    69.5   69.41   67.69    67.4   65.53   65.28
   64.57   64.86   65.11   65.37   66.15   72.25   72.25   71.85   70.49   69.54
   67.63   66.91   66.16   65.75   65.03   64.59   63.53   63.27   62.76   62.37
   62.13   61.71   61.71   55.61   55.54   55.54   55.53   55.31   54.37   54.17
      53   52.77   51.49   51.46   50.76    50.8   51.08    50.9    53.5    52.6
    51.5    48.8      49    48.3    48.7    48.9    48.6    48.8    48.3
   71.17   70.95   70.47   70.46   67.86   67.78   66.18      66   63.76    63.7
    61.5   61.42   61.36   61.28   61.08      61   60.92   58.65   57.29   56.34
   54.43   53.71   52.96   52.55   51.83   51.39   50.33   50.07   49.56   49.17
   48.93   48.51   48.51   48.51   48.44   48.44   48.46   52.45    51.4   51.27
    49.9   49.49   48.75   48.74   48.52    48.5   50.22   50.79    53.4    52.5
    51.4    48.7    48.9    48.2    48.6    48.8    48.5    48.7    48.2
Pier Skew, UpSta & Num, DnSta & Num=  ,4894.3, 2 ,4894.3, 2 , 0 , 0 , 0 ,,
     1.5     1.5
   39.46   57.49
     1.5     1.5
   39.36   57.39
Pier Skew, UpSta & Num, DnSta & Num=  ,4931.2, 2 ,4931.2, 2 , 0 , 0 , 0 ,,
     1.5     1.5
   27.71   54.86
     1.5     1.5
   27.61   54.76
Pier Skew, UpSta & Num, DnSta & Num=  ,4965.1, 2 ,4965.1, 2 , 0 , 0 , 0 ,,
     1.5     1.5
   27.21   52.97
     1.5     1.5
   27.11   52.87
Pier Skew, UpSta & Num, DnSta & Num=  ,5001.3, 2 ,5001.3, 2 , 0 , 0 , 0 ,,
     1.5     1.5
   35.77   51.21
     1.5     1.5
   35.67   51.11
BR Coef= 1 , 1 , 0 ,1.25, 0 ,,,0.8,0,2,0,
WSPro=,,,, 1 ,,,, 0 ,,,, 0 ,,,,-1 ,-1 ,-1 , 0 , 0 , 0 , 0 , 0
BR U #Sta/Elev= 59
    4682   71.27  4682.3   71.05    4701   70.57  4701.2   70.56  4743.5   67.96
  4746.4   67.88    4803   66.28  4809.4    66.1  4851.2   63.86  4852.3    63.8
  4855.4    61.6 4855.51   61.52  4855.6   61.46  4855.7   61.38 4855.99   61.18
  4856.1    61.1 4856.21   61.02  4861.8   57.05    4881   43.76  4894.3   40.73
  4921.2   30.94  4931.2   28.74  4941.8   28.29  4950.2   27.93  4965.1   28.23
    4974      29  4995.9   36.62  5001.3   36.79  5011.7   36.85  5020.6    36.9
    5026   37.59 5035.39   46.95  5035.5   47.06 5035.61   47.17  5036.8   48.36
 5036.89   48.45    5037   48.56    5041   52.55  5057.9    51.5  5061.5   51.37
  5099.4      50  5110.8   49.59  5173.6   48.85  5175.3   48.84  5230.1   48.62
    5235    48.6  5265.2   50.32  5275.2   50.89  5320.9    53.5  5335.9    52.6
  5360.9    51.5  5465.9    48.8  5470.9      49  5495.9    48.3  5505.9    48.7
  5520.9    48.9    5531    48.6    5561    48.8  5602.4    48.3
BR U #Mann= 3
    4682      .1  4852.3    .015    5041      .1
BR U Banks=4852.3,5041
BR D #Sta/Elev= 59
    4682   71.17  4682.3   70.95    4701   70.47  4701.2   70.46  4743.5   67.86
  4746.4   67.78    4803   66.18  4809.4      66  4851.2   63.76  4852.3    63.7
  4855.4    61.5 4855.51   61.42  4855.6   61.36  4855.7   61.28 4855.99   61.08
  4856.1      61 4856.21   60.92  4861.8   56.95    4881   43.66  4894.3   40.63
  4921.2   30.84  4931.2   28.64  4941.8   28.19  4950.2   27.83  4965.1   28.13
    4974    28.9  4995.9   36.52  5001.3   36.69  5011.7   36.75  5020.6    36.8
    5026   37.49 5035.39   46.85  5035.5   46.96 5035.61   47.07  5036.8   48.26
 5036.89   48.35    5037   48.46    5041   52.45  5057.9    51.4  5061.5   51.27
  5099.4    49.9  5110.8   49.49  5173.6   48.75  5175.3   48.74  5230.1   48.52
    5235    48.5  5265.2   50.22  5275.2   50.79  5320.9    53.4  5335.9    52.5
  5360.9    51.4  5465.9    48.7  5470.9    48.9  5495.9    48.2  5505.9    48.6
  5520.9    48.8    5531    48.5    5561    48.7  5602.4    48.2
BR D #Mann= 3
    4682      .1  4852.3    .015    5041      .1
BR D Banks=4852.3,5041
BC Design=,, 0 ,, 0 ,,,,,,
BC HTab HWMax=71.26
BC Use User HTab Curves=0
BC User HTab FreeFlow(D)= 0

Type RM Length L Ch R = 1 ,56200.0 ,6.1,6.1,6.1
BEGIN DESCRIPTION:
Downstream Section of Bridge/Culvert/Weir
END DESCRIPTION:
XS GIS Cut Line= 4
       3145362.4     13856429.72      3145217.48     13856324.32
      3145033.81     13856174.05      3144629.37     13855873.48
#Sta/Elev= 30
    4682   71.19  4682.3   70.97  4701.2   70.48  4743.5   67.88  4809.4   66.02
  4852.3   63.72    4881   43.68  4894.3   40.65  4921.2   30.86  4931.2   28.66
  4950.2   27.85  4965.1   28.15    4974   28.92  4995.9   36.54  5020.6   36.82
    5026   37.51    5041   52.47  5057.9   51.42  5110.8   49.51  5173.6   48.77
    5235   48.52  5320.9   53.42  5360.9   51.42  5465.9   48.72  5470.9   48.92
  5495.9   48.22  5520.9   48.82    5531   48.52    5561   48.72  5602.4   48.22
#Mann= 3 , 1 , 0
    4682      .1       0  4852.3    .015       0    5041      .1       0
#XS Ineff= 2 , 0
       0    4850      64    5037       0   48.36
Permanent Ineff=
       F       F
Bank Sta=4852.3,5041
XS Rating Curve= 0 ,0
Exp/Cntr=0.5,0.3

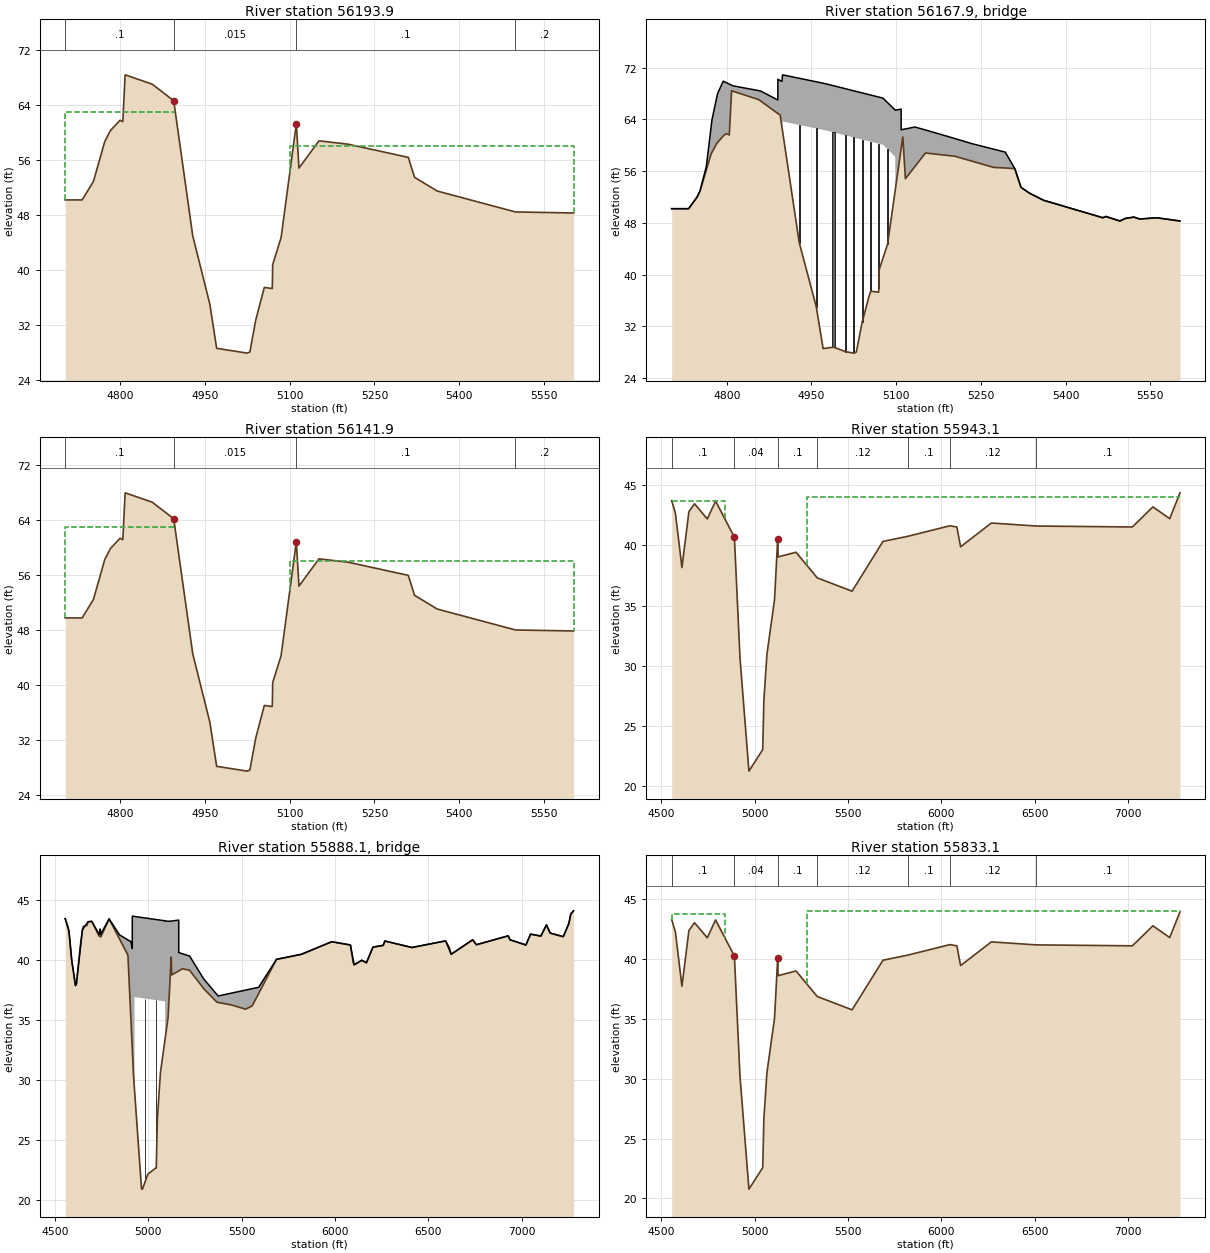
Type RM Length L Ch R = 1 ,56193.9 ,52,52,52
BEGIN DESCRIPTION:
Upstream Section of Bridge/Culvert/Weir
END DESCRIPTION:
XS GIS Cut Line= 6
      3145340.99     13856415.35      3145102.56     13856206.91
      3145051.69     13856117.92      3144992.47     13855977.82
      3144960.69     13855850.71      3144945.79     13855653.89
#Sta/Elev= 30
  4702.5   50.17  4732.5   50.17  4752.5   52.87  4772.5   58.67  4782.5   60.27
  4799.5   61.77  4804.5   61.57  4808.6   68.39  4856.5   67.03  4894.6   64.62
  4928.3   44.94  4958.5   35.01  4970.6   28.56  5024.7   27.86  5029.4   28.02
  5039.8   32.67    5055   37.43  5068.9   37.27  5069.3   38.05  5069.8   40.74
  5084.7   44.69  5111.7   61.26  5116.3    54.8  5151.8   58.78  5203.8   58.28
  5309.9   56.37  5320.9   53.47  5360.9   51.47  5499.6   48.42  5602.4   48.27
#Mann= 4 , 1 , 0
  4702.5      .1       0  4894.6    .015       0  5111.7      .1       0
  5499.6      .2       0
#XS Ineff= 2 , 0
       0    4897      63    5100       0      58
Permanent Ineff=
       F       F
Bank Sta=4894.6,5111.7
XS Rating Curve= 0 ,0
Exp/Cntr=0.5,0.3

Type RM Length L Ch R = 3 ,56167.9 ,,,
BEGIN DESCRIPTION:
UNION PACIFIC RAILROAD
Structure ID: H00-39,,,,
END DESCRIPTION:
Bridge Culvert--1,0,-1,-1, 0
Deck Dist Width WeirC Skew NumUp NumDn MinLoCord MaxHiCord MaxSubmerge Is_Ogee
10,32,2.6,0, 48, 48, , , 0.95, 0, 1,1,,
  4702.5  4732.5  4747.5  4752.5  4763.8  4772.5  4773.8  4782.5  4783.8  4793.8
  4799.5  4804.5  4808.6  4811.1  4856.5    4860 4890.39  4890.5  4894.6  4897.7
 4897.81  4898.7  4973.7  5076.6 5098.39  5098.5  5108.7 5108.81  5111.7  5116.3
  5133.1  5151.8  5203.8  5233.8  5272.2    5293  5309.9  5320.9  5335.9  5360.9
  5465.9  5470.9  5495.9  5505.9  5520.9    5531    5561  5602.4
    50.2    50.2      52    52.9    56.7   62.96    63.9   67.47      68    69.9
   69.66   69.45   69.28   69.18   68.44   68.38   66.99   70.19      70   69.86
   69.97   70.88   69.53   67.28   65.42   65.41   65.59   62.39   62.44   62.52
   62.82   62.36   61.04   60.25    59.4   58.94    56.4    53.5    52.6    51.5
    48.8      49    48.3    48.7    48.9    48.6    48.8    48.3
   50.19   50.19   51.99   52.89   56.17   58.69    58.9   60.29   60.42   61.42
   61.79   61.59   68.41   68.34   67.05   66.83   64.91    64.9   64.64   62.83
   62.77   63.67   62.32   60.07   58.21   53.18   59.44   59.51   61.28   54.82
    56.7    58.8    58.3   57.55   56.58   56.48   56.39   53.49   52.59   51.49
   48.79   48.99   48.29   48.69   48.89   48.59   48.79   48.29
  4702.5  4732.5  4747.5  4752.5  4763.8  4772.5  4773.8  4782.5  4783.8  4793.8
  4799.5  4804.5  4808.6  4811.1  4856.5    4860 4890.39  4890.5  4894.6  4897.7
 4897.81  4898.7  4973.7  5076.6 5098.39  5098.5  5108.7 5108.81  5111.7  5116.3
  5133.1  5151.8  5203.8  5233.8  5272.2    5293  5309.9  5320.9  5335.9  5360.9
  5465.9  5470.9  5495.9  5505.9  5520.9    5531    5561  5602.4
    50.2    50.2      52    52.9    56.7   62.96    63.9   67.47      68    69.9
   69.66   69.45   69.28   69.18   68.44   68.38   66.99   70.19      70   69.86
   69.97   70.88   69.53   67.28   65.42   65.41   65.59   62.39   62.44   62.52
   62.82   62.36   61.04   60.25    59.4   58.94    56.4    53.5    52.6    51.5
    48.8      49    48.3    48.7    48.9    48.6    48.8    48.3
   50.09   50.09   51.89   52.79   56.07   58.59    58.8   60.19   60.32   61.32
   61.69   61.49   68.31   68.24   66.95   66.73   64.81    64.8   64.54   62.73
   62.67   63.57   62.22   59.97   58.11   53.08   59.34   59.41   61.18   54.72
    56.6    58.7    58.2   57.45   56.48   56.38   56.29   53.39   52.49   51.39
   48.69   48.89   48.19   48.59   48.79   48.49   48.69   48.19
Pier Skew, UpSta & Num, DnSta & Num=  ,4928.3, 2 ,4928.3, 2 , 0 , 0 , 0 ,,
     1.2     1.2
   43.76   64.15
     1.2     1.2
   43.66   64.05
Pier Skew, UpSta & Num, DnSta & Num=  ,4958.5, 2 ,4958.5, 2 , 0 , 0 , 0 ,,
     1.2     1.2
   33.71    63.6
     1.2     1.2
   33.61    63.5
Pier Skew, UpSta & Num, DnSta & Num=  ,4989, 2 ,4989, 2 , 0 , 0 , 0 ,,
       7       7
   27.69   63.07
       7       7
   27.59   62.97
Pier Skew, UpSta & Num, DnSta & Num=  ,5010.3, 2 ,5010.3, 2 , 0 , 0 , 0 ,,
     1.2     1.2
    27.1   62.53
     1.2     1.2
      27   62.43
Pier Skew, UpSta & Num, DnSta & Num=  ,5024.7, 2 ,5024.7, 2 , 0 , 0 , 0 ,,
     1.2     1.2
   26.89   62.21
     1.2     1.2
   26.79   62.11
Pier Skew, UpSta & Num, DnSta & Num=  ,5039.8, 2 ,5039.8, 2 , 0 , 0 , 0 ,,
     1.2     1.2
   31.42   61.88
     1.2     1.2
   31.32   61.78
Pier Skew, UpSta & Num, DnSta & Num=  ,5055, 2 ,5055, 2 , 0 , 0 , 0 ,,
     1.2     1.2
    36.3   61.55
     1.2     1.2
    36.2   61.45
Pier Skew, UpSta & Num, DnSta & Num=  ,5069.2, 2 ,5069.2, 2 , 0 , 0 , 0 ,,
     1.2     1.2
   36.29   61.25
     1.2     1.2
   36.19   61.15
Pier Skew, UpSta & Num, DnSta & Num=  ,5084.6, 2 ,5084.6, 2 , 0 , 0 , 0 ,,
     1.2     1.2
   43.52   60.44
     1.2     1.2
   43.42   60.34
Abutment Skew #Up #Dn= , 2 , 2
  4897.7  4970.7
   62.85   28.58
  4897.7  4970.7
   62.75   28.48
Abutment Skew #Up #Dn= , 2 , 2
    5069 5098.59
   37.49   58.21
    5069 5098.59
   37.39   58.11
BR Coef= 1 , 1 , 0 ,1.25, 0 ,,,0.8,0,2,0,
WSPro=,,,, 1 ,,,, 0 ,,,, 0 ,,,,-1 ,-1 ,-1 , 0 , 0 , 0 , 0 , 0
BR U #Sta/Elev= 71
  4702.5   50.19  4732.5   50.19  4747.5   51.99  4752.5   52.89  4763.8   56.17
  4772.5   58.69  4773.8    58.9  4782.5   60.29  4783.8   60.42  4793.8   61.42
  4794.5   61.49  4799.5   61.79  4804.5   61.59  4808.6   68.41  4811.1   68.34
  4856.5   67.05    4860   66.83 4890.39   64.91  4890.5    64.9 4890.61   64.89
  4894.6   64.64  4897.7   62.83 4897.81   62.77  4897.9   62.71  4898.7   62.25
  4928.3   44.96  4958.5   35.03  4970.6   28.58  4970.7   28.58  4973.7   28.62
    4989    28.8  5010.3   28.11  5024.7   27.88  5029.4   28.04  5039.8   32.69
    5052   36.68    5055   37.45  5068.9   37.29    5069   37.49  5069.3   38.07
  5069.8   40.76  5076.6   42.56  5084.7   44.71 5098.39   53.11  5098.5   53.18
  5098.6   53.24 5108.59   59.37  5108.7   59.44 5108.81   59.51  5111.7   61.28
  5116.3   54.82  5133.1    56.7  5151.8    58.8  5180.5   58.52  5203.8    58.3
  5233.8   57.55  5272.2   56.58    5293   56.48  5309.9   56.39  5320.9   53.49
  5335.9   52.59  5360.9   51.49  5465.9   48.79  5470.9   48.99  5495.9   48.29
  5499.6   48.44  5505.9   48.69  5520.9   48.89    5531   48.59    5561   48.79
  5602.4   48.29
BR U #Mann= 4
  4702.5      .1  4894.6    .015  5111.7      .1  5499.6      .2
BR U Banks=4894.6,5111.7
BR D #Sta/Elev= 71
  4702.5   50.09  4732.5   50.09  4747.5   51.89  4752.5   52.79  4763.8   56.07
  4772.5   58.59  4773.8    58.8  4782.5   60.19  4783.8   60.32  4793.8   61.32
  4794.5   61.39  4799.5   61.69  4804.5   61.49  4808.6   68.31  4811.1   68.24
  4856.5   66.95    4860   66.73 4890.39   64.81  4890.5    64.8 4890.61   64.79
  4894.6   64.54  4897.7   62.73 4897.81   62.67  4897.9   62.61  4898.7   62.15
  4928.3   44.86  4958.5   34.93  4970.6   28.48  4970.7   28.48  4973.7   28.52
    4989    28.7  5010.3   28.01  5024.7   27.78  5029.4   27.94  5039.8   32.59
    5052   36.58    5055   37.35  5068.9   37.19    5069   37.39  5069.3   37.97
  5069.8   40.66  5076.6   42.46  5084.7   44.61 5098.39   53.01  5098.5   53.08
  5098.6   53.14 5108.59   59.27  5108.7   59.34 5108.81   59.41  5111.7   61.18
  5116.3   54.72  5133.1    56.6  5151.8    58.7  5180.5   58.42  5203.8    58.2
  5233.8   57.45  5272.2   56.48    5293   56.38  5309.9   56.29  5320.9   53.39
  5335.9   52.49  5360.9   51.39  5465.9   48.69  5470.9   48.89  5495.9   48.19
  5499.6   48.34  5505.9   48.59  5520.9   48.79    5531   48.49    5561   48.69
  5602.4   48.19
BR D #Mann= 4
  4702.5      .1  4894.6    .015  5111.7      .1  5499.6      .2
BR D Banks=4894.6,5111.7
BC Design=,, 0 ,, 0 ,,,,,,
BC HTab HWMax=68.39
BC Use User HTab Curves=0
BC User HTab FreeFlow(D)= 0

Type RM Length L Ch R = 1 ,56141.9 ,198.8,198.8,198.8
BEGIN DESCRIPTION:
Downstream Section of Bridge/Culvert/Weir
END DESCRIPTION:
XS GIS Cut Line= 6
      3145375.97     13856376.87      3145137.54     13856168.43
      3145086.67     13856079.44      3145027.45     13855939.34
      3144995.67     13855812.23      3144980.76     13855615.41
#Sta/Elev= 30
  4702.5   49.78  4732.5   49.78  4752.5   52.48  4772.5   58.28  4782.5   59.88
  4799.5   61.38  4804.5   61.18  4808.6      68  4856.5   66.64  4894.6   64.23
  4928.3   44.55  4958.5   34.62  4970.6   28.17  5024.7   27.47  5029.4   27.63
  5039.8   32.28    5055   37.04  5068.9   36.88  5069.3   37.66  5069.8   40.35
  5084.7    44.3  5111.7   60.87  5116.3   54.41  5151.8   58.39  5203.8   57.89
  5309.9   55.98  5320.9   53.08  5360.9   51.08  5499.6   48.03  5602.4   47.88
#Mann= 4 , 1 , 0
  4702.5      .1       0  4894.6    .015       0  5111.7      .1       0
  5499.6      .2       0
#XS Ineff= 2 , 0
       0    4897      63    5100       0      58
Permanent Ineff=
       F       F
Bank Sta=4894.6,5111.7
XS Rating Curve= 0 ,0
Exp/Cntr=0.5,0.3

Type RM Length L Ch R = 1 ,55943.1 ,110,110,110
BEGIN DESCRIPTION:
Upstream Section of Bridge/Culvert/Weir
END DESCRIPTION:
XS GIS Cut Line= 6
      3145451.91     13856411.94      3145356.81     13856337.98
      3145203.66     13855313.39        3145098.     13855062.98
      3144915.71     13854714.97      3144403.34      13853975.3
#Sta/Elev= 30
  4555.6   43.72  4575.6   42.68  4610.6   38.16  4647.8    42.8  4677.8   43.46
  4746.3    42.2  4790.7   43.69  4891.4   40.68  4921.3   30.66  4969.2   21.23
  5043.1   23.02  5049.2   27.09  5065.5   30.93  5106.5   35.51  5123.2   40.52
  5125.4   39.04  5221.5   39.43    5335    37.3  5521.5   36.19  5686.9   40.33
  5818.5   40.75    6045   41.63  6082.5   41.53  6102.5   39.88  6267.1   41.86
  6505.9   41.61  7022.1   41.53  7132.1    43.2  7222.1   42.22  7277.1   44.37
#Mann= 7 , 1 , 0
  4555.6      .1       0  4891.4     .04       0  5123.2      .1       0
    5335     .12       0  5818.5      .1       0    6045     .12       0
  6505.9      .1       0
#XS Ineff= 2 , 0
       0    4840    43.7    5280       0      44
Permanent Ineff=
       F       F
Bank Sta=4891.4,5123.2
XS Rating Curve= 0 ,0
Exp/Cntr=0.5,0.3

Type RM Length L Ch R = 3 ,55888.1 ,,,
BEGIN DESCRIPTION:
WAYSIDE ROAD - 35 Degree Skew
Structure ID: H00-38
END DESCRIPTION:
Bridge Culvert--1,0,-1,-1, 0
Deck Dist Width WeirC Skew NumUp NumDn MinLoCord MaxHiCord MaxSubmerge Is_Ogee
10,90,2.6,0, 60, 60, , , 0.95, 0, 1,1,,
  4555.6  4575.6  4590.6  4610.6  4615.6  4647.8  4677.8  4697.8  4737.8  4742.8
  4746.3  4790.7  4846.4  4891.4  4907.1 4914.69  4914.8  4921.3 4926.68 4926.77
 5090.43  5090.5 5090.61  5106.5  5123.2  5125.4  5163.5 5163.61  5221.5  5297.9
  5374.4  5521.5  5556.9  5591.3  5686.9  5821.2  5982.5  6082.5  6102.5  6143.3
  6168.3  6203.3  6258.3  6267.1  6412.1  6592.1  6622.1  6737.1  6757.1  6927.1
  6937.1  7022.1  7047.1  7102.1  7132.1  7152.1  7222.1  7252.1  7262.1  7277.1
   43.41   42.37   39.93   37.85   37.99   42.49   43.15   43.18   42.09   42.54
   42.13   43.39   42.06   41.64    41.5   40.92   43.62   43.61   43.59   43.59
   43.23   43.22   43.22   43.19   43.21   43.21   43.29   40.59    40.3   38.38
   36.98   37.47   37.59    37.7   40.03   40.45   41.49   41.22   39.57   39.95
   39.74   41.04   41.19   41.55   41.01   41.56   40.45   41.65   41.24   41.98
   41.65   41.22   42.12   41.96   42.89   42.21   41.91      43   43.79   44.06
   43.41   42.37   39.93   37.85   37.99   42.49   43.15   43.18   41.94   42.53
   41.89   43.38   41.72   40.37   35.11   32.57   32.53   30.35   29.17   36.89
   36.53   36.52   33.42    35.2   40.21   38.73   39.07   39.07   39.12   37.58
   36.44   35.88   36.16   37.18   40.02   40.45   41.49   41.22   39.57   39.95
   39.74   41.04   41.19   41.55   41.01   41.56   40.45   41.65   41.24   41.98
   41.65   41.22   42.12   41.96   42.89   42.21   41.91      43   43.79   44.06
  4555.6  4575.6  4590.6  4610.6  4615.6  4647.8  4677.8  4697.8  4737.8  4742.8
  4746.3  4790.7  4846.4  4891.4  4907.1 4914.69  4914.8  4921.3 4926.68 4926.77
 5090.43  5090.5 5090.61  5106.5  5123.2  5125.4  5163.5 5163.61  5221.5  5297.9
  5374.4  5521.5  5556.9  5591.3  5686.9  5821.2  5982.5  6082.5  6102.5  6143.3
  6168.3  6203.3  6258.3  6267.1  6412.1  6592.1  6622.1  6737.1  6757.1  6927.1
  6937.1  7022.1  7047.1  7102.1  7132.1  7152.1  7222.1  7252.1  7262.1  7277.1
   43.41   42.37   39.93   37.85   37.99   42.49   43.15   43.18   42.09   42.54
   42.13   43.39   42.06   41.64    41.5   40.92   43.62   43.61   43.59   43.59
   43.23   43.22   43.22   43.19   43.21   43.21   43.29   40.59    40.3   38.38
   36.98   37.47   37.59    37.7   40.03   40.45   41.49   41.22   39.57   39.95
   39.74   41.04   41.19   41.55   41.01   41.56   40.45   41.65   41.24   41.98
   41.65   41.22   42.12   41.96   42.89   42.21   41.91      43   43.79   44.06
   43.25   42.21   39.77   37.69   37.83   42.33   42.99   43.02   41.78   42.37
   41.73   43.22   41.56   40.21   34.95   32.41   32.37   30.19   29.01   36.73
   36.37   36.36   33.26   35.04   40.05   38.57   38.91   38.91   38.96   37.42
   36.28   35.72      36   37.02   39.86   40.29   41.33   41.06   39.41   39.79
   39.58   40.88   41.03   41.39   40.85    41.4   40.29   41.49   41.08   41.82
   41.49   41.06   41.96    41.8   42.73   42.05   41.75   42.84   43.63    43.9
Pier Skew, UpSta & Num, DnSta & Num=  ,4983.2, 2 ,4983.2, 2 , 0 , 0 , 0 ,,
       2       2
   20.48   37.76
       2       2
   20.32    37.6
Pier Skew, UpSta & Num, DnSta & Num=  ,5040.3, 2 ,5040.3, 2 , 0 , 0 , 0 ,,
       2       2
   21.66   37.64
       2       2
    21.5   37.48
BR Coef= 1 , 1 , 0 ,1.25, 0 ,,,0.8,0,2,0,
WSPro=,,,, 1 ,,,, 0 ,,,, 0 ,,,,-1 ,-1 ,-1 , 0 , 0 , 0 , 0 , 0
BR U #Sta/Elev= 94
  4555.6   43.41  4570.6   42.69  4575.6   42.37  4590.6   39.93  4610.6   37.85
  4615.6   37.99  4635.6   41.02  4647.8   42.49  4652.8   42.77  4672.8   42.85
  4677.8   43.15  4697.8   43.18  4720.6   42.47  4737.8   41.94  4740.6   42.27
  4742.8   42.53  4746.3   41.89  4777.7   42.94  4790.7   43.38  4846.4   41.72
  4891.4   40.37  4907.1   35.11  4910.7    33.9 4914.69   32.57  4914.8   32.53
 4914.91   32.49  4921.3   30.35 4926.68   29.17 4926.77   29.15 4926.86   29.13
  4956.9   22.55  4964.2   20.94  4969.2   20.92  4979.5   21.37  4998.3   22.17
  5043.1   22.71  5049.2   26.78  5065.5   30.62 5090.43    33.4  5090.5   33.41
 5090.61   33.42  5106.5    35.2  5110.5    36.4  5123.2   40.21  5125.4   38.73
 5163.39   39.06  5163.5   39.07 5163.61   39.07  5183.4   39.24  5221.5   39.12
  5226.9   39.01  5297.9   37.58  5300.5   37.53    5335   36.99  5368.3   36.46
  5374.4   36.44  5435.6   36.26  5444.1   36.24  5521.5   35.88  5556.9   36.16
  5591.3   37.18  5686.9   40.02  5781.8   40.32  5818.5   40.44  5821.2   40.45
  5982.5   41.49    6045   41.32  6082.5   41.22  6097.5   39.76  6102.5   39.57
  6103.3   39.58  6143.3   39.95  6168.3   39.74  6203.3   41.04  6258.3   41.19
  6267.1   41.55  6412.1   41.01  6505.9    41.3  6592.1   41.56  6612.1   41.01
  6622.1   40.45  6737.1   41.65  6757.1   41.24  6927.1   41.98  6937.1   41.65
  7022.1   41.22  7047.1   42.12  7102.1   41.96  7132.1   42.89  7152.1   42.21
  7222.1   41.91  7252.1      43  7262.1   43.79  7277.1   44.06
BR U #Mann= 7
  4555.6      .1  4891.4     .04  5123.2      .1    5335     .12  5818.5      .1
    6045     .12  6505.9      .1
BR U Banks=4891.4,5123.2
BR D #Sta/Elev= 94
  4555.6   43.25  4570.6   42.53  4575.6   42.21  4590.6   39.77  4610.6   37.69
  4615.6   37.83  4635.6   40.86  4647.8   42.33  4652.8   42.61  4672.8   42.69
  4677.8   42.99  4697.8   43.02  4720.6   42.31  4737.8   41.78  4740.6   42.11
  4742.8   42.37  4746.3   41.73  4777.7   42.78  4790.7   43.22  4846.4   41.56
  4891.4   40.21  4907.1   34.95  4910.7   33.74 4914.69   32.41  4914.8   32.37
 4914.91   32.33  4921.3   30.19 4926.68   29.01 4926.77   28.99 4926.86   28.97
  4956.9   22.39  4964.2   20.78  4969.2   20.76  4979.5   21.21  4998.3   22.01
  5043.1   22.55  5049.2   26.62  5065.5   30.46 5090.43   33.24  5090.5   33.25
 5090.61   33.26  5106.5   35.04  5110.5   36.24  5123.2   40.05  5125.4   38.57
 5163.39    38.9  5163.5   38.91 5163.61   38.91  5183.4   39.08  5221.5   38.96
  5226.9   38.85  5297.9   37.42  5300.5   37.37    5335   36.83  5368.3    36.3
  5374.4   36.28  5435.6    36.1  5444.1   36.08  5521.5   35.72  5556.9      36
  5591.3   37.02  5686.9   39.86  5781.8   40.16  5818.5   40.28  5821.2   40.29
  5982.5   41.33    6045   41.16  6082.5   41.06  6097.5    39.6  6102.5   39.41
  6103.3   39.42  6143.3   39.79  6168.3   39.58  6203.3   40.88  6258.3   41.03
  6267.1   41.39  6412.1   40.85  6505.9   41.14  6592.1    41.4  6612.1   40.85
  6622.1   40.29  6737.1   41.49  6757.1   41.08  6927.1   41.82  6937.1   41.49
  7022.1   41.06  7047.1   41.96  7102.1    41.8  7132.1   42.73  7152.1   42.05
  7222.1   41.75  7252.1   42.84  7262.1   43.63  7277.1    43.9
BR D #Mann= 7
  4555.6      .1  4891.4     .04  5123.2      .1    5335     .12  5818.5      .1
    6045     .12  6505.9      .1
BR D Banks=4891.4,5123.2
BC Design=,, 0 ,, 0 ,,,,,,
BC HTab HWMax=44.37
BC Use User HTab Curves=0
BC User HTab FreeFlow(D)= 0

Type RM Length L Ch R = 1 ,55833.1 ,51.6,51.6,51.6
BEGIN DESCRIPTION:
Downstream Section of Bridge/Culvert/Weir
END DESCRIPTION:
XS GIS Cut Line= 6
      3145519.36     13856325.05      3145424.27     13856251.08
      3145271.12     13855226.49      3145165.46     13854976.08
      3144983.17     13854628.07      3144470.79     13853888.41
#Sta/Elev= 30
  4555.6   43.27  4575.6   42.23  4610.6   37.71  4647.8   42.35  4677.8   43.01
  4746.3   41.75  4790.7   43.24  4891.4   40.23  4921.3   30.21  4969.2   20.78
  5043.1   22.57  5049.2   26.64  5065.5   30.48  5106.5   35.06  5123.2   40.07
  5125.4   38.59  5221.5   38.98    5335   36.85  5521.5   35.74  5686.9   39.88
  5818.5    40.3    6045   41.18  6082.5   41.08  6102.5   39.43  6267.1   41.41
  6505.9   41.16  7022.1   41.08  7132.1   42.75  7222.1   41.77  7277.1   43.92
#Mann= 7 , 1 , 0
  4555.6      .1       0  4891.4     .04       0  5123.2      .1       0
    5335     .12       0  5818.5      .1       0    6045     .12       0
  6505.9      .1       0
#XS Ineff= 2 , 0
       0    4840    43.7    5280       0      44
Permanent Ineff=
       F       F
Bank Sta=4891.4,5123.2
XS Rating Curve= 0 ,0
Exp/Cntr=0.5,0.3