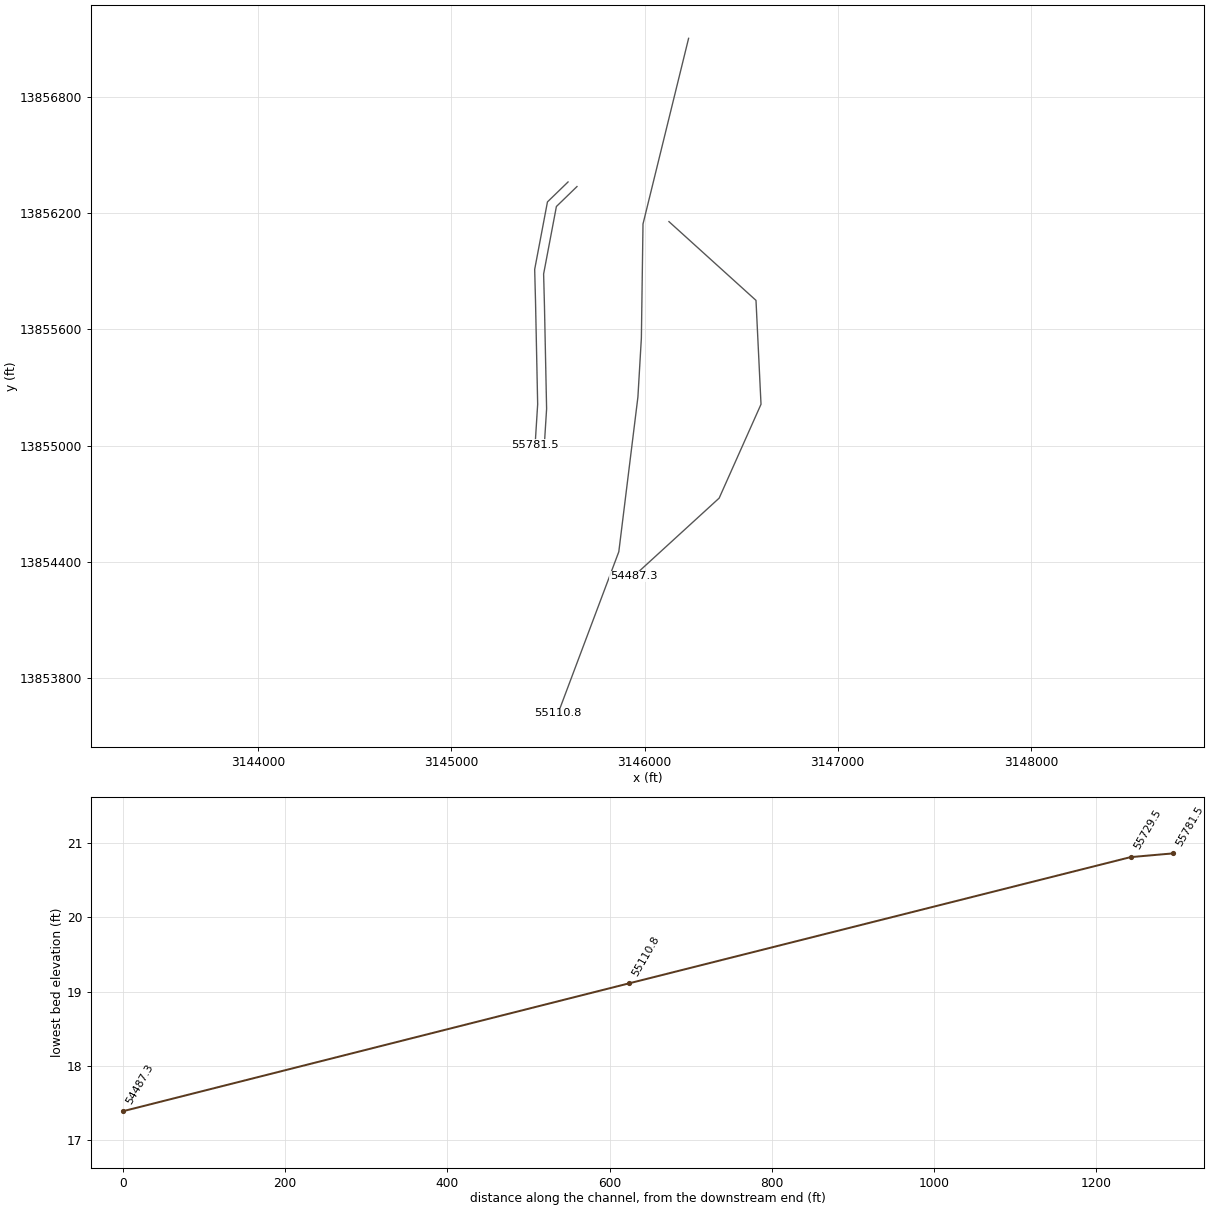
HEC-RAS study H100-00-00.prj: H100-00-00

--- H100-00-00.g01 (geometry) --- (continued)

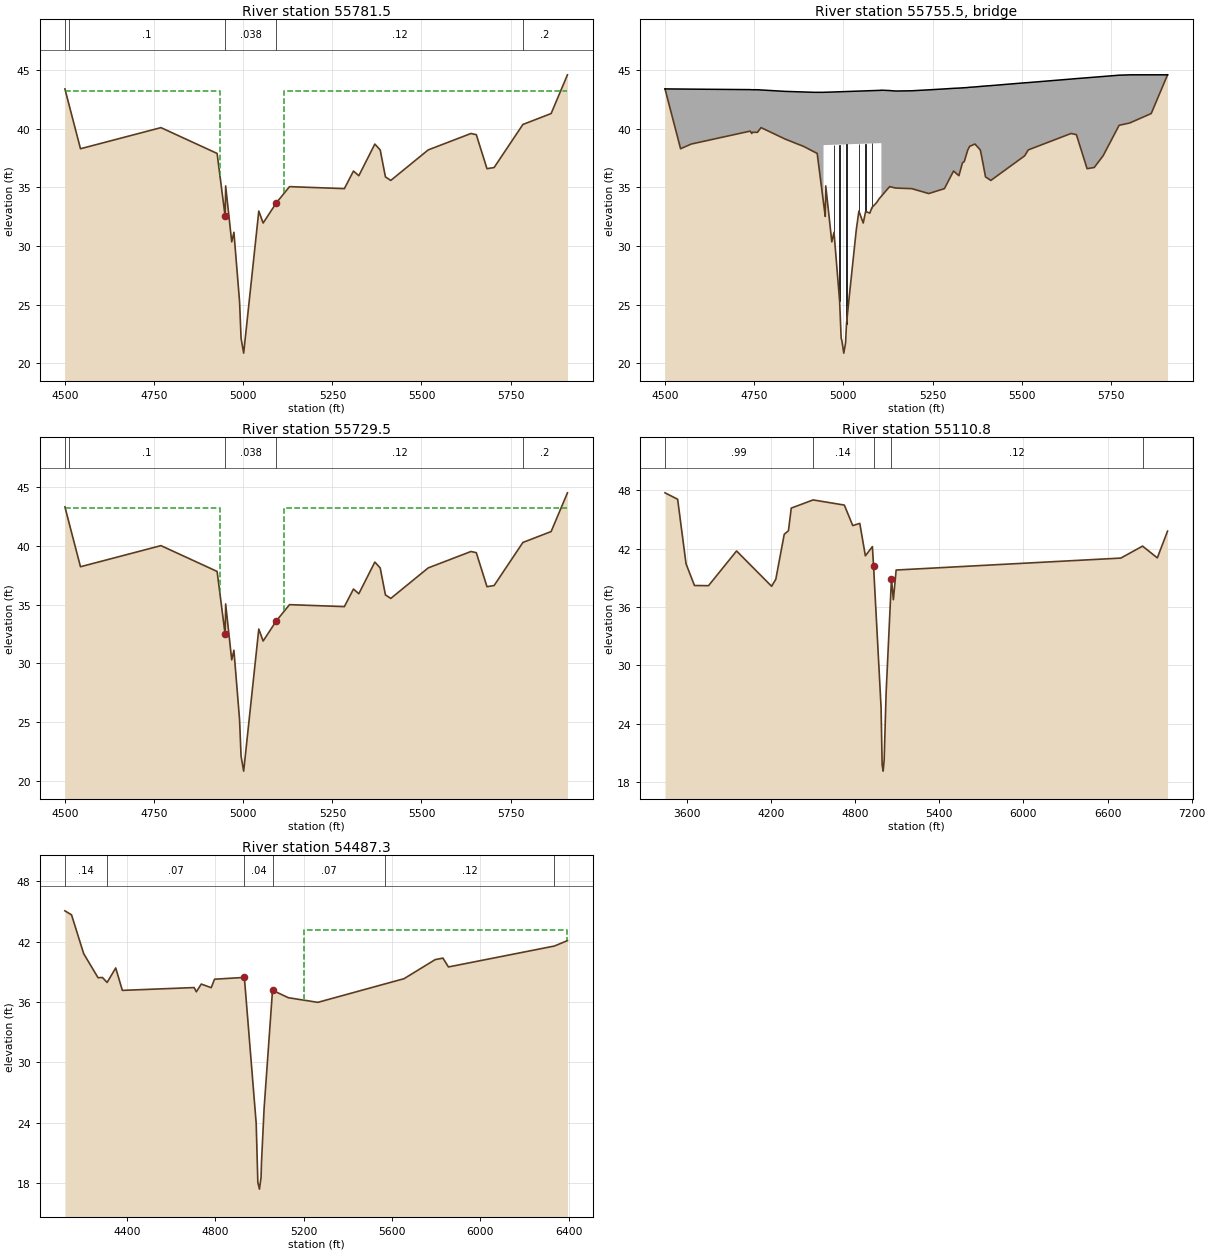
Type RM Length L Ch R = 1 ,55781.5 ,52,52,52
BEGIN DESCRIPTION:
Upstream Section of Bridge/Culvert/Weir
END DESCRIPTION:
XS GIS Cut Line= 6
      3145604.17     13856362.73      3145497.64     13856259.64
       3145431.5     13855910.93       3145435.9      13855743.5
      3145446.94     13855213.47      3145433.78     13855004.38
#Sta/Elev= 30
  4499.3   43.38    4543   38.28  4768.8   40.08 4926.39   37.88 4948.99   32.51
 4950.38   35.11 4967.44   30.34 4973.59   31.16 4989.43   25.25 4993.68   22.13
 5000.95   20.86 5043.39   32.97  5055.6   31.95 5092.92   33.68 5129.64   35.05
 5283.53   34.88  5309.1   36.38  5324.1   35.98  5369.1   38.68  5384.1   38.18
  5398.8   35.88  5413.8   35.58  5518.8   38.18  5638.8   39.58  5653.8   39.48
  5683.8   36.58  5703.8   36.68  5784.6   40.35  5863.8   41.28  5909.6   44.58
#Mann= 5 , 1 , 0
  4499.3      .2       0  4509.6      .1       0 4948.99    .038       0
 5092.92     .12       0  5784.6      .2       0
#XS Ineff= 2 , 0
       0    4935    43.2    5115       0    43.2
Permanent Ineff=
       F       F
Bank Sta=4948.99,5092.92
XS Rating Curve= 0 ,0
Exp/Cntr=0.5,0.3

Type RM Length L Ch R = 3 ,55755.5 ,,,
BEGIN DESCRIPTION:
HOUSTON BELT RAILROAD - 30 Degree Skew
Structure ID: H00-37
END DESCRIPTION:
Bridge Culvert--1,0,-1,-1, 0
Deck Dist Width WeirC Skew NumUp NumDn MinLoCord MaxHiCord MaxSubmerge Is_Ogee
10,32,2.6,0, 42, 42, , , 0.95, 0, 1,1,,
  4499.3    4543    4573    4738    4743  4743.8  4758.8  4768.8 4836.07 4887.59
  4916.8 4926.39 4944.05 4944.14 5106.49  5106.6 5129.64 5146.53 5191.39 5239.36
 5283.53  5309.1  5324.1  5334.1  5339.1  5349.1  5354.1  5369.1  5384.1  5398.8
  5413.8  5508.8  5518.8  5638.8  5653.8  5683.8  5703.8  5728.8  5773.8  5803.8
  5863.8  5909.6
    43.4   43.39   43.38   43.34   43.33   43.33   43.33   43.31   43.19   43.14
   43.11   43.11   43.11   43.11   43.28   43.29   43.26   43.22   43.24   43.32
    43.4   43.45   43.47   43.49    43.5   43.52   43.54   43.57   43.61   43.65
   43.68   43.92   43.94   44.24   44.28   44.35    44.4   44.46   44.57    44.6
    44.6    44.6
    43.4    38.3    38.7    39.8    39.6    39.7    39.7    40.1   39.13   38.51
   38.05    37.9    33.7   38.61   38.78   34.26   35.07   34.95    34.9   34.48
    34.9    36.4      36    37.1    37.2    38.2    38.5    38.7    38.2    35.9
    35.6    37.7    38.2    39.6    39.5    36.6    36.7    37.7    40.3    40.5
    41.3    44.6
  4499.3    4543    4573    4738    4743  4743.8  4758.8  4768.8 4836.07 4887.59
  4916.8 4926.39 4944.05 4944.14 5106.49  5106.6 5129.64 5146.53 5191.39 5239.36
 5283.53  5309.1  5324.1  5334.1  5339.1  5349.1  5354.1  5369.1  5384.1  5398.8
  5413.8  5508.8  5518.8  5638.8  5653.8  5683.8  5703.8  5728.8  5773.8  5803.8
  5863.8  5909.6
    43.4   43.39   43.38   43.34   43.33   43.33   43.33   43.31   43.19   43.14
   43.11   43.11   43.11   43.11   43.28   43.29   43.26   43.22   43.24   43.32
    43.4   43.45   43.47   43.49    43.5   43.52   43.54   43.57   43.61   43.65
   43.68   43.92   43.94   44.24   44.28   44.35    44.4   44.46   44.57    44.6
    44.6    44.6
   43.36   38.26   38.66   39.76   39.56   39.66   39.66   40.06   39.09   38.47
   38.01   37.86   33.66   38.57   38.74   34.22   35.03   34.91   34.86   34.44
   34.86   36.36   35.96   37.06   37.16   38.16   38.46   38.66   38.16   35.86
   35.56   37.66   38.16   39.56   39.46   36.56   36.66   37.66   40.26   40.46
   41.26   44.56
Pier Skew, UpSta & Num, DnSta & Num=  ,4973.6, 2 ,4973.6, 2 , 0 , 0 , 0 ,,
       2       2
   29.81   39.63
       2       2
   29.77   39.59
Pier Skew, UpSta & Num, DnSta & Num=  ,4989.4, 2 ,4989.4, 2 , 0 , 0 , 0 ,,
       2       2
   23.53   39.64
       2       2
   23.49    39.6
Pier Skew, UpSta & Num, DnSta & Num=  ,5008.5, 2 ,5008.5, 2 , 0 , 0 , 0 ,,
       2       2
    21.7   39.66
       2       2
   21.66   39.62
Pier Skew, UpSta & Num, DnSta & Num=  ,5043.4, 2 ,5043.4, 2 , 0 , 0 , 0 ,,
       2       2
   31.77   39.68
       2       2
   31.73   39.64
Pier Skew, UpSta & Num, DnSta & Num=  ,5062.4, 2 ,5062.4, 2 , 0 , 0 , 0 ,,
       2       2
   31.81    39.7
       2       2
   31.77   39.66
Pier Skew, UpSta & Num, DnSta & Num=  ,5080, 2 ,5080, 2 , 0 , 0 , 0 ,,
       2       2
    32.2   39.73
       2       2
   32.16   39.69
BR Coef= 1 , 1 , 0 ,1.25, 0 ,,,0.8,0,2,0,
WSPro=,,,, 1 ,,,, 0 ,,,, 0 ,,,,-1 ,-1 ,-1 , 0 , 0 , 0 , 0 , 0
BR U #Sta/Elev= 81
  4499.3    43.4    4543    38.3    4573    38.7    4738    39.8    4743    39.6
  4743.8    39.7  4757.4    39.7  4758.8    39.7  4768.8    40.1  4811.1   39.49
 4836.07   39.13  4870.6   38.71 4887.59   38.51  4916.8   38.05 4926.39    37.9
 4943.69   33.79  4943.8   33.76 4943.91   33.74 4944.05    33.7 4944.14   33.68
 4944.23   33.66  4945.2   33.43 4948.99   32.53 4950.38   35.13 4967.44   30.36
 4973.59   31.18 4989.43   25.27 4993.68   22.15 4995.67   21.94 5000.95   20.88
 5006.06   21.75 5006.32   21.96 5008.49   23.34 5016.97   25.88 5035.94   31.35
 5043.39   32.99  5055.6   31.97 5062.35   32.96  5064.7   32.93 5074.04   32.81
  5080.1   33.29 5092.92    33.7 5100.02   34.03 5106.42   34.25 5106.49   34.26
  5106.6   34.26 5113.99   34.52  5114.1   34.52 5114.21   34.53 5129.64   35.07
 5146.53   34.95  5155.2   34.94 5191.39    34.9  5202.1   34.81 5239.36   34.48
 5283.53    34.9    5300   35.87  5309.1    36.4  5324.1      36  5334.1    37.1
  5339.1    37.2  5339.3   37.22  5349.1    38.2  5354.1    38.5  5369.1    38.7
  5384.1    38.2  5388.8    37.5  5398.8    35.9  5413.8    35.6  5508.8    37.7
  5518.8    38.2  5638.8    39.6  5653.8    39.5  5683.8    36.6  5703.8    36.7
  5728.8    37.7  5773.8    40.3  5784.6   40.37  5803.8    40.5  5863.8    41.3
  5909.6    44.6
BR U #Mann= 5
  4499.3      .2  4509.6      .1 4948.99    .038 5092.92     .12  5784.6      .2
BR U Banks=4948.99,5092.92
BR D #Sta/Elev= 81
  4499.3   43.36    4543   38.26    4573   38.66    4738   39.76    4743   39.56
  4743.8   39.66  4757.4   39.66  4758.8   39.66  4768.8   40.06  4811.1   39.45
 4836.07   39.09  4870.6   38.67 4887.59   38.47  4916.8   38.01 4926.39   37.86
 4943.69   33.75  4943.8   33.72 4943.91    33.7 4944.05   33.66 4944.14   33.64
 4944.23   33.62  4945.2   33.39 4948.99   32.49 4950.38   35.09 4967.44   30.32
 4973.59   31.14 4989.43   25.23 4993.68   22.11 4995.67    21.9 5000.95   20.84
 5006.06   21.71 5006.32   21.92 5008.49    23.3 5016.97   25.84 5035.94   31.31
 5043.39   32.95  5055.6   31.93 5062.35   32.92  5064.7   32.89 5074.04   32.77
  5080.1   33.25 5092.92   33.66 5100.02   33.99 5106.42   34.21 5106.49   34.22
  5106.6   34.22 5113.99   34.48  5114.1   34.48 5114.21   34.49 5129.64   35.03
 5146.53   34.91  5155.2    34.9 5191.39   34.86  5202.1   34.77 5239.36   34.44
 5283.53   34.86    5300   35.83  5309.1   36.36  5324.1   35.96  5334.1   37.06
  5339.1   37.16  5339.3   37.18  5349.1   38.16  5354.1   38.46  5369.1   38.66
  5384.1   38.16  5388.8   37.46  5398.8   35.86  5413.8   35.56  5508.8   37.66
  5518.8   38.16  5638.8   39.56  5653.8   39.46  5683.8   36.56  5703.8   36.66
  5728.8   37.66  5773.8   40.26  5784.6   40.33  5803.8   40.46  5863.8   41.26
  5909.6   44.56
BR D #Mann= 5
  4499.3      .2  4509.6      .1 4948.99    .038 5092.92     .12  5784.6      .2
BR D Banks=4948.99,5092.92
BC Design=,, 0 ,, 0 ,,,,,,
BC HTab HWMax=44.58
BC Use User HTab Curves=0
BC User HTab FreeFlow(D)= 0

Type RM Length L Ch R = 1 ,55729.5 ,618.7,618.7,618.7
BEGIN DESCRIPTION:
Downstream Section of Bridge/Culvert/Weir
END DESCRIPTION:
XS GIS Cut Line= 6
      3145650.44       13856339.      3145543.92     13856235.92
      3145477.78     13855887.21      3145482.18     13855719.78
      3145493.22     13855189.75      3145480.05     13854980.65
#Sta/Elev= 30
  4499.3   43.33    4543   38.23  4768.8   40.03 4926.39   37.83 4948.99   32.46
 4950.38   35.06 4967.44   30.29 4973.59   31.11 4989.43    25.2 4993.68   22.08
 5000.95   20.81 5043.39   32.92  5055.6    31.9 5092.92   33.63 5129.64      35
 5283.53   34.83  5309.1   36.33  5324.1   35.93  5369.1   38.63  5384.1   38.13
  5398.8   35.83  5413.8   35.53  5518.8   38.13  5638.8   39.53  5653.8   39.43
  5683.8   36.53  5703.8   36.63  5784.6    40.3  5863.8   41.23  5909.6   44.53
#Mann= 5 , 1 , 0
  4499.3      .2       0  4509.6      .1       0 4948.99    .038       0
 5092.92     .12       0  5784.6      .2       0
#XS Ineff= 2 , 0
       0    4935    43.2    5115       0    43.2
Permanent Ineff=
       F       F
Bank Sta=4948.99,5092.92
XS Rating Curve= 0 ,0
Exp/Cntr=0.5,0.3

Type RM Length L Ch R = 1 ,55110.8 ,619.7,623.5,690.7
BEGIN DESCRIPTION:
Cross Section 55110.8
END DESCRIPTION:
XS GIS Cut Line= 6
      3146228.27     13857105.35      3145992.22     13856145.49
       3145983.8     13855556.07      3145965.83     13855250.57
      3145866.99      13854450.9      3145552.51     13853615.28
#Sta/Elev= 30
    3445   47.73    3535   47.07    3595   40.43    3655    38.2    3755   38.18
    3955   41.75    4205   38.12    4235   38.85    4295   43.47    4325   43.83
    4345   46.16  4500.9      47  4723.5   46.47  4783.5   44.36  4833.5   44.59
  4873.5   41.25  4923.5    42.2  4931.9   40.16  4985.4   25.65  4992.9   19.78
  5000.1   19.11  5007.4   20.26  5021.2   27.13  5059.3   38.88  5072.9   36.74
  5092.9   39.79  6694.7   41.02  6849.5   42.25  6954.7   41.04  7027.6   43.79
#Mann= 5 , 1 , 0
    3445     .99       0  4500.9     .14       0  4931.9     .05       0
  5059.3     .12       0  6849.5      .2       0
Bank Sta=4931.9,5059.3
XS Rating Curve= 0 ,0
Exp/Cntr=0.3,0.1

Type RM Length L Ch R = 1 ,54487.3 ,220.64,355.39,457.12
BEGIN DESCRIPTION:
Cross Section 54487.3
END DESCRIPTION:
XS GIS Cut Line= 5
      3146126.59     13856157.73       3146577.1     13855750.54
      3146603.09      13855213.4       3146386.5     13854728.25
      3145944.37     13854324.57
#Sta/Elev= 30
  4119.5   45.06  4149.5   44.66  4204.5    40.8  4269.5   38.41  4289.5   38.43
  4310.5   37.94  4349.5   39.38  4379.5   37.15  4704.5   37.43  4714.5   37.01
  4736.8   37.78  4781.8   37.42  4796.8   38.26  4931.9   38.44  4985.4   23.93
  4992.9   18.06  5000.1   17.39  5007.4   18.54  5009.4   20.05  5021.2   25.41
  5059.3   37.16  5131.2   36.42  5264.5   35.96  5567.7   37.79  5654.5   38.31
  5795.8   40.21  5830.8   40.36  5855.8   39.48  6335.5   41.56  6394.5    42.1
#Mann= 6 ,-1 , 0
  4119.5     .14       0  4310.5     .07       0  4931.9     .04       0
  5059.3     .07       0  5567.7     .12       0  6335.5      .2       0
#XS Ineff= 1 ,-1
    5200  6394.5   43.17
Permanent Ineff=
       F
Bank Sta=4931.9,5059.3
XS Rating Curve= 0 ,0
Exp/Cntr=0.5,0.3