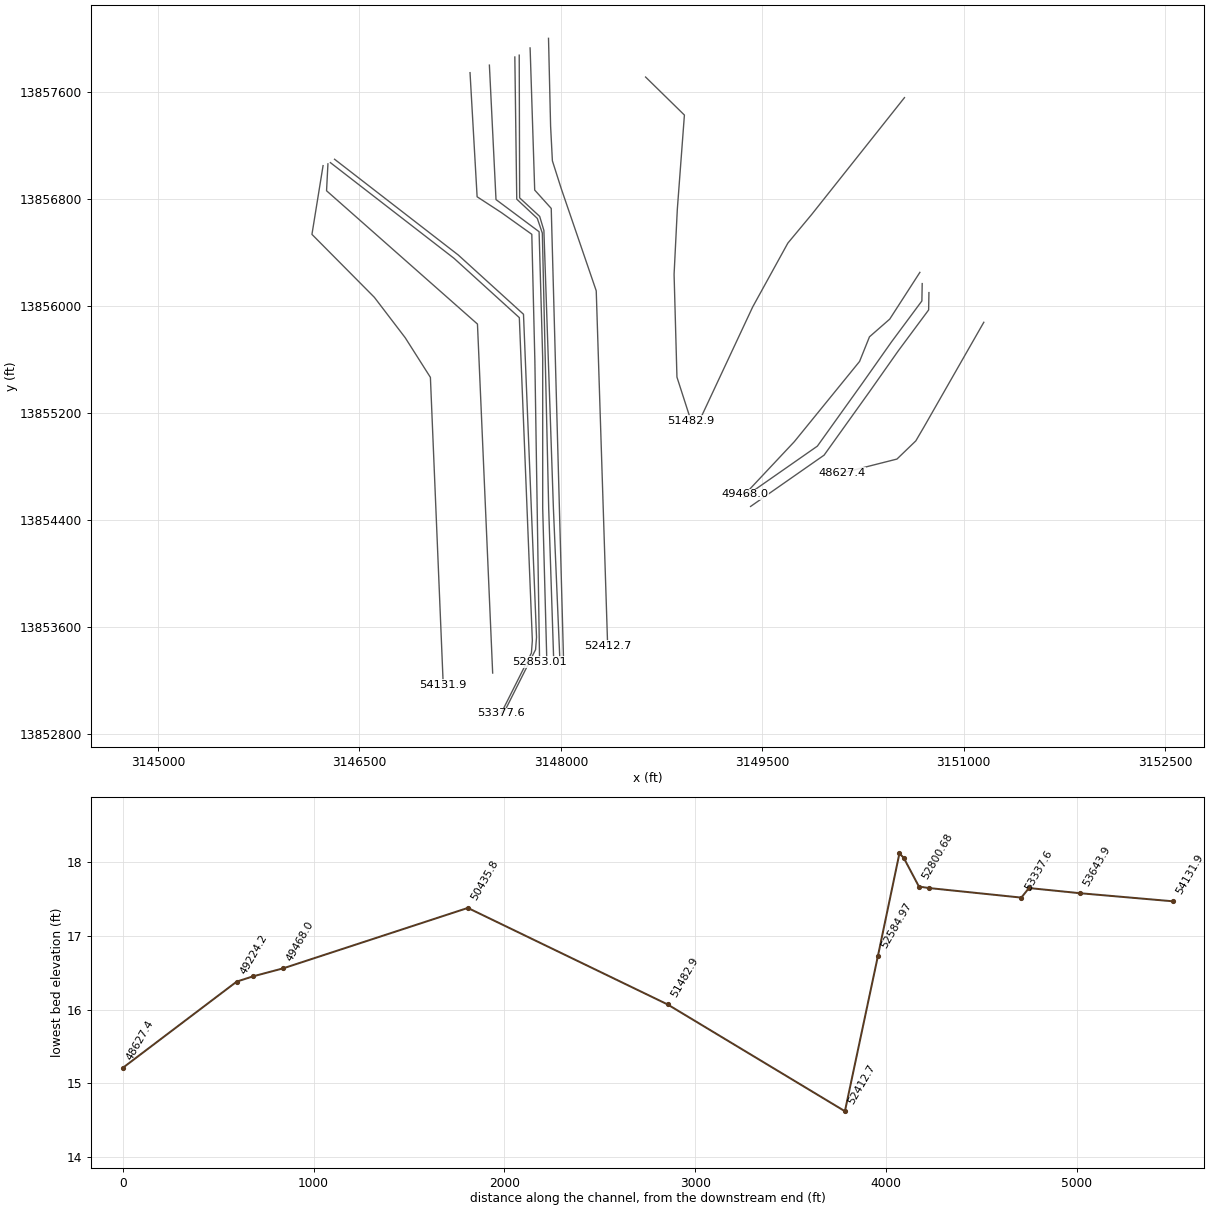
HEC-RAS study H100-00-00.prj: H100-00-00

--- H100-00-00.g01 (geometry) --- (continued)

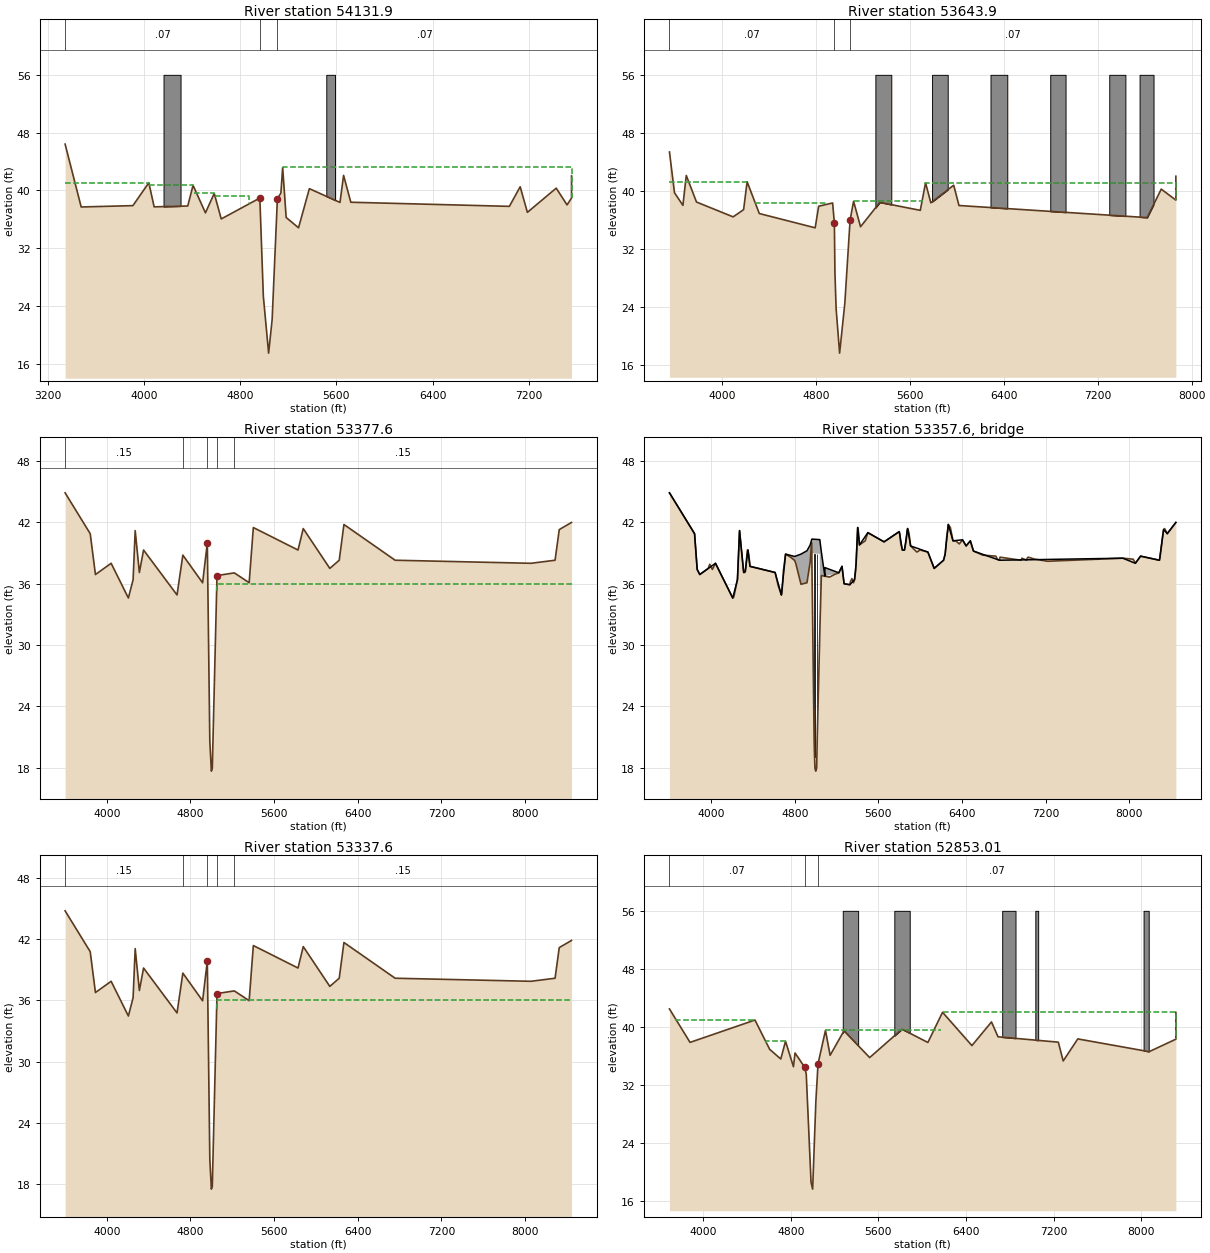
Type RM Length L Ch R = 1 ,54131.9 ,411.88,488.02,452.29
BEGIN DESCRIPTION:
54131.91
END DESCRIPTION:
XS GIS Cut Line= 6
      3146228.87      13857051.1     3146146.077     13856537.06
     3146611.296     13856065.79     3146840.884      13855763.7
      3147028.18     13855467.66     3147123.721     13853169.05
#Sta/Elev= 30
3343.201 46.40973476.861 37.7041 3907.14   37.89 4039.58   41.06 4083.72   37.72
 4363.32   37.84 4407.47    40.7 4510.48   36.89 4583.57   39.58 4641.94   36.05
 4963.01   38.94 4992.21   25.34    5036   17.47 5065.19    22.1 5108.98   38.84
 5138.17   39.63 5152.77   43.17 5181.96   36.25 5284.93   34.82 5374.86   40.24
 5629.68   38.33 5659.66   42.08 5719.61   38.36 7038.67   37.79  7128.6    40.5
 7188.56   36.96 7428.39   40.31 7518.33   37.997555.536   38.947555.536      42
#Mann= 3 , 0 , 0
3343.201     .07       0 4963.01     .04       0 5108.98     .07       0
#XS Ineff= 5 ,-1
  5152.6 7555.54   43.173343.201 4039.08   41.06 4041.57 4405.38   40.73
 4412.85 4584.79   39.62 4587.28 4873.83   39.29
Permanent Ineff=
       F       F       F       F       F
#Block Obstruct= 2 ,-1
 4161.73 4303.53      56 5515.68 5588.51      56
Bank Sta=4963.01,5108.98
XS Rating Curve= 0 ,0
Exp/Cntr=0.3,0.1

Type RM Length L Ch R = 1 ,53643.9 ,252.37,266.29,368.84
BEGIN DESCRIPTION:
53643.89
END DESCRIPTION:
XS GIS Cut Line= 4
      3146265.11     13857064.52      3146254.83     13856863.31
     3147378.605     13855866.42     3147491.845     13853256.22
#Sta/Elev= 30
3550.009 45.34993592.999 39.7167 3664.65 37.9815 3693.31 42.1099 3780.38   38.44
 4092.72   36.39 4181.96   37.39 4211.71   41.24 4315.82   36.85 4791.77   34.88
 4821.52   37.86 4940.51   38.31 4955.38   35.53 4960.02   28.78 4970.26   23.73
    5000   17.58 5044.62    24.5 5089.24   35.94 5118.99   38.54 5178.49   35.03
 5342.79   38.39 5687.52   37.29 5732.49   41.08 5777.46   38.33 5972.31   40.76
 6017.28   37.96 7621.07   36.29 7740.98   40.227865.501   38.717865.501      42
#Mann= 3 , 0 , 0
3550.009     .07       0 4955.38     .04       0 5089.24     .07       0
#XS Ineff= 4 ,-1
3550.009 4212.07   41.27 5730.91  7865.5   41.07 5119.06 5708.01   38.58
 4278.82 4893.95   38.25
Permanent Ineff=
       F       T       T       F
#Block Obstruct= 6 ,-1
 5304.72 5440.42      56 5787.87 5921.25      56 6285.78 6429.01      56
 6795.01  6925.6      56 7297.91 7435.57      56 7556.16  7675.2      56
Bank Sta=4955.38,5089.24
XS Rating Curve= 0 ,0
Exp/Cntr=0.3,0.1

Type RM Length L Ch R = 1 ,53377.6 ,40,40,40
BEGIN DESCRIPTION:
Upstream Section of Bridge/Culvert/Weir
END DESCRIPTION:
XS GIS Cut Line= 6
      3146283.47     13857073.66      3147204.39     13856357.76
       3147690.4     13855914.36      3147787.42     13853498.75
      3147780.36     13853406.06      3147554.57     13852954.48
#Sta/Elev= 30
  3602.5    44.9  3842.5    40.9  3892.5    36.9  4042.5      38  4207.5    34.6
  4252.5    36.4  4272.5    41.2  4312.5    37.1  4352.5    39.3  4672.5    34.9
    4728    38.8    4917   36.09    4962   39.99  4985.9   20.58  5000.9   17.65
  5009.7   17.96  5054.7    36.8  5220.3   37.06    5362    36.1    5402    41.5
  5829.2    39.3  5879.2    41.4  6133.1    37.5  6223.1    38.3  6268.1    41.8
  6757.7    38.3  8056.6      38  8286.6    38.3  8326.6    41.3  8443.8      42
#Mann= 5 ,-1 , 0
  3602.5     .15       0    4728     .07       0    4962     .04       0
  5054.7     .07       0  5220.3     .15       0
#XS Ineff= 2 , 0
       0    4966      36    5051       0      36
Permanent Ineff=
       F       F
Bank Sta=4962,5054.7
XS Rating Curve= 0 ,0
Exp/Cntr=0.5,0.3

Type RM Length L Ch R = 3 ,53357.6 ,,,
BEGIN DESCRIPTION:
EOUKON TANK FARM
Structure ID: H00-34
END DESCRIPTION:
Bridge Culvert--1,0,-1,-1, 0
Deck Dist Width WeirC Skew NumUp NumDn MinLoCord MaxHiCord MaxSubmerge Is_Ogee
10,20,2.6,0, 60, 60, , , 0.95, 0, 1,1,,
  3602.5  3842.5  3867.5  3892.5  4042.5  4207.5  4252.5  4272.5  4312.5  4327.5
  4352.5  4372.5  4612.5  4672.5  4712.5  4799.3  4859.9    4917  4947.6    4962
 4963.81  4963.9 5039.69  5039.8  5054.7  5087.9  5088.6  5221.9    5252    5272
    5327    5372    5387    5402  5419.2  5499.2  5654.2  5799.2  5829.2  5849.2
  5879.2  5908.1  6073.1  6133.1  6223.1  6238.1  6268.1  6313.1  6403.8  6438.8
  6478.8  6508.8  6757.7  7936.6  8056.6  8106.6  8286.6  8326.6  8361.6  8443.8
    44.9    40.9    37.4    36.9      38    34.6    36.4    41.2    37.1    37.2
    39.3    37.7    37.1    34.9    38.9   38.67    38.9   39.23   39.79   40.31
   40.37   40.37   40.32   40.32   39.11   36.75   37.58   37.07    37.7      36
    35.9    36.4      38    41.5    39.8      41    40.1    41.1    39.3    39.3
    41.4    39.7    39.1    37.5    38.3    38.9    41.8    40.2    40.3    39.7
    40.2    39.2    38.3    38.5      38    38.7    38.3    41.3    40.9      42
    44.9    40.9    37.4    36.9      38    34.6    36.4    41.2    37.1    37.2
    39.3    37.7    37.1    34.9    38.9   38.28   35.95   36.09   38.13   39.99
   38.52   38.97   38.92   31.15    36.8   36.74   36.74   37.07    37.7      36
    35.9    36.4      38    41.5    39.8      41    40.1    41.1    39.3    39.3
    41.4    39.7    39.1    37.5    38.3    38.9    41.8    40.2    40.3    39.7
    40.2    39.2    38.3    38.5      38    38.7    38.3    41.3    40.9      42
  3602.5  3842.5  3867.5  3892.5  4042.5  4207.5  4252.5  4272.5  4312.5  4327.5
  4352.5  4372.5  4612.5  4672.5  4712.5  4799.3  4859.9    4917  4947.6    4962
 4963.81  4963.9 5039.69  5039.8  5054.7  5087.9  5088.6  5221.9    5252    5272
    5327    5372    5387    5402  5419.2  5499.2  5654.2  5799.2  5829.2  5849.2
  5879.2  5908.1  6073.1  6133.1  6223.1  6238.1  6268.1  6313.1  6403.8  6438.8
  6478.8  6508.8  6757.7  7936.6  8056.6  8106.6  8286.6  8326.6  8361.6  8443.8
    44.9    40.9    37.4    36.9      38    34.6    36.4    41.2    37.1    37.2
    39.3    37.7    37.1    34.9    38.9   38.67    38.9   39.23   39.79   40.31
   40.37   40.37   40.32   40.32   39.11   36.75   37.58   37.07    37.7      36
    35.9    36.4      38    41.5    39.8      41    40.1    41.1    39.3    39.3
    41.4    39.7    39.1    37.5    38.3    38.9    41.8    40.2    40.3    39.7
    40.2    39.2    38.3    38.5      38    38.7    38.3    41.3    40.9      42
    44.8    40.8    37.3    36.8    37.9    34.5    36.3    41.1      37    37.1
    39.2    37.6      37    34.8    38.8   38.18   35.85   35.99   38.03   39.89
   38.42   38.87   38.82   31.05    36.7   36.64   36.64   36.97    37.6    35.9
    35.8    36.3    37.9    41.4    39.7    40.9      40      41    39.2    39.2
    41.3    39.6      39    37.4    38.2    38.8    41.7    40.1    40.2    39.6
    40.1    39.1    38.2    38.4    37.9    38.6    38.2    41.2    40.8    41.9
Pier Skew, UpSta & Num, DnSta & Num=  ,4989.5, 2 ,4989.5, 2 , 0 , 0 , 0 ,,
     1.4     1.4
   17.88   39.95
     1.4     1.4
   17.78   39.85
Pier Skew, UpSta & Num, DnSta & Num=  ,5015, 2 ,5015, 2 , 0 , 0 , 0 ,,
     1.4     1.4
   19.61   39.94
     1.4     1.4
   19.51   39.84
BR Coef= 1 , 1 , 0 ,1.25, 0 ,,,0.8,0,2,0,
WSPro=,,,, 1 ,,,, 0 ,,,, 0 ,,,,-1 ,-1 ,-1 , 0 , 0 , 0 , 0 , 0
BR U #Sta/Elev= 140
  3602.5    44.9  3842.5    40.9  3867.5    37.4  3892.5    36.9  3972.5    37.5
  3987.5    37.9  4012.5    37.4  4042.5      38  4207.5    34.6  4217.5    34.7
  4252.5    36.4  4267.5    40.1  4272.5    41.2  4307.5    37.5  4312.5    37.1
  4322.5    37.1  4327.5    37.2  4347.5    39.3  4352.5    39.3  4362.5    38.7
  4372.5    37.7  4612.5    37.1  4642.5    35.8  4672.5    34.9  4677.5    35.1
  4692.5    37.3  4712.5    38.9    4728    38.8  4752.7   38.65  4757.1   38.62
  4799.3   38.28  4805.4   38.11  4810.6   37.97  4859.9   35.95    4861   35.95
    4913   36.08    4917   36.09 4939.79   37.61  4939.9   37.62 4940.01   37.62
  4940.1   37.63  4947.6   38.13    4962   39.99  4963.7   38.61 4963.81   38.52
  4963.9   38.45    4964   38.37  4985.9   20.58  4989.5   19.08  4993.6   17.93
  5000.9   17.65  5009.7   17.96  5014.1   20.56    5015    20.8  5024.2   24.69
  5039.6   31.06 5039.69    31.1  5039.8   31.15  5039.9   31.19  5040.3   31.35
  5042.9   32.43  5054.7    36.8 5064.59   36.78  5064.7   36.78 5064.81   36.78
  5087.9   36.74  5088.6   36.74  5133.4   36.65  5135.5   36.66  5173.4   36.88
  5180.3   36.91  5218.4   37.06  5220.3   37.06  5221.9   37.07    5252    37.7
    5272      36    5327    35.9    5332    36.2    5347    36.5    5362    36.1
    5372    36.4    5382    37.2    5387      38    5402    41.5    5407    41.3
  5419.2    39.8  5474.2    40.2  5499.2      41  5654.2    40.1  5799.2    41.1
  5804.2    40.9  5814.2    39.9  5829.2    39.3  5849.2    39.3  5864.2    40.1
  5874.2    41.2  5879.2    41.4  5883.1    41.3  5893.1    40.9  5908.1    39.7
  5968.1    39.1  5998.1    39.3  6073.1    39.1  6133.1    37.5  6223.1    38.3
  6238.1    38.9  6253.1    40.6  6263.1    41.3  6268.1    41.8  6288.1    41.5
  6313.1    40.2  6338.8    40.2  6373.8    39.9  6403.8    40.3  6438.8    39.7
  6478.8    40.2  6508.8    39.2  6597.7    38.8  6722.7    38.7  6737.7    38.4
  6757.7    38.3  6762.7    38.6  6962.7    38.3  6972.7    38.5  7017.7    38.3
  7022.7    38.5  7032.7    38.6  7097.7    38.4  7217.7    38.2  7936.6    38.5
  8036.6    38.4  8056.6      38  8106.6    38.7  8286.6    38.3  8291.6    38.5
  8321.6      41  8326.6    41.3  8336.6    41.4  8361.6    40.9  8443.8      42
BR U #Mann= 5
  3602.5     .15    4728     .07    4962     .04  5054.7     .07  5220.3     .15
BR U Banks=4962,5054.7
BR D #Sta/Elev= 140
  3602.5    44.8  3842.5    40.8  3867.5    37.3  3892.5    36.8  3972.5    37.4
  3987.5    37.8  4012.5    37.3  4042.5    37.9  4207.5    34.5  4217.5    34.6
  4252.5    36.3  4267.5      40  4272.5    41.1  4307.5    37.4  4312.5      37
  4322.5      37  4327.5    37.1  4347.5    39.2  4352.5    39.2  4362.5    38.6
  4372.5    37.6  4612.5      37  4642.5    35.7  4672.5    34.8  4677.5      35
  4692.5    37.2  4712.5    38.8    4728    38.7  4752.7   38.55  4757.1   38.52
  4799.3   38.18  4805.4   38.01  4810.6   37.87  4859.9   35.85    4861   35.85
    4913   35.98    4917   35.99 4939.79   37.51  4939.9   37.52 4940.01   37.52
  4940.1   37.53  4947.6   38.03    4962   39.89  4963.7   38.51 4963.81   38.42
  4963.9   38.35    4964   38.27  4985.9   20.48  4989.5   18.98  4993.6   17.83
  5000.9   17.55  5009.7   17.86  5014.1   20.46    5015    20.7  5024.2   24.59
  5039.6   30.96 5039.69      31  5039.8   31.05  5039.9   31.09  5040.3   31.25
  5042.9   32.33  5054.7    36.7 5064.59   36.68  5064.7   36.68 5064.81   36.68
  5087.9   36.64  5088.6   36.64  5133.4   36.55  5135.5   36.56  5173.4   36.78
  5180.3   36.81  5218.4   36.96  5220.3   36.96  5221.9   36.97    5252    37.6
    5272    35.9    5327    35.8    5332    36.1    5347    36.4    5362      36
    5372    36.3    5382    37.1    5387    37.9    5402    41.4    5407    41.2
  5419.2    39.7  5474.2    40.1  5499.2    40.9  5654.2      40  5799.2      41
  5804.2    40.8  5814.2    39.8  5829.2    39.2  5849.2    39.2  5864.2      40
  5874.2    41.1  5879.2    41.3  5883.1    41.2  5893.1    40.8  5908.1    39.6
  5968.1      39  5998.1    39.2  6073.1      39  6133.1    37.4  6223.1    38.2
  6238.1    38.8  6253.1    40.5  6263.1    41.2  6268.1    41.7  6288.1    41.4
  6313.1    40.1  6338.8    40.1  6373.8    39.8  6403.8    40.2  6438.8    39.6
  6478.8    40.1  6508.8    39.1  6597.7    38.7  6722.7    38.6  6737.7    38.3
  6757.7    38.2  6762.7    38.5  6962.7    38.2  6972.7    38.4  7017.7    38.2
  7022.7    38.4  7032.7    38.5  7097.7    38.3  7217.7    38.1  7936.6    38.4
  8036.6    38.3  8056.6    37.9  8106.6    38.6  8286.6    38.2  8291.6    38.4
  8321.6    40.9  8326.6    41.2  8336.6    41.3  8361.6    40.8  8443.8    41.9
BR D #Mann= 5
  3602.5     .15    4728     .07    4962     .04  5054.7     .07  5220.3     .15
BR D Banks=4962,5054.7
BC Design=,, 0 ,, 0 ,,,,,,
BC HTab HWMax=44.9
BC Use User HTab Curves=0
BC User HTab FreeFlow(D)= 0

Type RM Length L Ch R = 1 ,53337.6 ,542.62,484.59,64.34
BEGIN DESCRIPTION:
Downstream Section of Bridge/Culvert/Weir
END DESCRIPTION:
XS GIS Cut Line= 6
      3146314.48     13857098.93      3147235.41     13856383.02
      3147721.42     13855939.62      3147818.44     13853524.01
      3147811.38     13853431.32      3147585.58     13852979.75
#Sta/Elev= 30
  3602.5   44.77  3842.5   40.77  3892.5   36.77  4042.5   37.87  4207.5   34.47
  4252.5   36.27  4272.5   41.07  4312.5   36.97  4352.5   39.17  4672.5   34.77
    4728   38.67    4917   35.96    4962   39.86  4985.9   20.45  5000.9   17.52
  5009.7   17.83  5054.7   36.67  5220.3   36.93    5362   35.97    5402   41.37
  5829.2   39.17  5879.2   41.27  6133.1   37.37  6223.1   38.17  6268.1   41.67
  6757.7   38.17  8056.6   37.87  8286.6   38.17  8326.6   41.17  8443.8   41.87
#Mann= 5 ,-1 , 0
  3602.5     .15       0    4728     .07       0    4962     .04       0
  5054.7     .07       0  5220.3     .15       0
#XS Ineff= 2 , 0
       0    4966      36    5051       0      36
Permanent Ineff=
       F       F
Bank Sta=4962,5054.7
XS Rating Curve= 0 ,0
Exp/Cntr=0.5,0.3

Type RM Length L Ch R = 1 ,52853.01,168.23,52.33,80.12
XS GIS Cut Line= 6
       3147323.3   13857746.6947    3147376.0506   13856818.3961
    3147557.3768   13856699.6265    3147783.3257   13856537.6254
    3147806.1972   13855588.0502    3147841.3413     13853338.98
#Sta/Elev= 30
 3692.47   42.48 3880.51   37.87 4473.29   40.95 4607.38   36.92 4708.98   35.58
 4752.33   38.03 4824.59   34.52 4839.04   36.41 4926.83   34.46 4941.47   33.52
 4985.36   18.59    5000   17.65 5029.26   29.74 5049.19   34.93 5117.06   39.52
 5159.37   36.09  5286.3   39.47 5520.57   35.78 5815.89   39.69 6052.15   37.86
  6186.1   42.02 6454.27   37.43 6633.05   40.69 6692.64   38.64 7243.31    37.9
 7287.72   35.31 7420.97   38.35 8072.37   36.598316.517 38.31158316.517      42
#Mann= 3 , 0 , 0
 3692.47     .07       0 4926.83     .04       0 5049.19     .07       0
#XS Ineff= 4 ,-1
  6185.78316.517   42.02 3744.98 4474.91   40.95 5117.13 6169.99   39.52
 4576.93  4752.4   38.03
Permanent Ineff=
       T       F       T       F
#Block Obstruct= 6 ,-1
 5274.79  5415.4      56 5745.61 5886.34      56  6730.6 6852.41      56
 7033.18 7059.39      56 8021.58 8068.69      56
Bank Sta=4926.83,5049.19
XS Rating Curve= 0 ,0
Exp/Cntr=0.3,0.1

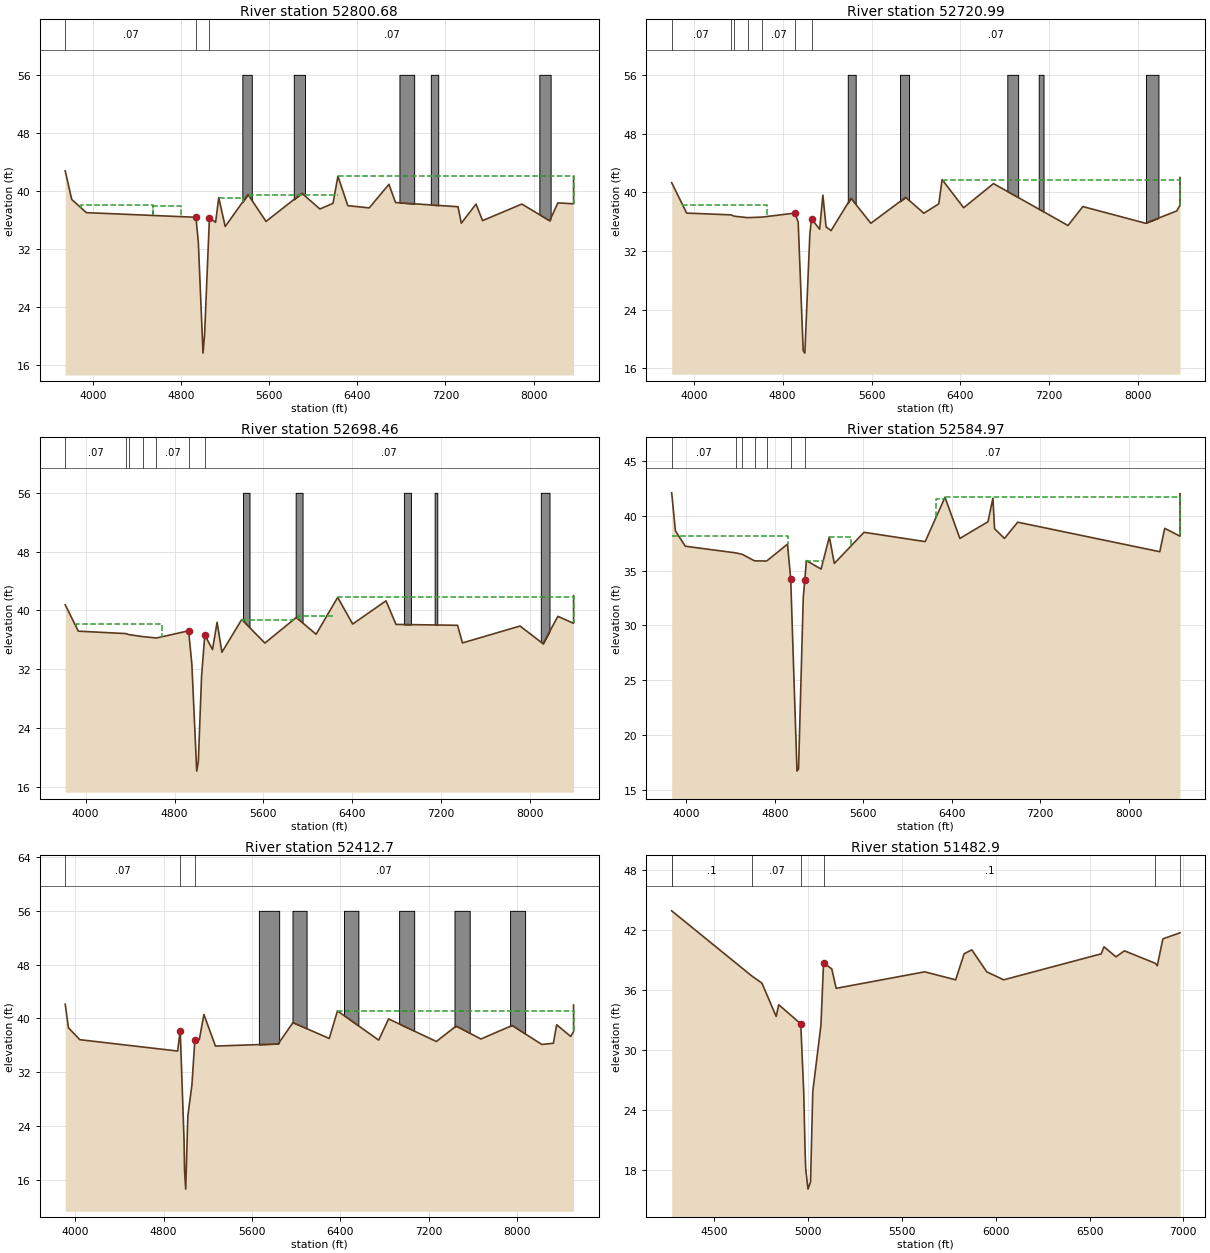
Type RM Length L Ch R = 1 ,52800.68,188.07,79.69,50.82
XS GIS Cut Line= 6
      3147467.47   13857802.9552    3147516.7019   13856797.2984
    3147837.6074   13856556.9648    3147864.4518   13855609.4103
    3147864.4518   13854488.9797    3147895.0708   13853351.7028
#Sta/Elev= 30
 3749.07   42.77  3808.3   38.84 3941.56   37.02  4935.3   36.38  4957.2   33.02
    5000   17.67 5014.26   20.21 5058.23   36.32 5114.11   35.68 5142.64   39.08
 5201.36   35.11 5408.78   39.52 5571.73   35.81 5897.64   39.69 6060.59   37.52
 6179.73    38.3 6224.55   42.03 6314.18   37.98 6508.39   37.67 6687.65   40.92
 6747.41   38.41 7314.58   37.83 7344.29   35.56 7477.98    38.2  7537.4   35.92
 7893.91    38.2 8146.44    35.9 8220.71   38.368362.961 38.24028362.961      42
#Mann= 3 , 0 , 0
 3749.07     .07       0  4935.3     .04       0 5058.23     .07       0
#XS Ineff= 5 ,-1
 3894.96 4548.64   38.03 4548.64 4799.35   37.95 5142.63 5362.91   39.08
  5422.6 6224.55    39.5 6224.558362.961   42.03
Permanent Ineff=
       F       F       T       T       T
#Block Obstruct= 5 ,-1
 5356.89 5442.46      56 5823.68 5925.22      56  6782.8 6916.55      56
 7067.65 7134.77      56 8052.68 8155.11      56
Bank Sta=4935.3,5058.23
XS Rating Curve= 0 ,0
Exp/Cntr=0.3,0.1

Type RM Length L Ch R = 1 ,52720.99,26.26,22.53,43.39
XS GIS Cut Line= 6
      3147656.94   13857863.7635    3147671.2482   13856800.3987
    3147824.2349   13856656.6282    3147861.7135   13856546.6498
    3147909.1137   13854488.9797    3147945.9707   13853363.7556
#Sta/Elev= 30
 3801.58    41.3 3936.38   37.15 4334.15   36.91 4364.38   36.73 4485.22   36.53
 4613.04    36.6 4910.03   37.15 4940.02   35.94 4985.01   18.39    5000   18.06
 5044.99   34.28 5059.99   36.37 5133.08   34.95 5162.12   39.59 5191.17   35.27
 5235.91   34.76 5414.87   39.18 5593.83   35.76 5907.01    39.3 6071.06   37.13
 6205.29   38.41 6235.12   41.72 6429.03   37.88 6697.52   41.17 7368.04   35.46
  7501.5   38.04 8064.99   35.778346.271 37.44148375.775 38.22318375.775      42
#Mann= 7 ,-1 , 0
 3801.58     .07       0 4334.15    .015       0 4364.38     .07       0
 4485.22    .015       0 4613.04     .07       0 4910.03     .04       0
 5059.99     .07       0
#XS Ineff= 3 ,-1
 6249.348375.775   41.65 5162.12 6245.82   39.59 3891.83 4661.58   38.19
Permanent Ineff=
       T       T       F
#Block Obstruct= 5 ,-1
 5386.14 5457.43      56 5856.13 5937.81      56 6821.89 6919.26      56
 7104.43 7147.79      56 8069.78 8181.93      56
Bank Sta=4910.03,5059.99
XS Rating Curve= 0 ,0
Exp/Cntr=0.3,0.1

Type RM Length L Ch R = 1 ,52698.46,110.19,112.56,71.97
XS GIS Cut Line= 6
      3147689.68    13857877.457    3147692.7524   13856810.2292
    3147842.0526   13856671.3739    3147873.3872   13856566.3107
    3147944.0665   13854490.9215    3147991.4807    13853374.532
#Sta/Elev= 30
 3816.25   40.76 3934.41   37.17 4362.26   36.84 4389.71    36.7 4513.25   36.43
 4637.25   36.24 4927.18   37.22 4956.31   32.66    5000   18.12 5014.56   19.43
 5043.69   31.06 5072.82   36.64  5142.2   34.67 5183.31   38.38 5226.76    34.3
 5405.23   38.76 5613.44   35.55 5896.01   39.03 6074.48   36.75 6268.82   41.77
  6403.8   38.14 6703.74    41.3 6793.73   38.09 7347.67   37.97 7392.08   35.57
 7910.27   37.87 8117.55   35.46  8250.8   39.198391.686 38.24038391.686      42
#Mann= 7 ,-1 , 0
 3816.25     .07       0 4362.26    .015       0 4389.71     .07       0
 4513.25    .015       0 4637.25     .07       0 4927.18     .04       0
 5072.82     .07       0
#XS Ineff= 5 ,-1
  6274.48391.686   41.79 5913.17 6243.56   39.17 5402.15 5877.92   38.74
 5183.31 5393.34   38.38 3912.86 4689.25   38.19
Permanent Ineff=
       T       T       T       T       F
#Block Obstruct= 5 ,-1
 5416.97 5475.13      56 5890.64 5952.67      56    6865 6928.15      56
 7141.59 7165.32      56 8097.19 8175.49      56
Bank Sta=4927.18,5072.82
XS Rating Curve= 0 ,0
Exp/Cntr=0.3,0.1

Type RM Length L Ch R = 1 ,52584.97,143.2,173.21,645.41
XS GIS Cut Line= 6
      3147770.47     13857931.54     3147771.366     13857911.82
      3147804.88     13856868.53     3147928.029     13856731.18
     3148016.031     13853488.73     3148018.954     13853381.04
#Sta/Elev= 30
 3866.22 42.0852 3900.13   38.62  3989.6   37.22 4448.24   36.61 4505.07   36.48
 4615.89   35.89 4725.39   35.87 4914.13   37.41 4943.21   34.26    5000   16.73
 5014.19   16.93 5056.76   32.52 5070.95   34.16 5085.14   35.91 5218.15   35.14
 5292.89   38.07 5337.74   35.65 5606.79   38.49 6159.85   37.64 6339.22   41.68
 6473.75   37.93 6727.86   39.45  6772.7   41.59 6787.65   38.82 6877.33   37.93
 6996.91   39.41 8282.41   36.72 8327.25   38.858465.419 38.13768465.419      42
#Mann= 7 ,-1 , 0
 3866.22     .07       0 4448.24    .015       0 4505.07     .07       0
 4615.89    .015       0 4725.39     .07       0 4943.21     .04       0
 5070.95     .07       0
#XS Ineff= 6 ,-1
 6339.12 8465.42   41.72 6261.09 6336.13   41.56 5605.75 6206.06   38.47
 5292.25 5489.02   38.07 3866.22 4914.19   38.19 5083.81 5242.22   35.89
Permanent Ineff=
       T       T       T       T       F       T
Bank Sta=4943.21,5070.95
XS Rating Curve= 0 ,0
Exp/Cntr=0.3,0.1

Type RM Length L Ch R = 1 ,52412.7 ,994.74,929.8,747.08
XS GIS Cut Line= 6
      3147907.75     13858003.35     3147923.292     13857346.92
      3147936.64     13857087.27      3148002.24     13856880.38
     3148263.129     13856114.82     3148348.171     13853458.99
#Sta/Elev= 30
3910.125 42.10963939.767 38.6051 4042.46   36.84 4927.65   35.15 4950.94   38.19
  4985.7   21.86  4990.1   17.39  5000.5   14.62  5019.8   25.49 5056.78    30.1
 5083.51    36.8  5123.6   36.85 5165.27   40.59  5269.8   35.89 5837.27   36.21
 5971.51   39.38  6299.6   37.02 6374.17   41.12    6747   36.78 6836.48   39.93
 7268.97   36.57 7447.93   38.87 7671.62   36.94 7954.93   38.95 8223.33   36.13
 8327.71   36.31 8357.53   39.068484.139 37.32998510.163 38.00168510.163      42
#Mann= 3 , 0 , 0
3910.125     .07       0 4950.94     .04       0 5083.51     .07       0
#XS Ineff= 3 ,-1
 6374.17 8510.16   41.11 5165.27 6374.17   40.593910.125 4950.94   38.19
Permanent Ineff=
       T       T       F
#Block Obstruct= 6 ,-1
 5662.86 5846.31      56 5966.85  6094.6      56 6432.85 6563.06      56
 6931.86 7068.09      56 7432.97 7570.58      56 7936.07 8072.13      56
Bank Sta=4950.94,5083.51
XS Rating Curve= 0 ,0
Exp/Cntr=0.3,0.1

Type RM Length L Ch R = 1 ,51482.9 ,1210.5,1047.1,733.6
BEGIN DESCRIPTION:
Cross Section 51482.9
END DESCRIPTION:
XS GIS Cut Line= 6
      3148630.66     13857713.92      3148919.76     13857429.49
      3148866.91     13856723.23      3148842.89     13856237.98
      3148864.22     13855469.54       3148968.4     13855144.62
#Sta/Elev= 30
  4272.5    43.9    4702   37.35  4753.7   36.67  4829.5   33.34  4843.2   34.51
  4960.6    32.6  4976.5   25.74  4983.9   19.69  4987.1   18.07  4999.2   16.07
  5012.7   16.79  5024.7   25.83  5068.2   32.48  5082.1   38.69    5126   38.09
  5149.4   36.15  5621.3    37.8  5786.3      37  5831.3    39.6  5872.1      40
  5952.1    37.8  6042.1      37  6562.1    39.6  6577.1    40.3  6640.9    39.3
  6685.9    39.9  6850.8   38.65  6860.9    38.4  6890.9    41.1  6982.1    41.7
#Mann= 7 , 1 , 0
  4272.5      .2       0  4272.5      .1       0    4702     .07       0
  4960.6     .04       0  5082.1      .1       0  6850.8     .07       0
  6982.1      .2       0
Bank Sta=4960.6,5082.1
XS Rating Curve= 0 ,0
Exp/Cntr=0.3,0.1

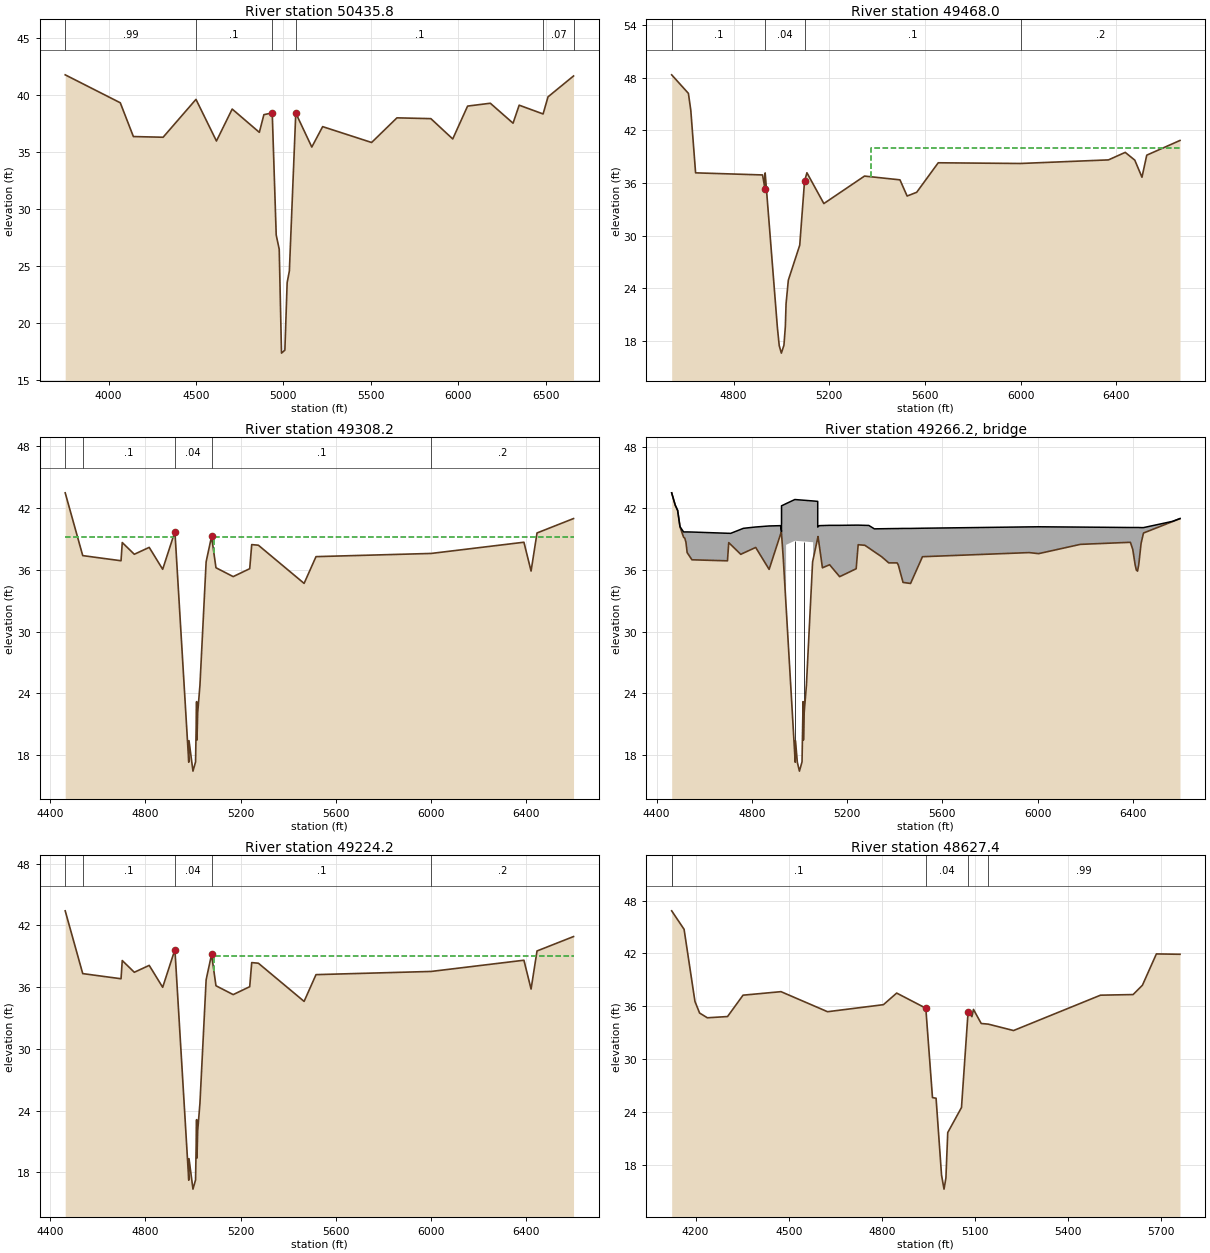
Type RM Length L Ch R = 1 ,50435.8 ,1001.1,967.8,914.1
BEGIN DESCRIPTION:
Cross Section 50435.8
END DESCRIPTION:
XS GIS Cut Line= 5
      3150558.59     13857559.91      3149867.76     13856686.28
      3149690.01     13856471.67      3149428.45     13855994.72
       3149018.4     13855114.61
#Sta/Elev= 30
  3752.2   41.77  4067.2   39.32  4142.2   36.36  4312.2    36.3  4500.1   39.62
  4617.2   35.97  4707.2   38.77  4862.5   36.73  4888.6   38.28  4936.3   38.43
    4959   27.73  4976.2   26.49  4989.3   17.38  5008.6   17.64  5021.6   23.56
  5034.3   24.58  5070.9   38.42  5162.6   35.44  5224.6   37.23  5504.6   35.84
  5649.6      38  5843.6   37.93  5968.6   36.15  6053.6   39.03  6183.6   39.28
  6313.6   37.53  6348.6   39.11  6485.4   38.34  6513.6   39.84  6659.5   41.67
#Mann= 6 , 1 , 0
  3752.2     .99       0  4500.1      .1       0  4936.3     .04       0
  5070.9      .1       0  6485.4     .07       0  6659.5      .2       0
Bank Sta=4936.3,5070.9
XS Rating Curve= 0 ,0
Exp/Cntr=0.3,0.1

Type RM Length L Ch R = 1 ,49468.0 ,73.1,159.8,82.3
BEGIN DESCRIPTION:
Cross Section 49468.0
END DESCRIPTION:
XS GIS Cut Line= 6
      3150673.29     13856252.94      3150448.79     13855903.31
      3150297.89     13855770.82      3150224.29      13855586.8
      3149738.49     13854986.91      3149370.46     13854593.12
#Sta/Elev= 30
  4541.4   48.36  4611.4   46.24  4621.4    44.3  4641.4   37.16  4921.4   36.92
  4931.4   35.35  4932.3   37.15  4983.3   19.52  4991.1   17.42    5000   16.56
  5010.8   17.46  5016.7   19.58  5019.7   22.21  5029.2    24.9  5076.9    28.9
  5096.9   36.19  5106.9   37.17  5177.7   33.65  5347.7   36.79  5495.9   36.36
  5525.9   34.51  5565.9   34.94  5655.9   38.31  6000.2   38.23  6367.8   38.64
  6437.8    39.5  6477.8   38.61  6507.8   36.66  6527.8   39.18  6666.8   40.86
#Mann= 4 , 1 , 0
  4541.4      .1       0  4931.4     .04       0  5096.9      .1       0
  6000.2      .2       0
#XS Ineff= 2 , 0
       0                    5375       0      40
Permanent Ineff=
       F       F
Bank Sta=4931.4,5096.9
XS Rating Curve= 0 ,0
Exp/Cntr=0.5,0.3

Type RM Length L Ch R = 1 ,49308.2 ,84,84,84
BEGIN DESCRIPTION:
Upstream Section of Bridge/Culvert/Weir
END DESCRIPTION:
XS GIS Cut Line= 6
      3150690.63     13856169.01      3150688.25     13856039.29
      3150461.64     13855732.55      3150246.05     13855425.02
      3149909.86     13854953.21      3149362.33     13854569.53
#Sta/Elev= 30
  4463.4   43.49    4537   37.39  4697.8   36.89    4703   38.66  4753.6   37.52
  4816.2   38.19  4872.7   36.06  4924.1   39.72  4982.2   17.32  4983.3   19.41
  4999.9   16.45  5010.8   17.35  5015.2    23.2  5016.7   19.47  5019.7    22.1
  5029.2   24.79  5055.2   36.79    5078   39.25  5096.5   36.21  5168.8   35.35
  5238.2   36.12  5246.6   38.46  5274.6    38.4  5466.6   34.69  5516.6   37.29
  6000.2    37.6  6389.7   38.69  6419.7   35.89  6444.7   39.59    6598   40.99
#Mann= 5 , 1 , 0
  4463.4      .2       0    4537      .1       0  4924.1     .04       0
    5078      .1       0  6000.2      .2       0
#XS Ineff= 2 , 0
       0    4915    39.2    5088       0    39.2
Permanent Ineff=
       F       F
Bank Sta=4924.1,5078
XS Rating Curve= 0 ,0
Exp/Cntr=0.5,0.3

Type RM Length L Ch R = 3 ,49266.2 ,,,
BEGIN DESCRIPTION:
MCCARTY ROAD
Structure ID: H00-32
END DESCRIPTION:
Bridge Culvert--1,0,-1,-1, 0
Deck Dist Width WeirC Skew NumUp NumDn MinLoCord MaxHiCord MaxSubmerge Is_Ogee
10,64,2.6,0, 58, 58, , , 0.95, 0, 1,1,,
  4463.4  4478.4  4488.4  4498.4  4513.4  4518.4  4523.4  4528.4  4548.4  4697.8
    4703    4711  4753.6  4764.5  4816.2  4872.7  4920.4  4924.1 4924.59  4924.7
  4932.3 4943.71  4943.8  4980.6 5057.19  5057.3  5076.7 5076.81    5078    5083
  5096.5  5126.7  5168.8  5238.2  5246.6  5274.6  5291.3  5314.5    5345    5375
    5410    5415    5435  5466.6  5516.6  5964.7  6004.7  6179.7  6389.7  6399.7
  6409.7  6414.7  6419.7  6424.7  6434.7  6444.7    6567    6598
    43.5    42.3    41.8   40.21    39.7    39.7    39.7    39.7   39.69   39.57
   39.57   39.56   39.95   40.05   40.18   40.28   40.31   39.81   39.74   42.24
   42.32   42.45   42.45   42.85   42.71   42.71   42.67   40.17    40.2   40.31
   40.32   40.34   40.34   40.36   40.36   40.34   40.33      40   40.01   40.02
   40.03   40.03   40.04   40.04   40.06   40.19    40.2   40.17   40.13   40.13
   40.13   40.13   40.13   40.13   40.12   40.12   40.73      41
   43.49   42.29   41.79   40.19   39.19   39.09   38.69   37.69   36.99   36.89
   38.66   38.48   37.52   37.64   38.19   36.06   39.46   39.72   39.56   39.52
   37.04   32.53   38.44   38.84    38.7   37.02   39.11   39.12   39.25   38.43
   36.21   36.51   35.35   36.12   38.46    38.4   38.14   37.77   37.29   36.69
   36.69   36.49   34.79   34.69   37.29   37.69   37.59   38.49   38.69   37.99
   36.49   35.99   35.89   36.49   38.59   39.59   40.71   40.99
  4463.4  4478.4  4488.4  4498.4  4513.4  4518.4  4523.4  4528.4  4548.4  4697.8
    4703    4711  4753.6  4764.5  4816.2  4872.7  4920.4  4924.1 4924.59  4924.7
  4932.3 4943.71  4943.8  4980.6 5057.19  5057.3  5076.7 5076.81    5078    5083
  5096.5  5126.7  5168.8  5238.2  5246.6  5274.6  5291.3  5314.5    5345    5375
    5410    5415    5435  5466.6  5516.6  5964.7  6004.7  6179.7  6389.7  6399.7
  6409.7  6414.7  6419.7  6424.7  6434.7  6444.7    6567    6598
    43.5    42.3    41.8   40.21    39.7    39.7    39.7    39.7   39.69   39.57
   39.57   39.56   39.95   40.05   40.18   40.28   40.31   39.81   39.74   42.24
   42.32   42.45   42.45   42.85   42.71   42.71   42.67   40.17    40.2   40.31
   40.32   40.34   40.34   40.36   40.36   40.34   40.33      40   40.01   40.02
   40.03   40.03   40.04   40.04   40.06   40.19    40.2   40.17   40.13   40.13
   40.13   40.13   40.13   40.13   40.12   40.12   40.73      41
   43.44   42.24   41.74   40.14   39.14   39.04   38.64   37.64   36.94   36.84
   38.61   38.43   37.47   37.59   38.14   36.01   39.41   39.67   39.51   39.47
   36.99   32.48   38.39   38.79   38.65   36.97   39.06   39.07    39.2   38.38
   36.16   36.46    35.3   36.07   38.41   38.35   38.09   37.72   37.24   36.64
   36.64   36.44   34.74   34.64   37.24   37.64   37.54   38.44   38.64   37.94
   36.44   35.94   35.84   36.44   38.54   39.54   40.66   40.94
Pier Skew, UpSta & Num, DnSta & Num=  ,4982.2, 2 ,4982.2, 2 , 0 , 0 , 0 ,,
     1.4     1.4
    16.6   39.84
     1.4     1.4
   16.55   39.79
Pier Skew, UpSta & Num, DnSta & Num=  ,5019.6, 2 ,5019.6, 2 , 0 , 0 , 0 ,,
     1.4     1.4
    20.4   39.77
     1.4     1.4
   20.35   39.72
Abutment Skew #Up #Dn= , 2 , 2
  4943.6  4961.6
   38.44   25.46
  4943.6  4961.6
   38.39   25.41
Abutment Skew #Up #Dn= , 2 , 2
  5029.2 5057.39
   24.79    38.7
  5029.2 5057.39
   24.74   38.65
BR Coef= 1 , 1 , 0 ,1.25, 0 ,,,0.8,0,2,0,
WSPro=,,,, 1 ,,,, 0 ,,,, 0 ,,,,-1 ,-1 ,-1 , 0 , 0 , 0 , 0 , 0
BR U #Sta/Elev= 79
  4463.4   43.49  4478.4   42.29  4488.4   41.79    4497   40.41  4498.4   40.19
  4513.4   39.19  4518.4   39.09  4523.4   38.69  4528.4   37.69    4537   37.39
  4548.4   36.99  4697.8   36.89    4703   38.66    4711   38.48  4753.6   37.52
  4764.5   37.64  4816.2   38.19    4854   36.76  4872.7   36.06  4920.4   39.46
  4924.1   39.72 4924.59   39.56  4924.7   39.52 4924.81   39.49  4932.3   37.04
 4943.71   32.53  4943.8    32.5  4961.6   25.46  4980.6   17.95  4982.2   17.32
  4983.3   19.41  4991.1   17.31  4999.9   16.45  5010.8   17.35  5015.2    23.2
  5016.7   19.47  5019.7    22.1  5029.1   24.76  5029.2   24.79  5055.2   36.79
 5057.19      37  5057.3   37.02 5076.59    39.1  5076.7   39.11 5076.81   39.12
    5078   39.25    5083   38.43  5096.5   36.21  5126.7   36.51  5134.9   36.28
  5168.8   35.35  5196.2   35.65  5238.2   36.12  5246.6   38.46  5249.1   38.45
  5274.6    38.4  5291.3   38.14  5314.5   37.77    5345   37.29    5375   36.69
    5410   36.69    5415   36.49    5435   34.79  5466.6   34.69  5516.6   37.29
  5964.7   37.69  6000.2    37.6  6004.7   37.59  6179.7   38.49  6389.7   38.69
  6399.7   37.99  6409.7   36.49  6414.7   35.99  6419.7   35.89  6424.7   36.49
  6434.7   38.59  6444.7   39.59    6567   40.71    6598   40.99
BR U #Mann= 5
  4463.4      .2    4537      .1  4924.1     .04    5078      .1  6000.2      .2
BR U Banks=4924.1,5078
BR D #Sta/Elev= 79
  4463.4   43.44  4478.4   42.24  4488.4   41.74    4497   40.36  4498.4   40.14
  4513.4   39.14  4518.4   39.04  4523.4   38.64  4528.4   37.64    4537   37.34
  4548.4   36.94  4697.8   36.84    4703   38.61    4711   38.43  4753.6   37.47
  4764.5   37.59  4816.2   38.14    4854   36.71  4872.7   36.01  4920.4   39.41
  4924.1   39.67 4924.59   39.51  4924.7   39.47 4924.81   39.44  4932.3   36.99
 4943.71   32.48  4943.8   32.45  4961.6   25.41  4980.6    17.9  4982.2   17.27
  4983.3   19.36  4991.1   17.26  4999.9    16.4  5010.8    17.3  5015.2   23.15
  5016.7   19.42  5019.7   22.05  5029.1   24.71  5029.2   24.74  5055.2   36.74
 5057.19   36.95  5057.3   36.97 5076.59   39.05  5076.7   39.06 5076.81   39.07
    5078    39.2    5083   38.38  5096.5   36.16  5126.7   36.46  5134.9   36.23
  5168.8    35.3  5196.2    35.6  5238.2   36.07  5246.6   38.41  5249.1    38.4
  5274.6   38.35  5291.3   38.09  5314.5   37.72    5345   37.24    5375   36.64
    5410   36.64    5415   36.44    5435   34.74  5466.6   34.64  5516.6   37.24
  5964.7   37.64  6000.2   37.55  6004.7   37.54  6179.7   38.44  6389.7   38.64
  6399.7   37.94  6409.7   36.44  6414.7   35.94  6419.7   35.84  6424.7   36.44
  6434.7   38.54  6444.7   39.54    6567   40.66    6598   40.94
BR D #Mann= 5
  4463.4      .2    4537      .1  4924.1     .04    5078      .1  6000.2      .2
BR D Banks=4924.1,5078
BC Design=,, 0 ,, 0 ,,,,,,
BC HTab HWMax=43.49
BC Use User HTab Curves=0
BC User HTab FreeFlow(D)= 0

Type RM Length L Ch R = 1 ,49224.2 ,596.8,596.8,596.8
BEGIN DESCRIPTION:
Downstream Section of Bridge/Culvert/Weir
END DESCRIPTION:
XS GIS Cut Line= 6
       3150740.8     13856101.64      3150738.43     13855971.93
      3150511.82     13855665.19      3150296.23     13855357.66
      3149960.04     13854885.85      3149412.51     13854502.16
#Sta/Elev= 30
  4463.4   43.42    4537   37.32  4697.8   36.82    4703   38.59  4753.6   37.45
  4816.2   38.12  4872.7   35.99  4924.1   39.65  4982.2   17.25  4983.3   19.34
  4999.9   16.38  5010.8   17.28  5015.2   23.13  5016.7    19.4  5019.7   22.03
  5029.2   24.72  5055.2   36.72    5078   39.18  5096.5   36.14  5168.8   35.28
  5238.2   36.05  5246.6   38.39  5274.6   38.33  5466.6   34.62  5516.6   37.22
  6000.2   37.53  6389.7   38.62  6419.7   35.82  6444.7   39.52    6598   40.92
#Mann= 5 , 1 , 0
  4463.4      .2       0    4537      .1       0  4924.1     .04       0
    5078      .1       0  6000.2      .2       0
#XS Ineff= 2 , 0
       0    4915      39    5088       0      39
Permanent Ineff=
       F       F
Bank Sta=4924.1,5078
XS Rating Curve= 0 ,0
Exp/Cntr=0.5,0.3

Type RM Length L Ch R = 1 ,48627.4 ,624.2,904.6,1221.1
BEGIN DESCRIPTION:
Cross Section 48627.4
END DESCRIPTION:
XS GIS Cut Line= 6
      3151149.38     13855879.65      3150989.89     13855599.61
      3150705.49     13855099.66      3150642.93     13854992.41
      3150502.58     13854856.58      3150094.53     13854752.57
#Sta/Elev= 30
  4122.9   46.85  4162.9   44.75  4197.9   36.55  4212.9   35.23  4237.9   34.69
  4302.9   34.83  4352.9   37.26  4475.2   37.66  4625.2   35.38  4805.2   36.18
    4848    37.5  4941.8   35.78  4963.3   25.62  4974.9   25.54  4992.5   16.81
  5000.5   15.21  5006.6   16.48  5012.5   21.64  5056.8   24.49  5078.1   35.38
  5090.4   34.82  5095.4   35.64  5120.4   34.04  5142.9   33.97  5224.5   33.24
  5504.8   37.26  5609.8   37.33  5639.8   38.39  5684.8   41.95  5760.9   41.91
#Mann= 5 , 1 , 0
  4122.9      .2       0  4122.9      .1       0  4941.8     .04       0
  5078.1      .1       0  5142.9     .99       0
Bank Sta=4941.8,5078.1
XS Rating Curve= 0 ,0
Exp/Cntr=0.3,0.1