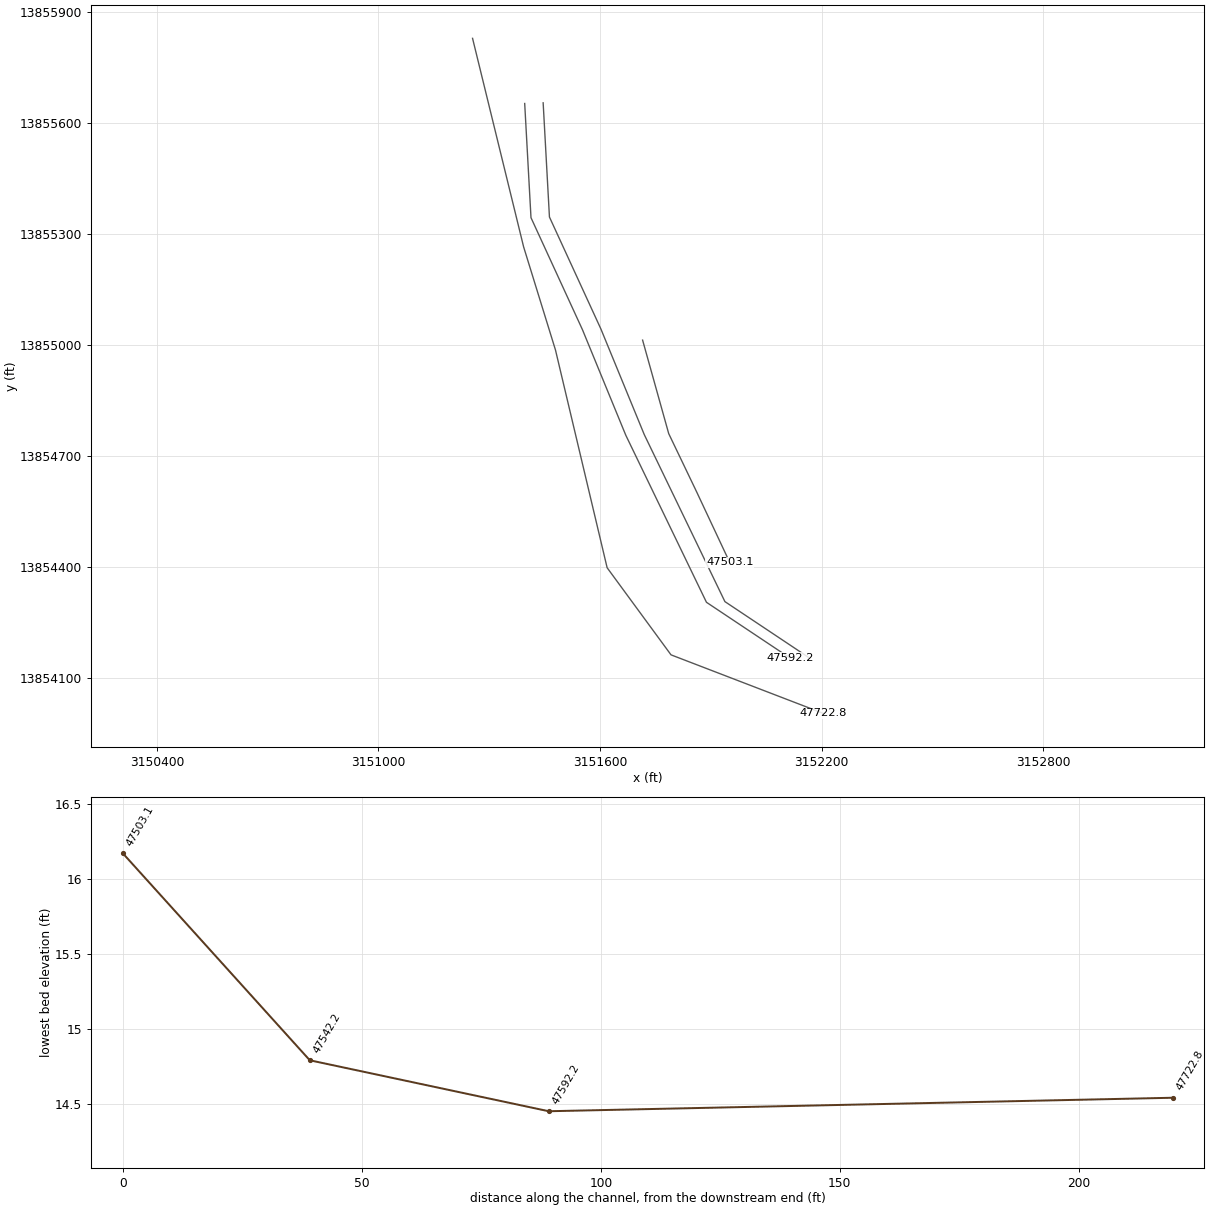
HEC-RAS study H100-00-00.prj: H100-00-00

--- H100-00-00.g01 (geometry) --- (continued)

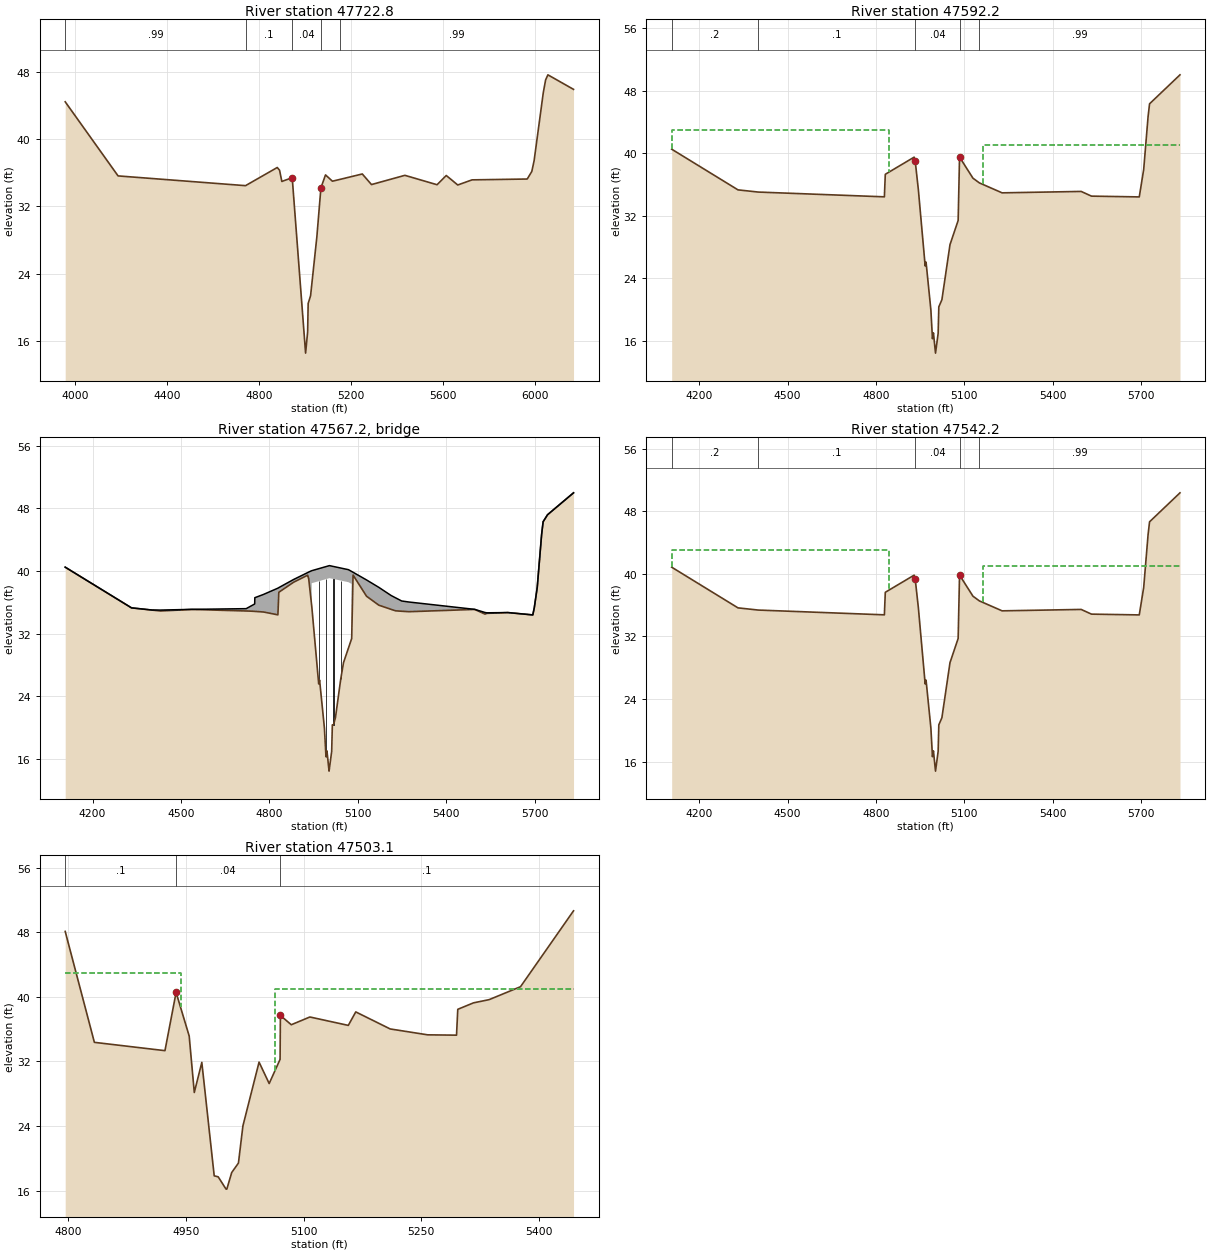
Type RM Length L Ch R = 1 ,47722.8 ,62.1,130.6,181.1
BEGIN DESCRIPTION:
Cross Section 47722.8
END DESCRIPTION:
XS GIS Cut Line= 6
      3151254.77      13855829.7        3151393.     13855265.85
      3151479.27     13854986.91      3151619.13     13854398.06
       3151792.1     13854162.52      3152204.29     13854004.27
#Sta/Elev= 30
  3956.4   44.45  4186.4   35.63  4740.9   34.47  4878.9   36.63  4888.9   36.31
  4898.9   34.97    4944   35.42  5002.2   14.54  5011.1   17.06  5013.4   20.45
  5023.9   21.37  5051.3    28.4  5068.9   34.21  5088.9   35.75  5118.9      35
  5151.1   35.21  5248.9   35.86  5288.9    34.6  5434.2    35.7  5574.2   34.58
  5614.2   35.68  5664.2   34.55  5726.4   35.16  5966.4   35.26  5986.4   36.16
  5996.4   37.44  6036.4   45.55  6046.4   47.05  6056.4   47.66  6167.9   45.93
#Mann= 5 , 1 , 0
  3956.4     .99       0  4740.9      .1       0    4944     .04       0
  5068.9      .1       0  5151.1     .99       0
Bank Sta=4944,5068.9
XS Rating Curve= 0 ,0
Exp/Cntr=0.5,0.3

Type RM Length L Ch R = 1 ,47592.2 ,50,50,50
BEGIN DESCRIPTION:
Upstream Section of Bridge/Culvert/Weir
END DESCRIPTION:
XS GIS Cut Line= 6
      3151395.94     13855653.51      3151412.97     13855344.74
      3151552.38     13855041.68      3151669.69     13854756.34
      3151888.04     13854304.68      3152114.15     13854154.06
#Sta/Elev= 30
    4107   40.51    4332   35.31  4400.9   35.03  4828.7   34.42  4831.8    37.3
  4929.7   39.49  4933.2   39.02    4944   35.33  4967.1   25.59  4970.1   26.08
  4986.5   19.95  4991.8   16.29  4995.1   17.04  5002.2   14.45  5011.1   16.97
  5013.4   20.36  5023.9   21.28  5051.3   28.31    5079    31.4  5083.7    39.5
  5129.3    36.8  5151.1    36.2  5228.1   34.93  5496.4   35.11  5531.4   34.51
  5693.5   34.41  5708.5   37.91  5723.5   44.71  5728.5   46.31  5831.7   50.01
#Mann= 5 , 1 , 0
    4107      .2       0  4400.9      .1       0  4933.2     .04       0
  5083.7      .1       0  5151.1     .99       0
#XS Ineff= 2 , 0
       0    4843      43    5163       0      41
Permanent Ineff=
       F       F
Bank Sta=4933.2,5083.7
XS Rating Curve= 0 ,0
Exp/Cntr=0.5,0.3

Type RM Length L Ch R = 3 ,47567.2 ,,,
BEGIN DESCRIPTION:
INTERSTATE 610-ACCESS ROAD South
Structure ID: H00-30
END DESCRIPTION:
Bridge Culvert--1,0,-1,-1, 0
Deck Dist Width WeirC Skew NumUp NumDn MinLoCord MaxHiCord MaxSubmerge Is_Ogee
10,30,2.6,0, 39, 39, , , 0.95, 0, 1,1,,
    4107    4332  4400.9  4430.3  4537.1  4720.9  4749.9  4750.3  4779.9  4828.7
  4831.8  4881.6  4929.7  4933.2 4943.31  4943.4  5003.4    5068 5078.59  5078.7
    5079  5083.7  5129.3  5171.2  5212.8  5228.1  5248.6  5273.1  5496.4  5531.4
  5537.6  5608.5  5693.5  5698.5  5708.5  5723.5  5728.5  5743.5  5831.7
    40.5    35.3   35.03   35.02   35.11    35.2    35.8    36.6   37.02   37.82
   37.89   38.92   39.81   39.88   40.05   40.05    40.7   40.18   39.96   39.96
   39.95   39.85   38.87   37.92   36.88   36.58   36.18   36.05   35.11   34.71
   34.67    34.7    34.4    35.3    37.9    44.7    46.3    47.2      50
    40.5    35.3   35.02    34.9    35.1    34.9   34.85   34.85   34.77   34.41
   37.29   38.57   39.48   39.01   35.56   38.45    39.1   38.58   38.36   31.36
   31.39   39.49   36.79   35.64   35.11   34.92   34.87   34.81    35.1    34.5
    34.6    34.7    34.4    35.3    37.9    44.7    46.3    47.2      50
    4107    4332  4400.9  4430.3  4537.1  4720.9  4749.9  4750.3  4779.9  4828.7
  4831.8  4881.6  4929.7  4933.2 4943.31  4943.4  5003.4    5068 5078.59  5078.7
    5079  5083.7  5129.3  5171.2  5212.8  5228.1  5248.6  5273.1  5496.4  5531.4
  5537.6  5608.5  5693.5  5698.5  5708.5  5723.5  5728.5  5743.5  5831.7
    40.5    35.3   35.03   35.02   35.11    35.2    35.8    36.6   37.02   37.82
   37.89   38.92   39.81   39.88   40.05   40.05    40.7   40.18   39.96   39.96
   39.95   39.85   38.87   37.92   36.88   36.58   36.18   36.05   35.11   34.71
   34.67    34.7    34.4    35.3    37.9    44.7    46.3    47.2      50
   40.49   35.29   35.01   34.89   35.09   34.89   34.84   34.84   34.76    34.4
   37.28   38.56   39.47      39   35.55   38.44   39.09   38.57   38.35   31.35
   31.38   39.48   36.78   35.63    35.1   34.91   34.86    34.8   35.09   34.49
   34.59   34.69   34.39   35.29   37.89   44.69   46.29   47.19   49.99
Pier Skew, UpSta & Num, DnSta & Num=  ,4967.1, 2 ,4967.1, 2 , 0 , 0 , 0 ,,
     1.4     1.4
   24.69   39.72
     1.4     1.4
   24.68   39.71
Pier Skew, UpSta & Num, DnSta & Num=  ,4991.8, 2 ,4991.8, 2 , 0 , 0 , 0 ,,
     1.4     1.4
   15.44   39.98
     1.4     1.4
   15.43   39.97
Pier Skew, UpSta & Num, DnSta & Num=  ,5017, 2 ,5017, 2 , 0 , 0 , 0 ,,
     1.4     1.4
   19.33   39.99
     1.4     1.4
   19.32   39.98
Pier Skew, UpSta & Num, DnSta & Num=  ,5041.8, 2 ,5041.8, 2 , 0 , 0 , 0 ,,
     1.4     1.4
      25   39.79
     1.4     1.4
   24.99   39.78
Abutment Skew #Up #Dn= , 2 , 2
  5066.5 5078.79
      30   38.36
  5066.5 5078.79
   29.99   38.35
BR Coef= 1 , 1 , 0 ,1.25, 0 ,,,0.8,0,2,0,
WSPro=,,,, 1 ,,,, 0 ,,,, 0 ,,,,-1 ,-1 ,-1 , 0 , 0 , 0 , 0 , 0
BR U #Sta/Elev= 71
    4107    40.5    4332    35.3  4400.9   35.02  4430.3    34.9  4537.1    35.1
  4720.9    34.9  4738.3   34.88  4749.9   34.85  4750.3   34.85  4779.9   34.77
  4781.6   34.76  4824.3   34.44  4828.7   34.41  4831.8   37.29  4877.1   38.45
  4881.6   38.57  4927.3   39.43  4929.7   39.48  4933.2   39.01 4942.39   35.87
  4942.5   35.83 4942.61   35.79  4943.2   35.59 4943.31   35.56  4943.4   35.53
  4943.5   35.49    4944   35.32  4967.1   25.58  4970.1   26.07  4986.5   19.94
  4991.8   16.28  4995.1   17.03  5002.2   14.44  5003.4   14.78  5011.1   16.96
  5013.4   20.35  5017.1   20.32  5023.9   21.27  5041.8   26.19  5051.3    28.3
 5066.09   29.95  5066.2   29.96 5066.31   29.97  5066.5      30  5066.7   30.02
    5068   30.16 5078.59   31.34  5078.7   31.36    5079   31.39  5083.7   39.49
  5107.5   38.08  5129.3   36.79  5151.1   36.19  5164.2   35.83  5171.2   35.64
  5212.8   35.11  5228.1   34.92  5248.6   34.87  5273.1   34.81  5496.4    35.1
  5531.4    34.5  5537.6    34.6  5590.1   34.67  5608.5    34.7  5693.5    34.4
  5698.5    35.3  5708.5    37.9  5723.5    44.7  5728.5    46.3  5743.5    47.2
  5831.7      50
BR U #Mann= 5
    4107      .2  4400.9      .1  4933.2     .04  5083.7      .1  5151.1     .99
BR U Banks=4933.2,5083.7
BR D #Sta/Elev= 71
    4107   40.49    4332   35.29  4400.9   35.01  4430.3   34.89  4537.1   35.09
  4720.9   34.89  4738.3   34.87  4749.9   34.84  4750.3   34.84  4779.9   34.76
  4781.6   34.75  4824.3   34.43  4828.7    34.4  4831.8   37.28  4877.1   38.44
  4881.6   38.56  4927.3   39.42  4929.7   39.47  4933.2      39 4942.39   35.86
  4942.5   35.82 4942.61   35.78  4943.2   35.58 4943.31   35.55  4943.4   35.52
  4943.5   35.48    4944   35.31  4967.1   25.57  4970.1   26.06  4986.5   19.93
  4991.8   16.27  4995.1   17.02  5002.2   14.43  5003.4   14.77  5011.1   16.95
  5013.4   20.34  5017.1   20.31  5023.9   21.26  5041.8   26.18  5051.3   28.29
 5066.09   29.94  5066.2   29.95 5066.31   29.96  5066.5   29.99  5066.7   30.01
    5068   30.15 5078.59   31.33  5078.7   31.35    5079   31.38  5083.7   39.48
  5107.5   38.07  5129.3   36.78  5151.1   36.18  5164.2   35.82  5171.2   35.63
  5212.8    35.1  5228.1   34.91  5248.6   34.86  5273.1    34.8  5496.4   35.09
  5531.4   34.49  5537.6   34.59  5590.1   34.66  5608.5   34.69  5693.5   34.39
  5698.5   35.29  5708.5   37.89  5723.5   44.69  5728.5   46.29  5743.5   47.19
  5831.7   49.99
BR D #Mann= 5
    4107      .2  4400.9      .1  4933.2     .04  5083.7      .1  5151.1     .99
BR D Banks=4933.2,5083.7
BC Design=,, 0 ,, 0 ,,,,,,
BC HTab HWMax=50.01
BC Use User HTab Curves=0
BC User HTab FreeFlow(D)= 0

Type RM Length L Ch R = 1 ,47542.2 ,39.1,39.1,39.1
BEGIN DESCRIPTION:
Downstream Section of Bridge/Culvert/Weir
END DESCRIPTION:
XS GIS Cut Line= 6
      3151445.91     13855655.34      3151462.93     13855346.56
      3151602.34      13855043.5      3151719.65     13854758.16
        3151938.      13854306.5      3152164.12     13854155.89
#Sta/Elev= 30
    4107   40.85    4332   35.65  4400.9   35.37  4828.7   34.76  4831.8   37.64
  4929.7   39.83  4933.2   39.36    4944   35.67  4967.1   25.93  4970.1   26.42
  4986.5   20.29  4991.8   16.63  4995.1   17.38  5002.2   14.79  5011.1   17.31
  5013.4    20.7  5023.9   21.62  5051.3   28.65    5079   31.74  5083.7   39.84
  5129.3   37.14  5151.1   36.54  5228.1   35.27  5496.4   35.45  5531.4   34.85
  5693.5   34.75  5708.5   38.25  5723.5   45.05  5728.5   46.65  5831.7   50.35
#Mann= 5 , 1 , 0
    4107      .2       0  4400.9      .1       0  4933.2     .04       0
  5083.7      .1       0  5151.1     .99       0
#XS Ineff= 2 , 0
       0    4843      43    5163       0      41
Permanent Ineff=
       F       F
Bank Sta=4933.2,5083.7
XS Rating Curve= 0 ,0
Exp/Cntr=0.5,0.3

Type RM Length L Ch R = 1 ,47503.1 ,167.4,167.4,167.4
BEGIN DESCRIPTION:
Upstream Section of Bridge/Culvert/Weir
END DESCRIPTION:
XS GIS Cut Line= 4
      3151715.16     13855013.62      3151785.84      13854760.8
      3151861.93     13854602.27      3151951.15     13854412.32
#Sta/Elev= 30
 4795.89   48.09  4833.1   34.35  4923.1   33.32  4937.3   40.53    4954   35.13
  4960.5   28.14  4970.1   31.87  4985.9   17.82    4991   17.69    5001   16.17
    5002   16.17  5008.2   18.22  5016.8    19.4  5022.5      24  5043.1    31.9
    5056   29.25  5069.9   32.24  5070.3   37.68  5084.2   36.53  5107.9   37.49
  5156.9   36.45  5166.4   38.12  5210.3   36.01  5258.1   35.28  5294.9   35.24
  5296.5   38.44  5316.5   39.24  5336.5   39.64  5376.5   41.24 5444.11   50.64
#Mann= 3 , 1 , 0
 4795.89      .1       0  4937.3     .04       0  5070.3      .1       0
#XS Ineff= 2 , 0
       0    4943      43    5063       0      41
Permanent Ineff=
       F       F
Bank Sta=4937.3,5070.3
XS Rating Curve= 0 ,0
Exp/Cntr=0.5,0.3