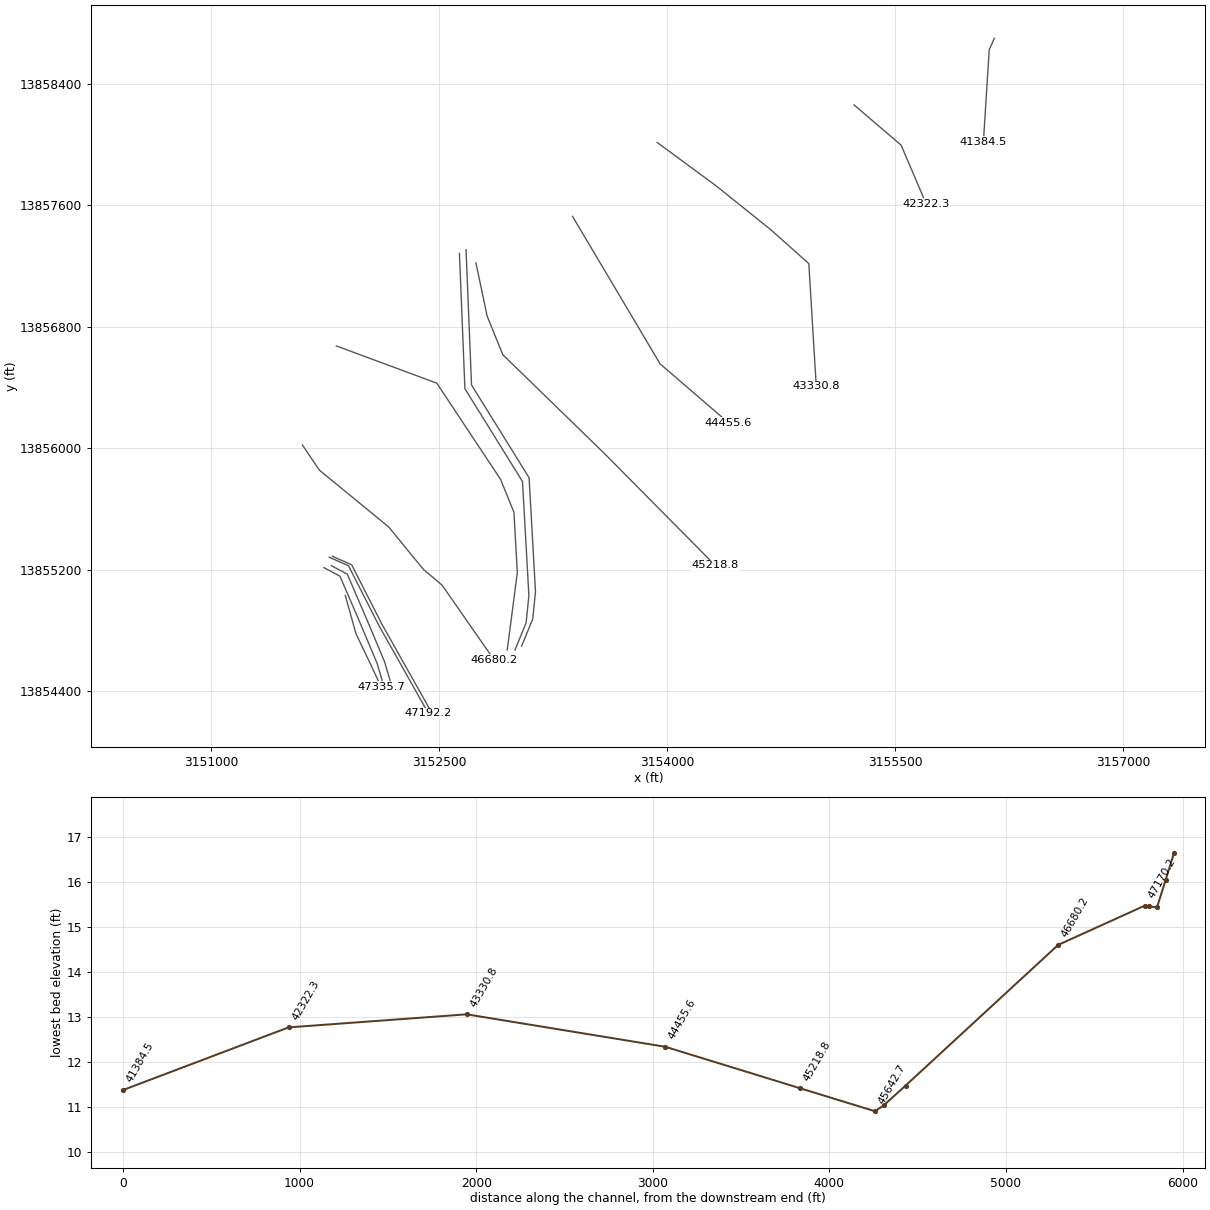
HEC-RAS study H100-00-00.prj: H100-00-00

--- H100-00-00.g01 (geometry) --- (continued)

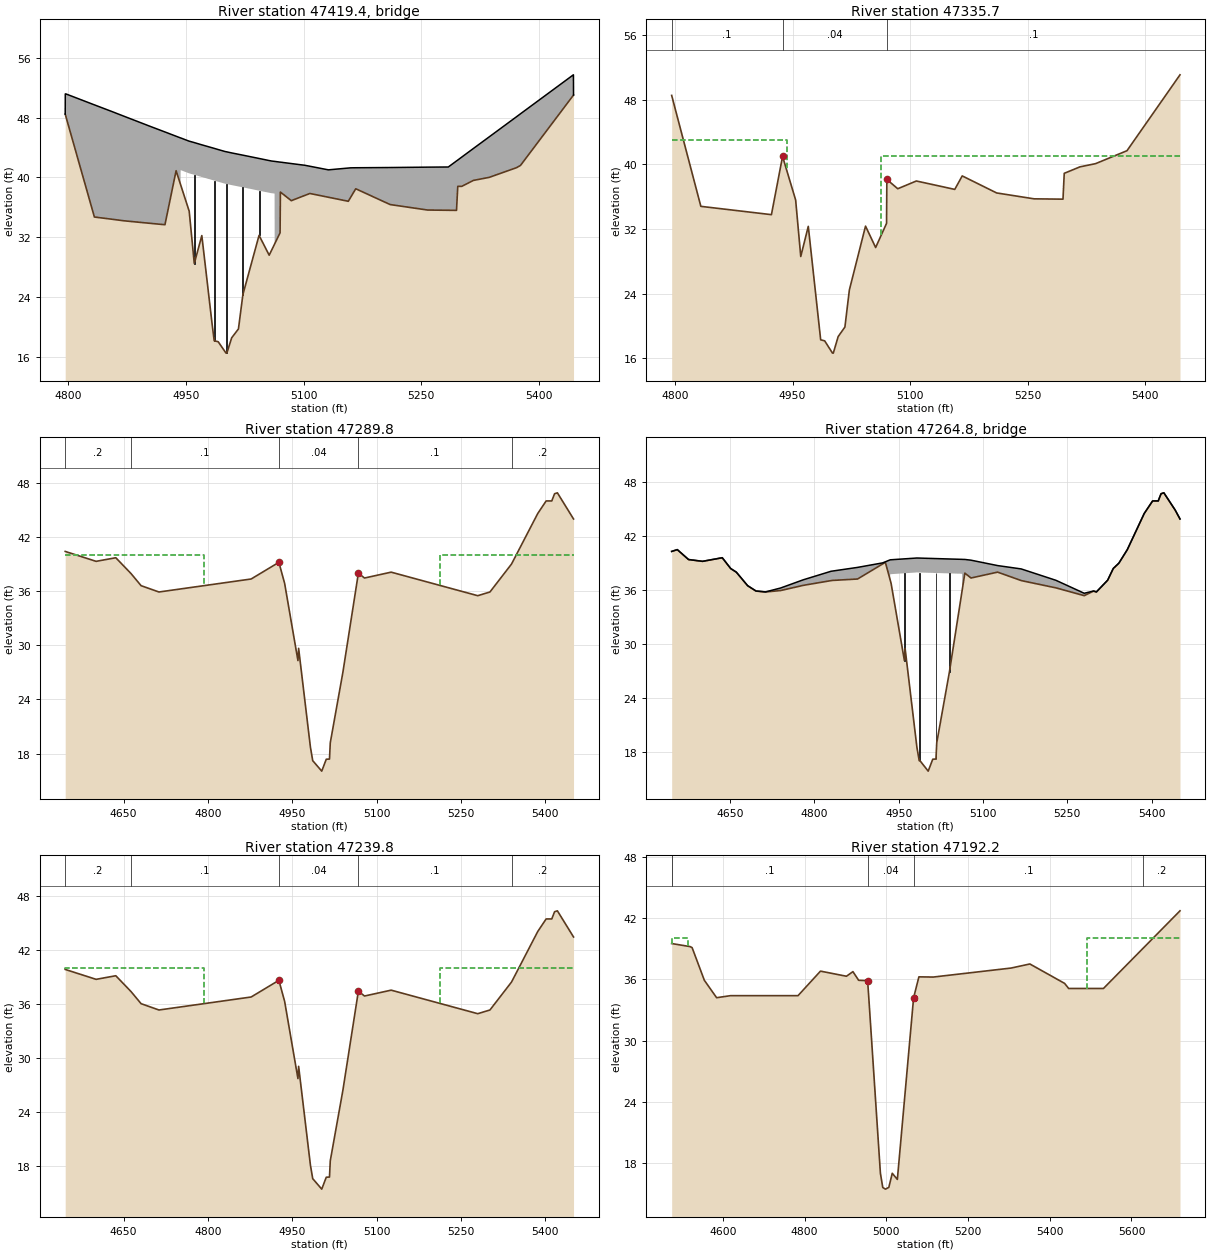
Type RM Length L Ch R = 3 ,47419.4 ,,,
BEGIN DESCRIPTION:
INTERSTATE 610
Structure ID: H00-29
END DESCRIPTION:
Bridge Culvert--1,0,-1,-1, 0
Deck Dist Width WeirC Skew NumUp NumDn MinLoCord MaxHiCord MaxSubmerge Is_Ogee
10,147.4,2.6,0, 54, 54, , , 0.95, 0, 1,1,,
 4795.89    4796 4796.11  4796.8  4833.1  4854.9  4871.1  4904.7  4923.1  4937.3
 4943.01  4943.1  4943.2  4953.4    4954  4960.5  4970.1  4983.2  4985.9    4991
    5000    5001    5002  5008.2  5016.8  5022.5  5043.1    5056    5059  5062.8
 5062.89    5063  5069.9  5070.3  5084.2  5101.4  5107.9  5131.5  5156.9  5160.1
  5166.4  5210.3  5258.1  5284.4  5294.9  5296.5  5301.5  5316.5  5336.5  5371.5
  5376.5 5443.89    5444 5444.11
   48.45   51.15   51.15   51.15   49.69   48.82   48.16    46.8   46.07    45.5
   45.27   45.27   45.27   44.86   44.84   44.65   44.35   43.96   43.88   43.72
   43.45   43.43   43.41   43.27   43.09   42.97   42.53   42.25   42.19   42.14
   42.14   42.14   42.04   42.04   41.85   41.62   41.49   41.01   41.25   41.28
   41.29   41.32   41.37   41.39    42.2   42.32   42.71   43.87   45.41   48.11
    48.5    53.7    53.7      51
   48.45   48.41   48.37   48.11   34.71   34.42    34.2   33.86   33.68   40.89
   39.04   40.97   40.97   40.56   40.54   40.35   40.05   39.66   39.58   39.42
   39.15   39.13   39.11   38.97   38.79   38.67   38.23   37.95   37.89   37.84
   37.84   31.12    32.6   38.04   36.89   37.59   37.85   37.35   36.81   37.37
   38.48   36.37   35.64   35.61    35.6    38.8    38.8    39.6      40    41.3
    41.6   50.97   50.98      51
 4795.89    4796 4796.11  4796.8  4833.1  4854.9  4871.1  4904.7  4923.1  4937.3
 4943.01  4943.1  4943.2  4953.4    4954  4960.5  4970.1  4983.2  4985.9    4991
    5000    5001    5002  5008.2  5016.8  5022.5  5043.1    5056    5059  5062.8
 5062.89    5063  5069.9  5070.3  5084.2  5101.4  5107.9  5131.5  5156.9  5160.1
  5166.4  5210.3  5258.1  5284.4  5294.9  5296.5  5301.5  5316.5  5336.5  5371.5
  5376.5 5443.89    5444 5444.11
   48.67   51.15   51.15   51.15   49.69   48.82   48.16    46.8   46.07    45.5
   45.27   45.27   45.27   44.86   44.84   44.65   44.35   43.96   43.88   43.72
   43.45   43.43   43.41   43.27   43.09   42.97   42.53   42.25   42.19   42.14
   42.14   42.14   42.04   42.04   41.85   41.62   41.49   41.01   41.25   41.28
   41.29   41.32   41.37   41.39    42.2   42.32   42.71   43.87   45.41   48.11
    48.5    53.7    53.7   51.22
   48.67   48.63   48.59   48.33   34.93   34.64   34.42   34.08    33.9   41.11
   39.26   41.19   41.19   40.78   40.76   40.57   40.27   39.88    39.8   39.64
   39.37   39.35   39.33   39.19   39.01   38.89   38.45   38.17   38.11   38.06
   38.06   31.34   32.82   38.26   37.11   37.81   38.07   37.57   37.03   37.59
    38.7   36.59   35.86   35.83   35.82   39.02   39.02   39.82   40.22   41.52
   41.82   51.19    51.2   51.22
Pier Skew, UpSta & Num, DnSta & Num=  ,4960.5, 2 ,4960.5, 2 , 0 , 0 , 0 ,,
     1.4     1.4
   27.77   41.37
     1.4     1.4
   27.99   41.59
Pier Skew, UpSta & Num, DnSta & Num=  ,4985.9, 2 ,4985.9, 2 , 0 , 0 , 0 ,,
     1.4     1.4
   17.16    40.6
     1.4     1.4
   17.38   40.82
Pier Skew, UpSta & Num, DnSta & Num=  ,5002, 2 ,5002, 2 , 0 , 0 , 0 ,,
     1.4     1.4
   15.53   40.12
     1.4     1.4
   15.75   40.34
Pier Skew, UpSta & Num, DnSta & Num=  ,5022.5, 2 ,5022.5, 2 , 0 , 0 , 0 ,,
     1.4     1.4
    22.8   39.68
     1.4     1.4
   23.02    39.9
Pier Skew, UpSta & Num, DnSta & Num=  ,5043.1, 2 ,5043.1, 2 , 0 , 0 , 0 ,,
     1.4     1.4
   30.99   39.24
     1.4     1.4
   31.21   39.46
BR Coef= 1 , 1 , 0 ,1.25, 0 ,,,0.8,0,2,0,
WSPro=,,,, 1 ,,,, 0 ,,,, 0 ,,,,-1 ,-1 ,-1 , 0 , 0 , 0 , 0 , 0
BR U #Sta/Elev= 54
 4795.89   48.45    4796   48.41 4796.11   48.37  4796.8   48.11  4833.1   34.71
  4854.9   34.42  4871.1    34.2  4904.7   33.86  4923.1   33.68  4937.3   40.89
 4943.01   39.04  4943.1   39.01  4943.2   38.98  4953.4   35.68    4954   35.49
  4960.5    28.5  4970.1   32.23  4983.2   20.43  4985.9   18.18    4991   18.05
    5000   16.68    5001   16.53    5002   16.53  5008.2   18.58  5016.8   19.76
  5022.5   24.36  5043.1   32.26    5056   29.61    5059   30.26  5062.8   31.07
 5062.89   31.09    5063   31.12  5069.9    32.6  5070.3   38.04  5084.2   36.89
  5101.4   37.59  5107.9   37.85  5131.5   37.35  5156.9   36.81  5160.1   37.37
  5166.4   38.48  5210.3   36.37  5258.1   35.64  5284.4   35.61  5294.9    35.6
  5296.5    38.8  5301.5    38.8  5316.5    39.6  5336.5      40  5371.5    41.3
  5376.5    41.6 5443.89   50.97    5444   50.98 5444.11      51
BR U #Mann= 3
 4795.89      .1  4937.3     .04  5070.3      .1
BR U Banks=4937.3,5070.3
BR D #Sta/Elev= 54
 4795.89   48.67    4796   48.63 4796.11   48.59  4796.8   48.33  4833.1   34.93
  4854.9   34.64  4871.1   34.42  4904.7   34.08  4923.1    33.9  4937.3   41.11
 4943.01   39.26  4943.1   39.23  4943.2    39.2  4953.4    35.9    4954   35.71
  4960.5   28.72  4970.1   32.45  4983.2   20.65  4985.9    18.4    4991   18.27
    5000    16.9    5001   16.75    5002   16.75  5008.2    18.8  5016.8   19.98
  5022.5   24.58  5043.1   32.48    5056   29.83    5059   30.48  5062.8   31.29
 5062.89   31.31    5063   31.34  5069.9   32.82  5070.3   38.26  5084.2   37.11
  5101.4   37.81  5107.9   38.07  5131.5   37.57  5156.9   37.03  5160.1   37.59
  5166.4    38.7  5210.3   36.59  5258.1   35.86  5284.4   35.83  5294.9   35.82
  5296.5   39.02  5301.5   39.02  5316.5   39.82  5336.5   40.22  5371.5   41.52
  5376.5   41.82 5443.89   51.19    5444    51.2 5444.11   51.22
BR D #Mann= 3
 4795.89      .1  4937.3     .04  5070.3      .1
BR D Banks=4937.3,5070.3
BC Design=,, 0 ,, 0 ,,,,,,
BC HTab HWMax=50.64
BC Use User HTab Curves=0
BC User HTab FreeFlow(D)= 0

Type RM Length L Ch R = 1 ,47335.7 ,45.9,45.9,45.9
BEGIN DESCRIPTION:
Downstream Section of Bridge/Culvert/Weir
END DESCRIPTION:
XS GIS Cut Line= 4
      3151881.56      13855031.9      3151952.24     13854779.08
      3152028.33     13854620.55      3152117.55      13854430.6
#Sta/Elev= 30
 4795.89   48.55  4833.1   34.81  4923.1   33.78  4937.3   40.99    4954   35.59
  4960.5    28.6  4970.1   32.33  4985.9   18.28    4991   18.15    5001   16.63
    5002   16.63  5008.2   18.68  5016.8   19.86  5022.5   24.46  5043.1   32.36
    5056   29.71  5069.9    32.7  5070.3   38.14  5084.2   36.99  5107.9   37.95
  5156.9   36.91  5166.4   38.58  5210.3   36.47  5258.1   35.74  5294.9    35.7
  5296.5    38.9  5316.5    39.7  5336.5    40.1  5376.5    41.7 5444.11    51.1
#Mann= 3 , 1 , 0
 4795.89      .1       0  4937.3     .04       0  5070.3      .1       0
#XS Ineff= 2 , 0
       0    4943      43    5063       0      41
Permanent Ineff=
       F       F
Bank Sta=4937.3,5070.3
XS Rating Curve= 0 ,0
Exp/Cntr=0.5,0.3

Type RM Length L Ch R = 1 ,47289.8 ,50,50,50
BEGIN DESCRIPTION:
Upstream Section of Bridge/Culvert/Weir
END DESCRIPTION:
XS GIS Cut Line= 5
      3151741.24     13855215.22      3151846.41     13855159.13
      3151978.81     13854851.68      3152091.02     13854584.63
      3152136.72     13854430.67
#Sta/Elev= 30
  4546.2   40.42  4601.2   39.32  4636.2   39.72  4663.2   37.97  4681.2   36.62
    4713   35.92  4876.9   37.36  4926.3   39.21  4936.5   36.88  4960.2   28.31
  4961.4   29.67  4982.4    18.7  4986.5   17.21  5002.5   16.05  5010.6   17.37
  5016.3   17.39  5017.7   19.19  5040.1      27  5067.7   38.01  5078.6   37.47
    5126   38.12    5280   35.51  5301.7   35.92  5340.1   39.02  5386.7   44.62
  5401.7   46.02  5411.7   46.02  5416.7   46.82  5421.7   46.92  5450.4   44.02
#Mann= 5 , 1 , 0
  4546.2      .2       0  4663.2      .1       0  4926.3     .04       0
  5067.7      .1       0  5340.1      .2       0
#XS Ineff= 2 , 0
       0    4793      40    5213       0      40
Permanent Ineff=
       F       F
Bank Sta=4926.3,5067.7
XS Rating Curve= 0 ,0
Exp/Cntr=0.5,0.3

Type RM Length L Ch R = 3 ,47264.8 ,,,
BEGIN DESCRIPTION:
ACCESS ROAD NORTH
Structure ID: H00-28
END DESCRIPTION:
Bridge Culvert--1,0,-1,-1, 0
Deck Dist Width WeirC Skew NumUp NumDn MinLoCord MaxHiCord MaxSubmerge Is_Ogee
10,30,2.6,0, 40, 40, , , 0.95, 0, 1,1,,
  4546.2  4556.2  4576.2  4601.2  4636.2  4651.2  4661.2  4681.2  4696.2    4713
  4739.8  4780.6  4829.7  4876.9  4921.5  4926.3 4934.91    4935  4982.4 5062.79
  5062.9  5067.7  5078.6    5126  5167.9  5229.6    5280  5296.7  5301.7  5321.7
  5331.7  5341.7  5356.7  5386.7  5401.7  5411.7  5416.7  5421.7  5441.7  5450.4
    40.3    40.5    39.4    39.2    39.6    38.4      38   36.51   35.91   35.81
   36.24   37.16    38.1   38.53   39.03   39.15   39.37   39.37   39.57   39.42
   39.42   39.41   39.33   38.73   38.36    37.1   35.66   35.91   35.81   37.11
   38.41      39    40.5    44.5    45.9    45.9    46.7    46.8    44.9    43.9
    40.3    40.5    39.4    39.2    39.6    38.4      38    36.5    35.9    35.8
   35.96   36.54   37.06   37.24   38.91   39.09   37.12   37.77   37.97   37.82
   35.98   37.89   37.35      38   37.07   36.26   35.39    35.9    35.8    37.1
    38.4      39    40.5    44.5    45.9    45.9    46.7    46.8    44.9    43.9
  4546.2  4556.2  4576.2  4601.2  4636.2  4651.2  4661.2  4681.2  4696.2    4713
  4739.8  4780.6  4829.7  4876.9  4921.5  4926.3 4934.91    4935  4982.4 5062.79
  5062.9  5067.7  5078.6    5126  5167.9  5229.6    5280  5296.7  5301.7  5321.7
  5331.7  5341.7  5356.7  5386.7  5401.7  5411.7  5416.7  5421.7  5441.7  5450.4
    40.3    40.5    39.4    39.2    39.6    38.4      38   36.51   35.91   35.81
   36.24   37.16    38.1   38.53   39.03   39.15   39.37   39.37   39.57   39.42
   39.42   39.41   39.33   38.73   38.36    37.1   35.66   35.91   35.81   37.11
   38.41      39    40.5    44.5    45.9    45.9    46.7    46.8    44.9    43.9
   39.79   39.99   38.89   38.69   39.09   37.89   37.49   35.99   35.39   35.29
   35.45   36.03   36.55   36.73    38.4   38.58   36.61   37.26   37.46   37.31
   35.47   37.38   36.84   37.49   36.56   35.75   34.88   35.39   35.29   36.59
   37.89   38.49   39.99   43.99   45.39   45.39   46.19   46.29   44.39   43.39
Pier Skew, UpSta & Num, DnSta & Num=  ,4960.2, 2 ,4960.2, 2 , 0 , 0 , 0 ,,
     1.4     1.4
   27.44   38.88
     1.4     1.4
   26.93   38.37
Pier Skew, UpSta & Num, DnSta & Num=  ,4987.6, 2 ,4987.6, 2 , 0 , 0 , 0 ,,
     1.4     1.4
   16.05   38.96
     1.4     1.4
   15.54   38.45
Pier Skew, UpSta & Num, DnSta & Num=  ,5016.3, 2 ,5016.3, 2 , 0 , 0 , 0 ,,
     1.4     1.4
   16.27   38.91
     1.4     1.4
   15.76    38.4
Pier Skew, UpSta & Num, DnSta & Num=  ,5040.1, 2 ,5040.1, 2 , 0 , 0 , 0 ,,
     1.4     1.4
   25.64   38.86
     1.4     1.4
   25.13   38.35
BR Coef= 1 , 1 , 0 ,1.25, 0 ,,,0.8,0,2,0,
WSPro=,,,, 1 ,,,, 0 ,,,, 0 ,,,,-1 ,-1 ,-1 , 0 , 0 , 0 , 0 , 0
BR U #Sta/Elev= 70
  4546.2    40.3  4556.2    40.5  4576.2    39.4  4601.2    39.2  4636.2    39.6
  4651.2    38.4  4661.2      38  4663.2   37.85  4681.2    36.5  4696.2    35.9
    4713    35.8  4739.8   35.96  4740.7   35.97  4779.9   36.53  4780.6   36.54
  4829.7   37.06  4831.6   37.08  4876.9   37.24  4877.7   37.27  4921.5   38.91
  4926.3   39.09 4933.89   37.36    4934   37.33 4934.11   37.31  4934.8   37.15
 4934.91   37.12    4935    37.1  4935.1   37.08  4936.5   36.76  4960.2   28.19
  4961.4   29.55  4981.7   18.95  4982.4   18.58  4986.5   17.09  4987.6   17.11
  5002.5   15.93  5010.6   17.25  5016.3   17.27  5017.7   19.07  5040.1   26.88
  5062.6   35.86 5062.79   35.93  5062.9   35.98  5067.7   37.89 5073.19   37.62
  5073.3   37.61 5073.41   37.61  5078.6   37.35  5125.8      38    5126      38
  5167.9   37.07  5168.4   37.06  5229.5   36.26  5229.6   36.26  5279.6    35.4
    5280   35.39  5296.7    35.9  5301.7    35.8  5321.7    37.1  5331.7    38.4
  5340.1    38.9  5341.7      39  5356.7    40.5  5386.7    44.5  5401.7    45.9
  5411.7    45.9  5416.7    46.7  5421.7    46.8  5441.7    44.9  5450.4    43.9
BR U #Mann= 5
  4546.2      .2  4663.2      .1  4926.3     .04  5067.7      .1  5340.1      .2
BR U Banks=4926.3,5067.7
BR D #Sta/Elev= 70
  4546.2   39.79  4556.2   39.99  4576.2   38.89  4601.2   38.69  4636.2   39.09
  4651.2   37.89  4661.2   37.49  4663.2   37.34  4681.2   35.99  4696.2   35.39
    4713   35.29  4739.8   35.45  4740.7   35.46  4779.9   36.02  4780.6   36.03
  4829.7   36.55  4831.6   36.57  4876.9   36.73  4877.7   36.76  4921.5    38.4
  4926.3   38.58 4933.89   36.85    4934   36.82 4934.11    36.8  4934.8   36.64
 4934.91   36.61    4935   36.59  4935.1   36.57  4936.5   36.25  4960.2   27.68
  4961.4   29.04  4981.7   18.44  4982.4   18.07  4986.5   16.58  4987.6    16.6
  5002.5   15.42  5010.6   16.74  5016.3   16.76  5017.7   18.56  5040.1   26.37
  5062.6   35.35 5062.79   35.42  5062.9   35.47  5067.7   37.38 5073.19   37.11
  5073.3    37.1 5073.41    37.1  5078.6   36.84  5125.8   37.49    5126   37.49
  5167.9   36.56  5168.4   36.55  5229.5   35.75  5229.6   35.75  5279.6   34.89
    5280   34.88  5296.7   35.39  5301.7   35.29  5321.7   36.59  5331.7   37.89
  5340.1   38.39  5341.7   38.49  5356.7   39.99  5386.7   43.99  5401.7   45.39
  5411.7   45.39  5416.7   46.19  5421.7   46.29  5441.7   44.39  5450.4   43.39
BR D #Mann= 5
  4546.2      .2  4663.2      .1  4926.3     .04  5067.7      .1  5340.1      .2
BR D Banks=4926.3,5067.7
BC Design=,, 0 ,, 0 ,,,,,,
BC HTab HWMax=46.92
BC Use User HTab Curves=0
BC User HTab FreeFlow(D)= 0

Type RM Length L Ch R = 1 ,47239.8 ,47.6,47.6,47.6
BEGIN DESCRIPTION:
Downstream Section of Bridge/Culvert/Weir
END DESCRIPTION:
XS GIS Cut Line= 5
      3151789.42     13855228.56      3151894.59     13855172.47
      3152026.99     13854865.02       3152139.2     13854597.97
      3152184.91     13854444.02
#Sta/Elev= 30
  4546.2    39.8  4601.2    38.7  4636.2    39.1  4663.2   37.35  4681.2      36
    4713    35.3  4876.9   36.74  4926.3   38.59  4936.5   36.26  4960.2   27.69
  4961.4   29.05  4982.4   18.08  4986.5   16.59  5002.5   15.43  5010.6   16.75
  5016.3   16.77  5017.7   18.57  5040.1   26.38  5067.7   37.39  5078.6   36.85
    5126    37.5    5280   34.89  5301.7    35.3  5340.1    38.4  5386.7      44
  5401.7    45.4  5411.7    45.4  5416.7    46.2  5421.7    46.3  5450.4    43.4
#Mann= 5 , 1 , 0
  4546.2      .2       0  4663.2      .1       0  4926.3     .04       0
  5067.7      .1       0  5340.1      .2       0
#XS Ineff= 2 , 0
       0    4793      40    5213       0      40
Permanent Ineff=
       F       F
Bank Sta=4926.3,5067.7
XS Rating Curve= 0 ,0
Exp/Cntr=0.5,0.3

Type RM Length L Ch R = 1 ,47192.2 ,22,22,22
BEGIN DESCRIPTION:
Upstream Section of Bridge/Culvert/Weir
END DESCRIPTION:
XS GIS Cut Line= 4
      3151775.71     13855283.67      3151902.54     13855227.94
      3152102.26     13854835.22      3152428.55     13854255.91
#Sta/Elev= 29
  4474.7   39.49  4519.7   39.19  4524.7   39.09  4554.7   35.89  4584.7   34.19
  4618.9   34.39  4783.9   34.39  4838.9   36.79  4902.4   36.29 4918.32   36.74
 4932.32   35.89 4954.22   35.86 4957.22   34.12 4985.52   17.02 4991.32   15.62
 4997.92   15.46 5006.12   15.63 5014.52   17.01 5027.02   16.41 5066.72   34.17
 5079.72   36.23 5114.82   36.21  5305.3   37.09  5351.3   37.49  5436.3   35.59
  5446.3   35.09  5531.3   35.09  5628.7   39.04  5718.7   42.69
#Mann= 5 , 1 , 0
  4474.7      .2       0  4474.7      .1       0 4954.22     .04       0
 5066.72      .1       0  5628.7      .2       0
#XS Ineff= 2 , 0
       0    4514      40    5492       0      40
Permanent Ineff=
       F       F
Bank Sta=4954.22,5066.72
XS Rating Curve= 0 ,0
Exp/Cntr=0.5,0.3

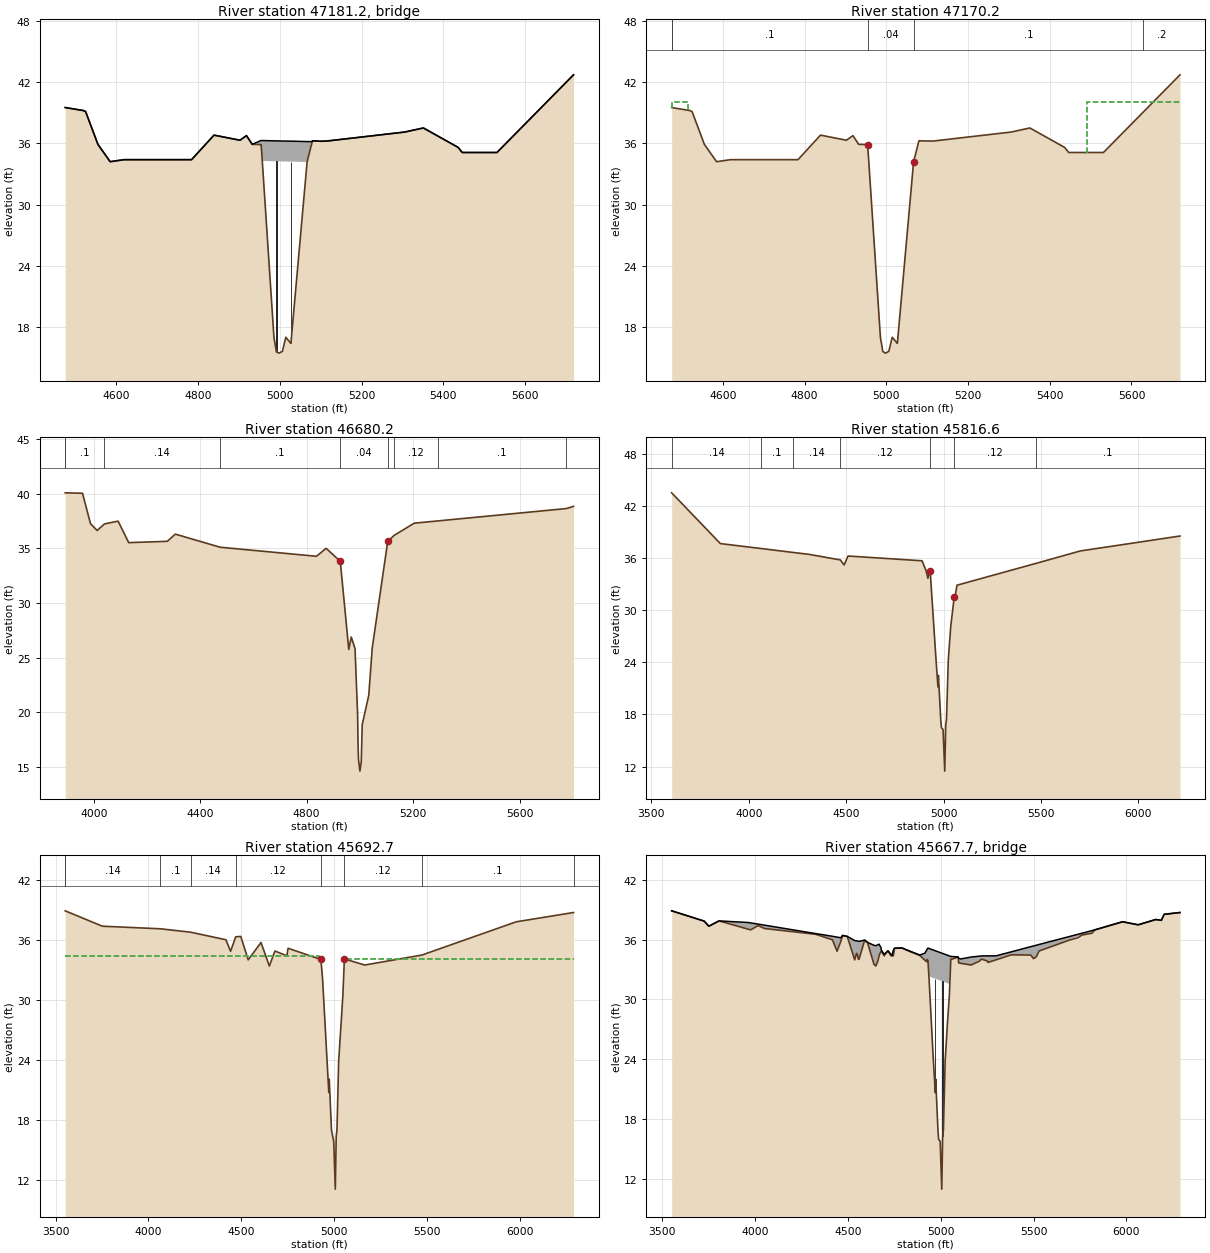
Type RM Length L Ch R = 3 ,47181.2 ,,,
BEGIN DESCRIPTION:
Pipeline
END DESCRIPTION:
Bridge Culvert--1,0,-1,-1, 0
Deck Dist Width WeirC Skew NumUp NumDn MinLoCord MaxHiCord MaxSubmerge Is_Ogee
10,2,2.6,0, 37, 37, , , 0.95, 0, 1,1,,
  4474.7  4519.7  4524.7  4554.7  4584.7  4618.9  4783.9  4838.9  4902.4 4918.32
 4932.32 4953.62 4953.73 4953.82 4954.22 4957.22 4985.52 4991.32 4992.02 4997.92
 5006.12 5014.52 5027.02 5066.51 5066.62 5066.72 5078.72 5079.72 5101.72 5114.82
  5305.3  5351.3  5436.3  5446.3  5531.3  5628.7  5718.7
    39.5    39.2    39.1    35.9    34.2    34.4    34.4    36.8    36.3   36.75
    35.9   36.27   36.27   36.27   36.27   36.27   36.24   36.24   36.24   36.23
   36.22   36.22   36.21   36.17   36.17   36.17   36.16   36.24    36.2   36.22
    37.1    37.5    35.6    35.1    35.1   39.05    42.7
    39.5    39.2    39.1    35.9    34.2    34.4    34.4    36.8    36.3   36.75
    35.9   35.87   35.87   35.87   35.87   34.27   34.24   34.24   34.24   34.23
   34.22   34.22   34.21   34.17   34.16   34.18   36.08   36.24    36.2   36.22
    37.1    37.5    35.6    35.1    35.1   39.05    42.7
  4474.7  4519.7  4524.7  4554.7  4584.7  4618.9  4783.9  4838.9  4902.4 4918.32
 4932.32 4953.62 4953.73 4953.82 4954.22 4957.22 4985.52 4991.32 4992.02 4997.92
 5006.12 5014.52 5027.02 5066.51 5066.62 5066.72 5078.72 5079.72 5101.72 5114.82
  5305.3  5351.3  5436.3  5446.3  5531.3  5628.7  5718.7
    39.5    39.2    39.1    35.9    34.2    34.4    34.4    36.8    36.3   36.75
    35.9   36.27   36.27   36.27   36.27   36.27   36.24   36.24   36.24   36.23
   36.22   36.22   36.21   36.17   36.17   36.17   36.16   36.24    36.2   36.22
    37.1    37.5    35.6    35.1    35.1   39.05    42.7
    39.5    39.2    39.1    35.9    34.2    34.4    34.4    36.8    36.3   36.75
    35.9   35.87   35.87   35.87   35.87   34.27   34.24   34.24   34.24   34.23
   34.22   34.22   34.21   34.17   34.16   34.18   36.08   36.24    36.2   36.22
    37.1    37.5    35.6    35.1    35.1   39.05    42.7
Pier Skew, UpSta & Num, DnSta & Num=  ,4991.3, 2 ,4991.3, 2 , 0 , 0 , 0 ,,
     1.4     1.4
   14.58   35.24
     1.4     1.4
   14.58   35.24
Pier Skew, UpSta & Num, DnSta & Num=  ,5027, 2 ,5027, 2 , 0 , 0 , 0 ,,
     1.4     1.4
   15.45   35.21
     1.4     1.4
   15.45   35.21
BR Coef= 1 , 1 , 0 ,1.25, 0 ,,,0.8,-1,2,0,
WSPro=,,,, 1 ,,,, 0 ,,,, 0 ,,,,-1 ,-1 ,-1 , 0 , 0 , 0 , 0 , 0
BR U #Sta/Elev= 37
  4474.7    39.5  4519.7    39.2  4524.7    39.1  4554.7    35.9  4584.7    34.2
  4618.9    34.4  4783.9    34.4  4838.9    36.8  4902.4    36.3 4918.32   36.75
 4932.32    35.9 4953.62   35.87 4953.73   35.87 4953.82   35.87 4954.22   35.87
 4957.22   34.13 4985.52   17.03 4991.32   15.63 4992.02   15.58 4997.92   15.47
 5006.12   15.64 5014.52   17.02 5027.02   16.42 5066.51   34.11 5066.62   34.16
 5066.72   34.18 5078.72   36.08 5079.72   36.24 5101.72    36.2 5114.82   36.22
  5305.3    37.1  5351.3    37.5  5436.3    35.6  5446.3    35.1  5531.3    35.1
  5628.7   39.05  5718.7    42.7
BR U #Mann= 5
  4474.7      .2  4474.7      .1 4954.22     .04 5066.72      .1  5628.7      .2
BR U Banks=4954.22,5066.72
BR D #Sta/Elev= 37
  4474.7    39.5  4519.7    39.2  4524.7    39.1  4554.7    35.9  4584.7    34.2
  4618.9    34.4  4783.9    34.4  4838.9    36.8  4902.4    36.3 4918.32   36.75
 4932.32    35.9 4953.62   35.87 4953.73   35.87 4953.82   35.87 4954.22   35.87
 4957.22   34.13 4985.52   17.03 4991.32   15.63 4992.02   15.58 4997.92   15.47
 5006.12   15.64 5014.52   17.02 5027.02   16.42 5066.51   34.11 5066.62   34.16
 5066.72   34.18 5078.72   36.08 5079.72   36.24 5101.72    36.2 5114.82   36.22
  5305.3    37.1  5351.3    37.5  5436.3    35.6  5446.3    35.1  5531.3    35.1
  5628.7   39.05  5718.7    42.7
BR D #Mann= 5
  4474.7      .2  4474.7      .1 4954.22     .04 5066.72      .1  5628.7      .2
BR D Banks=4954.22,5066.72
BC Design=,, 0 ,, 0 ,,,,,,
BC HTab HWMax=42.69
BC Use User HTab Curves=0
BC User HTab FreeFlow(D)= 0

Type RM Length L Ch R = 1 ,47170.2 ,490,490,490
BEGIN DESCRIPTION:
Downstream Section of Bridge/Culvert/Weir
END DESCRIPTION:
XS GIS Cut Line= 4
      3151796.92     13855289.54      3151923.74     13855233.82
      3152123.46      13854841.1      3152449.75     13854261.78
#Sta/Elev= 29
  4474.7    39.5  4519.7    39.2  4524.7    39.1  4554.7    35.9  4584.7    34.2
  4618.9    34.4  4783.9    34.4  4838.9    36.8  4902.4    36.3 4918.32   36.75
 4932.32    35.9 4954.22   35.87 4957.22   34.13 4985.52   17.03 4991.32   15.63
 4997.92   15.47 5006.12   15.64 5014.52   17.02 5027.02   16.42 5066.72   34.18
 5079.72   36.24 5114.82   36.22  5305.3    37.1  5351.3    37.5  5436.3    35.6
  5446.3    35.1  5531.3    35.1  5628.7   39.05  5718.7    42.7
#Mann= 5 , 1 , 0
  4474.7      .2       0  4474.7      .1       0 4954.22     .04       0
 5066.72      .1       0  5628.7      .2       0
#XS Ineff= 2 , 0
       0    4514      40    5492       0      40
Permanent Ineff=
       F       F
Bank Sta=4954.22,5066.72
XS Rating Curve= 0 ,0
Exp/Cntr=0.5,0.3

Type RM Length L Ch R = 1 ,46680.2 ,837.8,863.6,692.5
BEGIN DESCRIPTION:
Cross Section 46680.2
END DESCRIPTION:
XS GIS Cut Line= 6
      3151599.55     13856022.25      3151710.52     13855857.39
      3152167.06     13855483.28      3152395.33     13855204.28
      3152518.98     13855099.66      3152860.88     13854608.39
#Sta/Elev= 30
  3892.8   40.08  3957.8   40.04  3987.8   37.26  4012.8   36.63  4040.1   37.23
  4091.5   37.49  4131.5   35.52  4276.5   35.64  4306.5    36.3  4474.8    35.1
  4836.8   34.27  4873.2      35  4926.4   33.81  4958.3   25.74  4967.7   26.88
  4981.8   25.82  4991.5   19.79  4993.3   16.88  4994.9   15.63  5000.2    14.6
  5005.2   15.46  5008.8   18.85  5033.4   21.54  5046.5   25.88  5104.6   35.63
  5128.6   36.18  5204.2    37.3  5293.8   37.51  5775.9   38.64  5802.8   38.84
#Mann= 9 , 1 , 0
  3892.8      .2       0  3892.8      .1       0  4040.1     .14       0
  4474.8      .1       0  4926.4     .04       0  5104.6     .14       0
  5128.6     .12       0  5293.8      .1       0  5775.9      .2       0
Bank Sta=4926.4,5104.6
XS Rating Curve= 0 ,0
Exp/Cntr=0.3,0.1

Type RM Length L Ch R = 1 ,45816.6 ,126.6,123.9,88
BEGIN DESCRIPTION:
Cross Section 45816.6
END DESCRIPTION:
XS GIS Cut Line= 6
      3151822.68     13856674.74        3152484.     13856429.59
      3152903.55     13855796.58      3152991.88     13855579.44
      3153013.96     13855181.97      3152947.72     13854674.09
#Sta/Elev= 30
    3604    43.5    3854   37.66  4064.1   37.09  4227.1   36.64  4309.3   36.42
    4470   35.78  4489.3    35.2  4509.3   36.23  4889.3   35.68  4909.3   34.59
  4919.3   33.67  4928.3   34.49  4931.6   34.33  4958.1   25.27  4970.8   21.16
  4973.2    22.5  4985.3   17.39  4988.9   16.47  4997.3   16.26  5005.8   11.48
  5010.7   16.79  5014.7    17.4    5024   24.27  5036.6   28.15  5054.6   31.54
  5059.3   31.67  5068.7   32.87  5472.1   35.37  5701.2   36.81  6213.4   38.53
#Mann= 7 , 1 , 0
    3604     .14       0  4064.1      .1       0  4227.1     .14       0
    4470     .12       0  4928.3     .04       0  5054.6     .12       0
  5472.1      .1       0
Bank Sta=4928.3,5054.6
XS Rating Curve= 0 ,0
Exp/Cntr=0.5,0.3

Type RM Length L Ch R = 1 ,45692.7 ,50,50,50
BEGIN DESCRIPTION:
Upstream Section of Bridge/Culvert/Weir
END DESCRIPTION:
XS GIS Cut Line= 6
        3152633.     13857283.64      3152669.01     13856393.17
      3153048.03     13855782.22      3153090.17     13855031.23
      3153071.85     13854852.01       3152998.8     13854673.44
#Sta/Elev= 30
  3551.9   38.92  3751.9   37.38  4064.1   37.12  4227.1   36.78  4417.1   36.02
  4442.1   34.87    4470   36.32  4497.1   36.35  4537.1   34.01  4605.8   35.75
  4650.8   33.39  4680.8   34.89  4745.1   34.42  4751.5   35.17  4928.3   34.05
  4937.4   32.09  4970.8   20.72  4973.2   22.06  4985.3   16.95  4997.3   15.82
  5005.8   11.04  5010.7   16.35  5014.7   16.96  5023.9   23.83  5046.6   30.44
  5054.6    34.1    5164   33.49  5472.1   34.49  5979.5   37.82  6288.2   38.75
#Mann= 9 , 1 , 0
  3551.9      .2       0  3551.9     .14       0  4064.1      .1       0
  4227.1     .14       0    4470     .12       0  4928.3     .04       0
  5054.6     .12       0  5472.1      .1       0  6288.2      .2       0
#XS Ineff= 2 , 0
       0  4918.3   34.39  5064.6       0   34.06
Permanent Ineff=
       F       F
Bank Sta=4928.3,5054.6
XS Rating Curve= 0 ,0
Exp/Cntr=0.5,0.3

Type RM Length L Ch R = 3 ,45667.7 ,,,
BEGIN DESCRIPTION:
MANITOU ROAD
Structure ID: HOO-26
END DESCRIPTION:
Bridge Culvert--1,0,-1,-1, 0
Deck Dist Width WeirC Skew NumUp NumDn MinLoCord MaxHiCord MaxSubmerge Is_Ogee
10,30,2.6,0, 60, 60, , , 0.95, 0, 1,1,,
  3551.9  3726.9  3751.9  3806.9    3964  3976.9  4016.9  4053.2  4327.1  4417.1
  4442.1  4462.1  4472.1  4497.1  4537.1  4547.1  4557.1  4560.8  4590.8  4605.8
  4640.8  4650.8    4668    4678  4680.8  4695.8  4715.8    4738  4745.1  4751.5
  4792.1    4887  4914.6  4924.1  4928.3  4931.6  4937.4  5046.6  5054.6  5093.8
    5097  5109.1    5164  5218.9  5254.7  5298.2  5379.7  5484.7  5499.7  5514.7
  5529.7  5759.7  5814.7  5829.7  5979.5  6062.8  6157.8  6187.8  6202.8  6288.2
   38.88   37.85   37.34   37.87   37.71   37.67   37.55   37.44    36.6   36.33
   36.25   36.18   36.42   36.32    35.9   35.87   35.83   35.82   35.95   35.72
   35.43   35.38   35.54   35.22   34.94   34.52   34.88   34.39   34.94   35.14
   35.16   34.45   34.63   34.93   35.07   35.15   35.11   34.36   34.31   34.26
   34.12   34.06   34.25   34.36   34.37   34.37   34.77   35.29   35.36   35.43
   35.51   36.63    36.9   36.98   37.79   37.48   38.01   37.93   38.53   38.71
   38.88   37.85   37.34   37.87   37.04   36.97    37.4    37.1   36.53   35.98
   34.83   35.79   36.41   36.31   33.97   34.62   34.01   34.04   35.94   35.71
   33.52   33.35   34.32   34.76   34.85   34.37   34.87   34.38   34.38   35.13
   35.15   34.42   33.94   33.78   34.01   33.85   32.31   31.56   34.06   34.25
   33.66   33.62   33.45   34.04   33.71   33.97   34.47   34.45   34.09   34.27
   34.85   36.45   36.64   36.96   37.78   37.48   38.01   37.93   38.53   38.71
  3551.9  3726.9  3751.9  3806.9    3964  3976.9  4016.9  4053.2  4327.1  4417.1
  4442.1  4462.1  4472.1  4497.1  4537.1  4547.1  4557.1  4560.8  4590.8  4605.8
  4640.8  4650.8    4668    4678  4680.8  4695.8  4715.8    4738  4745.1  4751.5
  4792.1    4887  4914.6  4924.1  4928.3  4931.6  4937.4  5046.6  5054.6  5093.8
    5097  5109.1    5164  5218.9  5254.7  5298.2  5379.7  5484.7  5499.7  5514.7
  5529.7  5759.7  5814.7  5829.7  5979.5  6062.8  6157.8  6187.8  6202.8  6288.2
   38.88   37.85   37.34   37.87   37.71   37.67   37.55   37.44    36.6   36.33
   36.25   36.18   36.42   36.32    35.9   35.87   35.83   35.82   35.95   35.72
   35.43   35.38   35.54   35.22   34.94   34.52   34.88   34.39   34.94   35.14
   35.16   34.45   34.63   34.93   35.07   35.15   35.11   34.36   34.31   34.26
   34.12   34.06   34.25   34.36   34.37   34.37   34.77   35.29   35.36   35.43
   35.51   36.63    36.9   36.98   37.79   37.48   38.01   37.93   38.53   38.71
   38.78   37.75   37.24   37.77   36.94   36.87    37.3      37   36.43   35.88
   34.73   35.69   36.31   36.21   33.87   34.52   33.91   33.94   35.84   35.61
   33.42   33.25   34.22   34.66   34.75   34.27   34.77   34.28   34.28   35.03
   35.05   34.32   33.84   33.68   33.91   33.75   32.21   31.46   33.96   34.15
   33.56   33.52   33.35   33.94   33.61   33.87   34.37   34.35   33.99   34.17
   34.75   36.35   36.54   36.86   37.68   37.38   37.91   37.83   38.43   38.61
Pier Skew, UpSta & Num, DnSta & Num=  ,4970.8, 2 ,4970.8, 2 , 0 , 0 , 0 ,,
       2       2
      20   33.09
       2       2
    19.9   32.99
Pier Skew, UpSta & Num, DnSta & Num=  ,5010.7, 2 ,5010.7, 2 , 0 , 0 , 0 ,,
       2       2
   14.23   32.82
       2       2
   14.13   32.72
Abutment Skew #Up #Dn= , 2 , 2
  4930.9  4958.1
   33.87   24.76
  4930.9  4958.1
   33.77   24.66
Abutment Skew #Up #Dn= , 2 , 2
    5024 5054.19
   23.82   33.78
    5024 5054.19
   23.72   33.68
BR Coef= 1 , 1 , 0 ,1.25, 0 ,,,0.8,0,2,0,
WSPro=,,,, 1 ,,,, 0 ,,,, 0 ,,,,-1 ,-1 ,-1 , 0 , 0 , 0 , 0 , 0
BR U #Sta/Elev= 107
  3551.9   38.88  3726.9   37.85  3751.9   37.34  3806.9   37.87    3964   37.04
  3976.9   36.97  4016.9    37.4  4053.2    37.1  4064.1   37.08  4227.1   36.74
  4327.1   36.53  4417.1   35.98  4442.1   34.83  4443.1   34.88  4462.1   35.79
    4470   36.28  4472.1   36.41  4497.1   36.31  4537.1   33.97  4547.1   34.62
  4552.1   34.45  4557.1   34.01  4560.8   34.04    4573   34.81  4590.8   35.94
  4605.8   35.71  4640.8   33.52  4650.8   33.35    4658   33.67  4660.8   33.79
    4668   34.32  4670.8   34.52    4678   34.76  4680.8   34.85    4683   34.78
  4695.8   34.37    4713    34.8  4715.8   34.87  4717.3   34.84    4723   34.67
  4732.3   34.38    4738   34.38  4744.2   34.38  4745.1   34.38  4751.5   35.13
  4792.1   35.15    4798    35.1  4838.4   34.77  4847.1   34.71    4887   34.42
  4894.6   34.29  4914.6   33.94  4924.1   33.78  4928.3   34.01  4930.9   33.88
 4931.01   33.88  4931.1   33.87  4931.6   33.85  4937.4   32.05    4958   24.79
  4958.1   24.76  4970.8   20.68  4973.2   22.02  4985.3   16.91  4988.9   15.99
  4997.3   15.78  5005.8      11  5010.7   16.31  5014.7   16.92  5023.9   23.79
    5024   23.82  5036.6   27.67  5046.6    30.4 5053.99   33.78  5054.1   33.83
  5054.2   33.88  5054.6   34.06  5058.4   34.02  5093.8   34.25    5097   33.66
  5109.1   33.62    5164   33.45  5168.3   33.49    5208   33.83  5218.9   34.04
  5226.4      34  5250.3   33.86  5254.7   33.71  5298.2   33.97  5379.7   34.47
  5472.1   34.45  5484.7   34.45  5499.7   34.09  5514.7   34.27  5529.7   34.85
  5689.7   35.93  5739.7   36.19  5759.7   36.45  5814.7   36.64  5829.7   36.96
  5979.5   37.78    5981   37.77  6062.8   37.48  6157.8   38.01  6187.8   37.93
  6202.8   38.53  6288.2   38.71
BR U #Mann= 9
  3551.9      .2  3551.9     .14  4064.1      .1  4227.1     .14    4470     .12
  4928.3     .04  5054.6     .12  5472.1      .1  6288.2      .2
BR U Banks=4928.3,5054.6
BR D #Sta/Elev= 107
  3551.9   38.78  3726.9   37.75  3751.9   37.24  3806.9   37.77    3964   36.94
  3976.9   36.87  4016.9    37.3  4053.2      37  4064.1   36.98  4227.1   36.64
  4327.1   36.43  4417.1   35.88  4442.1   34.73  4443.1   34.78  4462.1   35.69
    4470   36.18  4472.1   36.31  4497.1   36.21  4537.1   33.87  4547.1   34.52
  4552.1   34.35  4557.1   33.91  4560.8   33.94    4573   34.71  4590.8   35.84
  4605.8   35.61  4640.8   33.42  4650.8   33.25    4658   33.57  4660.8   33.69
    4668   34.22  4670.8   34.42    4678   34.66  4680.8   34.75    4683   34.68
  4695.8   34.27    4713    34.7  4715.8   34.77  4717.3   34.74    4723   34.57
  4732.3   34.28    4738   34.28  4744.2   34.28  4745.1   34.28  4751.5   35.03
  4792.1   35.05    4798      35  4838.4   34.67  4847.1   34.61    4887   34.32
  4894.6   34.19  4914.6   33.84  4924.1   33.68  4928.3   33.91  4930.9   33.78
 4931.01   33.78  4931.1   33.77  4931.6   33.75  4937.4   31.95    4958   24.69
  4958.1   24.66  4970.8   20.58  4973.2   21.92  4985.3   16.81  4988.9   15.89
  4997.3   15.68  5005.8    10.9  5010.7   16.21  5014.7   16.82  5023.9   23.69
    5024   23.72  5036.6   27.57  5046.6    30.3 5053.99   33.68  5054.1   33.73
  5054.2   33.78  5054.6   33.96  5058.4   33.92  5093.8   34.15    5097   33.56
  5109.1   33.52    5164   33.35  5168.3   33.39    5208   33.73  5218.9   33.94
  5226.4    33.9  5250.3   33.76  5254.7   33.61  5298.2   33.87  5379.7   34.37
  5472.1   34.35  5484.7   34.35  5499.7   33.99  5514.7   34.17  5529.7   34.75
  5689.7   35.83  5739.7   36.09  5759.7   36.35  5814.7   36.54  5829.7   36.86
  5979.5   37.68    5981   37.67  6062.8   37.38  6157.8   37.91  6187.8   37.83
  6202.8   38.43  6288.2   38.61
BR D #Mann= 9
  3551.9      .2  3551.9     .14  4064.1      .1  4227.1     .14    4470     .12
  4928.3     .04  5054.6     .12  5472.1      .1  6288.2      .2
BR D Banks=4928.3,5054.6
BC Design=,, 0 ,, 0 ,,,,,,
BC HTab HWMax=38.92
BC Use User HTab Curves=0
BC User HTab FreeFlow(D)= 0

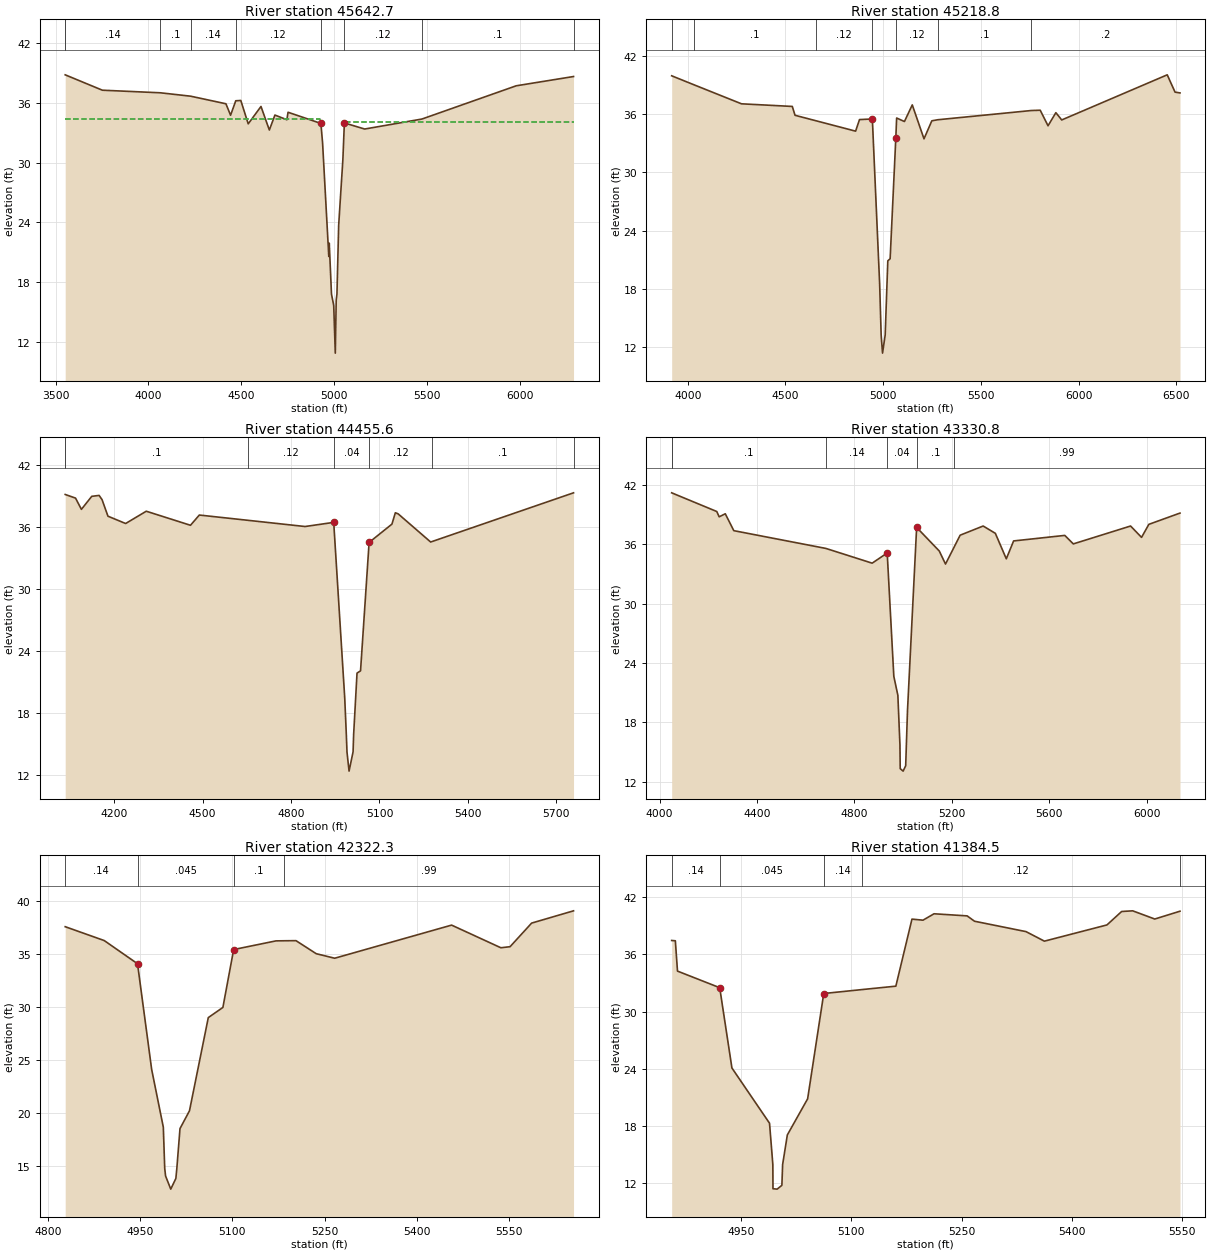
Type RM Length L Ch R = 1 ,45642.7 ,423.9,423.9,423.9
BEGIN DESCRIPTION:
Downstream Section of Bridge/Culvert/Weir
END DESCRIPTION:
XS GIS Cut Line= 6
      3152676.41     13857308.45      3152712.43     13856417.97
      3153091.45     13855807.02      3153133.59     13855056.03
      3153115.27     13854876.81      3153042.22     13854698.24
#Sta/Elev= 30
  3551.9   38.79  3751.9   37.25  4064.1   36.99  4227.1   36.65  4417.1   35.89
  4442.1   34.74    4470   36.19  4497.1   36.22  4537.1   33.88  4605.8   35.62
  4650.8   33.26  4680.8   34.76  4745.1   34.29  4751.5   35.04  4928.3   33.92
  4937.4   31.96  4970.8   20.59  4973.2   21.93  4985.3   16.82  4997.3   15.69
  5005.8   10.91  5010.7   16.22  5014.7   16.83  5023.9    23.7  5046.6   30.31
  5054.6   33.97    5164   33.36  5472.1   34.36  5979.5   37.69  6288.2   38.62
#Mann= 9 , 1 , 0
  3551.9      .2       0  3551.9     .14       0  4064.1      .1       0
  4227.1     .14       0    4470     .12       0  4928.3     .04       0
  5054.6     .12       0  5472.1      .1       0  6288.2      .2       0
#XS Ineff= 2 , 0
       0 4921.63   34.39 5061.27       0   34.06
Permanent Ineff=
       F       F
Bank Sta=4928.3,5054.6
XS Rating Curve= 0 ,0
Exp/Cntr=0.5,0.3

Type RM Length L Ch R = 1 ,45218.8 ,807,763.2,690.4
BEGIN DESCRIPTION:
Cross Section 45218.8
END DESCRIPTION:
XS GIS Cut Line= 5
      3152741.62     13857220.86      3152815.23     13856871.23
      3152918.27     13856617.29      3153595.45     13855958.51
      3154316.79     13855229.81
#Sta/Elev= 30
  3917.8   39.93  4033.9   38.99  4275.1   37.05  4535.1   36.78  4549.1   35.87
    4654   35.32  4859.1   34.24  4879.1   35.43  4944.8   35.49  4982.2    18.5
  4989.9   13.26  4996.9   11.42  5010.5   13.29  5023.9   20.91  5035.8   21.12
  5064.9   33.55  5069.1   35.59  5109.1   35.23  5149.1   36.94  5209.1   33.45
  5249.1    35.3  5278.8   35.41  5758.4   36.36  5803.9   36.39  5843.9   34.79
  5883.9   36.14  5913.9   35.39  6453.9   40.03  6493.9   38.25  6519.2   38.17
#Mann= 7 , 1 , 0
  3917.8      .2       0  4033.9      .1       0    4654     .12       0
  4944.8     .04       0  5064.9     .12       0  5278.8      .1       0
  5758.4      .2       0
Bank Sta=4944.8,5064.9
XS Rating Curve= 0 ,0
Exp/Cntr=0.3,0.1

Type RM Length L Ch R = 1 ,44455.6 ,1073.3,1124.8,1161.8
BEGIN DESCRIPTION:
Cross Section 44455.6
END DESCRIPTION:
XS GIS Cut Line= 3
      3153377.27     13857527.99      3153953.89     13856556.47
      3154404.71     13856168.56
#Sta/Elev= 29
  4033.9   39.11  4068.9   38.76  4088.9   37.67  4123.9   38.93  4148.9   39.02
  4158.9   38.61  4178.9   37.01  4238.9    36.3  4308.9   37.49  4458.9   36.13
  4488.9   37.12    4654   36.61  4847.5   36.01  4944.8   36.41  4982.2   19.42
  4987.7   15.81  4989.9   14.18  4996.9   12.34  5010.5   14.21  5012.4   15.87
  5023.9   21.83  5035.8   22.04  5064.9   34.47  5142.3   36.24  5153.9   37.34
  5163.7   37.23  5273.7   34.51  5278.8   34.56  5758.4   39.27
#Mann= 7 , 1 , 0
  4033.9      .2       0  4033.9      .1       0    4654     .12       0
  4944.8     .04       0  5064.9     .12       0  5278.8      .1       0
  5758.4      .2       0
Bank Sta=4944.8,5064.9
XS Rating Curve= 0 ,0
Exp/Cntr=0.3,0.1

Type RM Length L Ch R = 1 ,43330.8 ,997.5,1008.5,993.2
BEGIN DESCRIPTION:
Cross Section 43330.8
END DESCRIPTION:
XS GIS Cut Line= 5
      3153934.96     13858013.86      3154322.54     13857728.74
      3154683.39     13857439.17      3154932.87     13857216.42
      3154981.87     13856410.08
#Sta/Elev= 30
  4049.9   41.23  4234.9   39.34  4244.9    38.8  4269.9   39.11  4304.9    37.4
  4683.1    35.6  4872.7   34.11  4934.4   35.14  4961.6   22.65  4978.2   20.73
  4986.7   15.71  4987.8   13.31  4999.8   13.06  5010.3   13.61  5017.6   19.14
  5055.2   37.73  5148.1   35.34  5173.7   34.02  5208.7   35.72  5233.7   36.94
  5328.2   37.87  5378.2   37.13  5423.2   34.55  5453.2   36.36  5663.2   36.92
  5698.2   36.06  5933.2   37.87  5978.2   36.72  6008.2   38.04    6136   39.18
#Mann= 6 , 1 , 0
  4049.9      .2       0  4049.9      .1       0  4683.1     .14       0
  4934.4     .04       0  5055.2      .1       0  5208.7     .99       0
Bank Sta=4934.4,5055.2
XS Rating Curve= 0 ,0
Exp/Cntr=0.3,0.1

Type RM Length L Ch R = 1 ,42322.3 ,1055.6,937.8,773.8
BEGIN DESCRIPTION:
Cross Section 42322.3
END DESCRIPTION:
XS GIS Cut Line= 3
      3155230.66     13858261.47      3155540.49     13857996.28
      3155704.74     13857611.87
#Sta/Elev= 25
  4828.4   37.57  4891.8   36.26  4945.9   34.07  4968.9   24.07  4987.8   18.63
  4990.1   14.72  4991.5   14.01  4999.9   12.77  5008.2   13.78  5009.8   14.75
  5014.9   18.49  5030.3   20.17  5060.9   28.98  5084.6   29.94  5102.1   35.41
  5170.9   36.23  5184.3   36.24  5203.4   36.25  5236.2   35.02  5266.2   34.59
  5456.2   37.72  5536.2   35.58  5551.2   35.68  5586.2   37.91  5654.3   39.07
#Mann= 4 , 1 , 0
  4828.4     .14       0  4945.9    .045       0  5102.1      .1       0
  5184.3     .99       0
Bank Sta=4945.9,5102.1
XS Rating Curve= 0 ,0
Exp/Cntr=0.3,0.1

Type RM Length L Ch R = 1 ,41384.5 ,1137.3,1068.3,972.8
BEGIN DESCRIPTION:
Cross Section 41384.5
END DESCRIPTION:
XS GIS Cut Line= 3
      3156154.39     13858699.66       3156120.6     13858625.33
      3156082.16     13858017.25
#Sta/Elev= 28
  4855.8   37.45  4860.8   37.42  4863.7   34.24  4921.1    32.5  4937.7   24.08
  4988.8   18.29  4993.3   13.96  4993.5   11.42  4999.2   11.38  5005.6   11.78
  5006.6   13.95    5013   17.06  5040.6   20.85  5062.5   31.89  5114.1    32.3
  5160.5   32.66  5182.4   39.69  5197.4   39.58  5212.4   40.25  5257.4   40.03
  5267.4   39.47  5337.4   38.38  5362.4   37.38  5447.4   39.08  5467.4   40.49
  5482.4   40.56  5512.4    39.7  5546.7   40.52
#Mann= 5 , 1 , 0
  4855.8     .14       0  4921.1    .045       0  5062.5     .14       0
  5114.1     .12       0  5546.7      .2       0
Bank Sta=4921.1,5062.5
XS Rating Curve= 0 ,0
Exp/Cntr=0.3,0.1