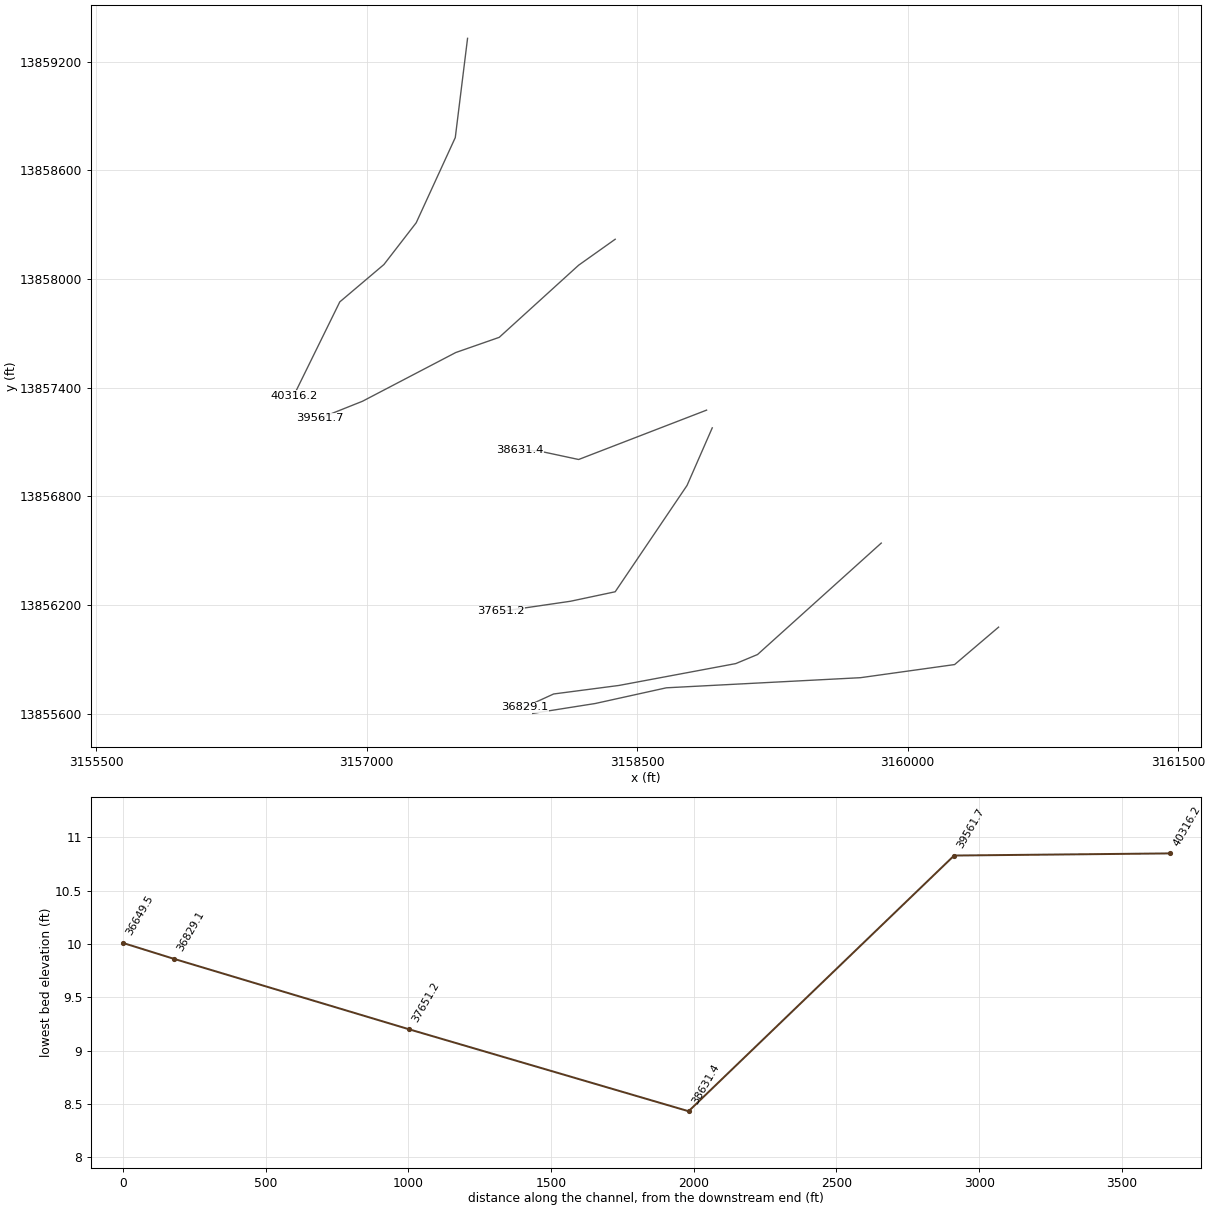
HEC-RAS study H100-00-00.prj: H100-00-00

--- H100-00-00.g01 (geometry) --- (continued)

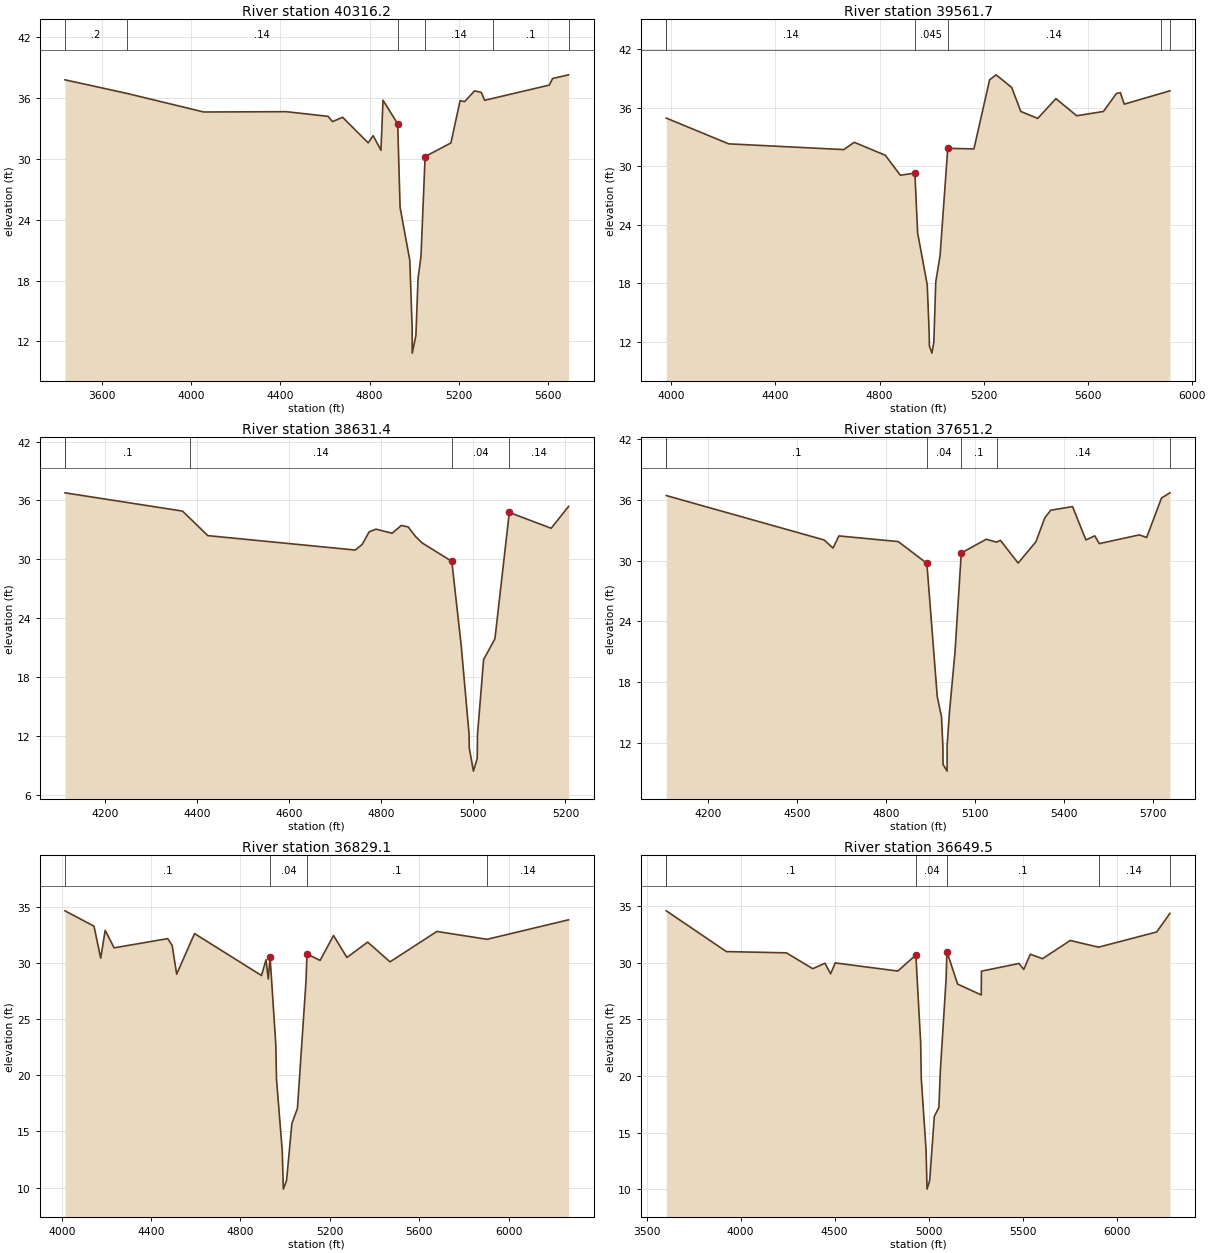
Type RM Length L Ch R = 1 ,40316.2 ,836.7,754.5,693.9
BEGIN DESCRIPTION:
Cross Section 40316.2
END DESCRIPTION:
XS GIS Cut Line= 6
      3157559.56     13859329.37       3157491.5     13858781.34
      3157274.79     13858310.95      3157095.62     13858080.16
        3156851.     13857873.97      3156595.88     13857356.75
#Sta/Elev= 30
    3434   37.77  3711.7   36.43  4056.2    34.6  4426.2   34.63  4614.1   34.17
  4634.1   33.65  4679.1   34.08  4794.1   31.56  4816.3   32.27  4851.3   30.83
  4860.5   35.76  4926.3   33.44  4937.1    25.2  4980.6      20  4991.2   13.29
  4991.5   10.85    5008   12.58  5017.6    18.2  5030.8   20.38  5049.3   30.21
  5165.1   31.55  5206.3   35.72  5226.3   35.62  5271.3   36.68  5301.3   36.53
  5316.3   35.75    5353   35.94  5606.3   37.25  5621.3    37.9    5693   38.26
#Mann= 6 , 1 , 0
    3434      .2       0  3711.7     .14       0  4926.3    .045       0
  5049.3     .14       0    5353      .1       0    5693      .2       0
Bank Sta=4926.3,5049.3
XS Rating Curve= 0 ,0
Exp/Cntr=0.3,0.1

Type RM Length L Ch R = 1 ,39561.7 ,869.8,930.3,792.5
BEGIN DESCRIPTION:
Cross Section 39561.7
END DESCRIPTION:
XS GIS Cut Line= 6
      3158378.18     13858219.94      3158175.49     13858076.66
      3157735.15     13857678.27      3157494.02     13857594.39
       3156976.8      13857325.3      3156739.17     13857230.94
#Sta/Elev= 30
  3980.2   34.94  4220.2    32.3  4662.7   31.71  4702.7   32.46  4822.2   31.13
  4880.1   29.08  4935.9    29.3  4946.5   23.17  4983.5   17.82  4990.9    12.9
  4991.7   11.56  5001.5   10.83  5008.7   11.95  5016.2   18.14  5032.7   20.83
  5062.3   31.84  5162.9   31.78  5223.2   38.87  5248.2   39.38  5308.2   38.08
  5343.2   35.62  5408.2   34.91  5478.2   36.94  5558.2   35.18  5660.8   35.62
  5710.8   37.47  5725.8   37.55  5740.8   36.37  5880.5   37.46  5916.5   37.74
#Mann= 6 , 1 , 0
  3980.2      .2       0  3980.2     .14       0  4935.9    .045       0
  5062.3     .14       0  5880.5      .1       0  5916.5      .2       0
Bank Sta=4935.9,5062.3
XS Rating Curve= 0 ,0
Exp/Cntr=0.3,0.1

Type RM Length L Ch R = 1 ,38631.4 ,705.2,980.2,995.3
BEGIN DESCRIPTION:
Cross Section 38631.4
END DESCRIPTION:
XS GIS Cut Line= 4
      3158884.91     13857276.38      3158175.49     13857003.79
      3157962.31     13857049.22      3157847.63     13857058.47
#Sta/Elev= 25
  4113.9   36.78  4368.9   34.92  4385.5   34.17  4423.9   32.42  4743.9   30.95
  4758.9   31.52  4773.9    32.8  4788.9   33.08  4823.9   32.66  4843.9   33.46
  4858.9    33.3  4873.9   32.37  4888.9   31.68  4953.4    29.8  4973.7   21.26
  4990.9   12.17  4991.3   10.79  5000.3    8.43  5008.5    9.71  5009.1   12.13
  5022.4   19.79    5047   21.91  5078.2   34.78    5169   33.17  5206.9    35.4
#Mann= 5 , 1 , 0
  4113.9      .2       0  4113.9      .1       0  4385.5     .14       0
  4953.4     .04       0  5078.2     .14       0
Bank Sta=4953.4,5078.2
XS Rating Curve= 0 ,0
Exp/Cntr=0.3,0.1

Type RM Length L Ch R = 1 ,37651.2 ,926.1,822.1,656.7
BEGIN DESCRIPTION:
Cross Section 37651.2
END DESCRIPTION:
XS GIS Cut Line= 5
      3158916.36     13857178.52      3158776.57     13856860.51
      3158378.18      13856273.4      3158130.05     13856220.98
      3157745.64     13856165.06
#Sta/Elev= 30
  4059.8   36.44  4592.2   32.05  4622.2   31.25  4642.2   32.45  4842.2   31.89
  4938.8   29.74  4973.9   16.55    4988    14.6  4992.8   11.71  4993.5    9.86
  5006.9     9.2  5007.1   11.71  5014.9   14.99  5033.8      21  5054.9   30.76
  5139.1   32.12    5174   31.83  5186.7   32.02  5246.7   29.77  5306.7   31.87
  5336.7   34.24  5356.7   34.99  5430.3   35.35  5475.3   32.05  5505.3   32.46
  5520.3   31.69  5655.3   32.55  5680.3    32.3  5730.3    36.2  5758.8   36.71
#Mann= 6 , 1 , 0
  4059.8      .2       0  4059.8      .1       0  4938.8     .04       0
  5054.9      .1       0    5174     .14       0  5758.8      .2       0
Bank Sta=4938.8,5054.9
XS Rating Curve= 0 ,0
Exp/Cntr=0.3,0.1

Type RM Length L Ch R = 1 ,36829.1 ,409.7,179.6,93.2
BEGIN DESCRIPTION:
Cross Section Cross Section 36829.1-Interpolated
END DESCRIPTION:
XS GIS Cut Line= 6
      3159853.45     13856542.21      3159167.44     13855926.86
      3159046.73     13855876.81      3158398.99      13855756.1
      3158036.85     13855708.99      3157874.92     13855635.38
#Sta/Elev= 30
  4014.3   34.68  4144.3   33.31  4174.3   30.46  4194.3   32.94  4234.3   31.38
  4474.3    32.2  4494.3   31.58  4514.3   29.03  4594.3   32.65  4894.3   28.91
  4914.3   30.32  4924.3    28.6  4932.5   30.54    4958    22.8  4961.3   19.64
  4986.8   13.32  4991.9    9.86  5006.3   10.64    5030   15.71    5055   17.07
  5093.3   28.41  5097.8   30.83  5156.5   30.26  5216.5   32.48  5276.5   30.52
  5369.3   31.89  5469.3   30.13  5679.3   32.84  5904.1   32.14  6268.9   33.88
#Mann= 4 , 1 , 0
  4014.3      .1       0  4932.5     .04       0  5097.8      .1       0
  5904.1     .14       0
Bank Sta=4932.5,5097.8
XS Rating Curve= 0 ,0
Exp/Cntr=0.5,0.3

Type RM Length L Ch R = 1 ,36649.5 ,100,100,100
BEGIN DESCRIPTION:
Upstream Section of Bridge/Culvert/Weir
END DESCRIPTION:
XS GIS Cut Line= 6
      3160504.07      13856078.1      3160260.18     13855871.42
      3159738.45       13855799.      3158662.08     13855743.09
      3158267.96     13855656.46      3157920.87     13855601.89
#Sta/Elev= 30
  3604.9   34.59  3924.6   30.99  4243.9   30.88  4383.9   29.48  4448.9   29.96
  4478.9   29.03  4503.9   29.99  4836.3   29.27  4932.5   30.69    4958   22.95
  4961.3   19.79  4986.8   13.47  4991.9   10.01  5006.3   10.79  5030.4   16.42
  5054.9   17.22  5062.7   20.45  5093.3   28.56  5097.8   30.98  5154.6   28.12
  5280.3   27.16  5281.3   29.26  5481.4   29.94  5506.4   29.41  5541.4   30.76
  5606.4   30.36  5753.4   31.97  5904.1   31.38  6213.4   32.72  6284.1   34.37
#Mann= 6 , 1 , 0
  3604.9      .2       0  3604.9      .1       0  4932.5     .04       0
  5097.8      .1       0  5904.1     .14       0  6284.1      .2       0
#XS Ineff= 2 , 0
       0  4922.5   30.54  5107.8       0   29.64
Permanent Ineff=
       F       F
Bank Sta=4932.5,5097.8
XS Rating Curve= 0 ,0
Exp/Cntr=0.5,0.3