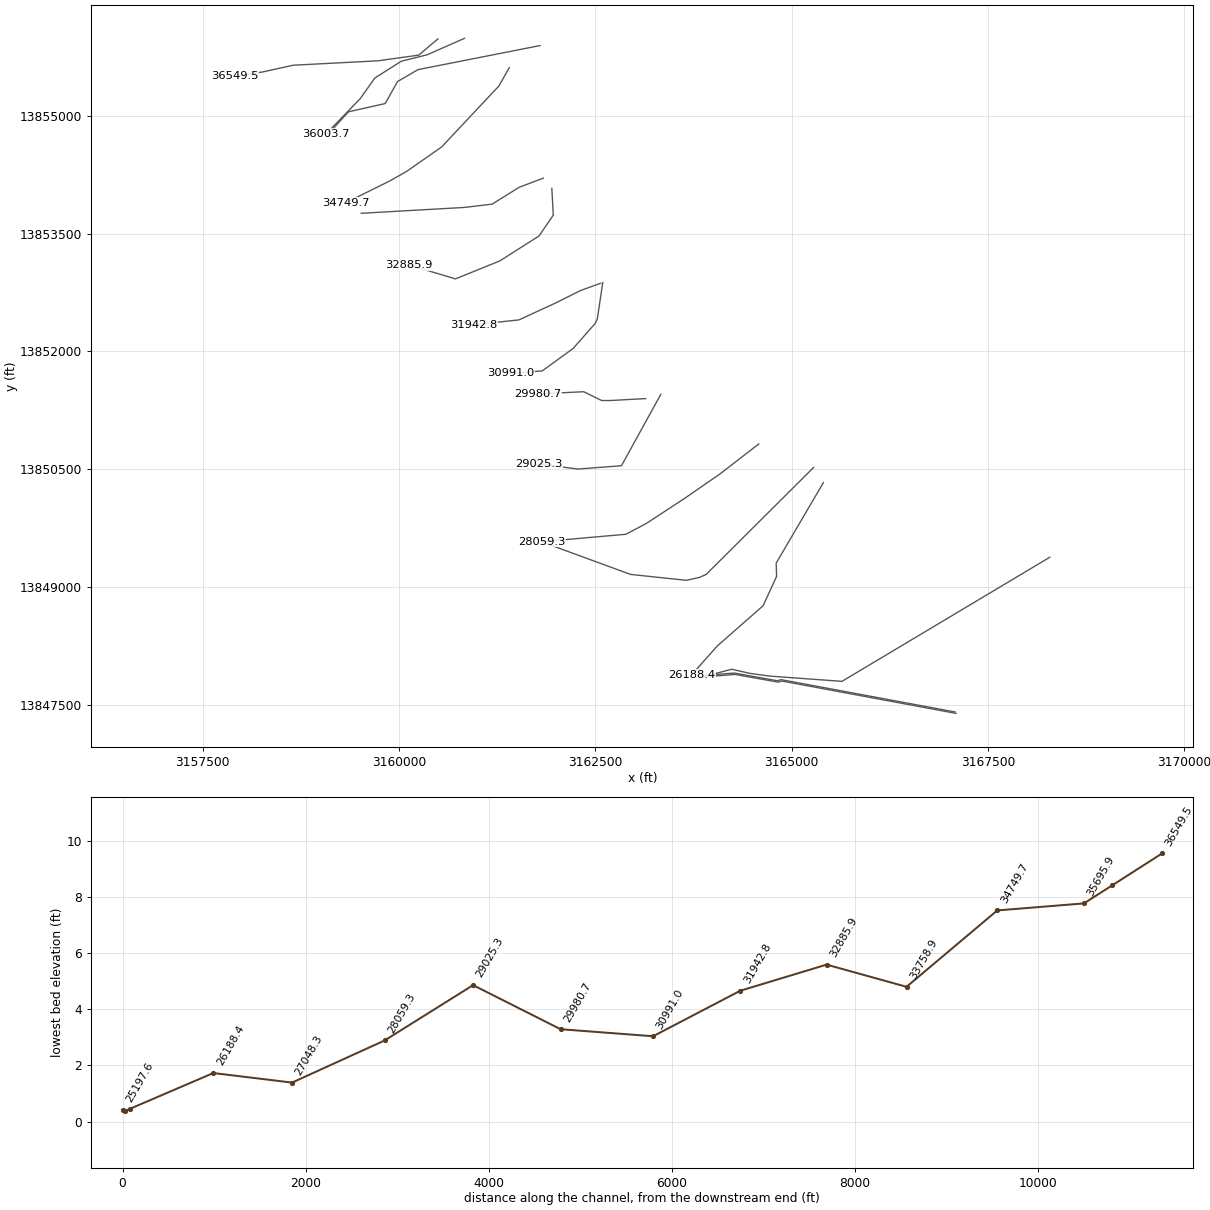
HEC-RAS study H100-00-00.prj: H100-00-00

--- H100-00-00.g01 (geometry) --- (continued)

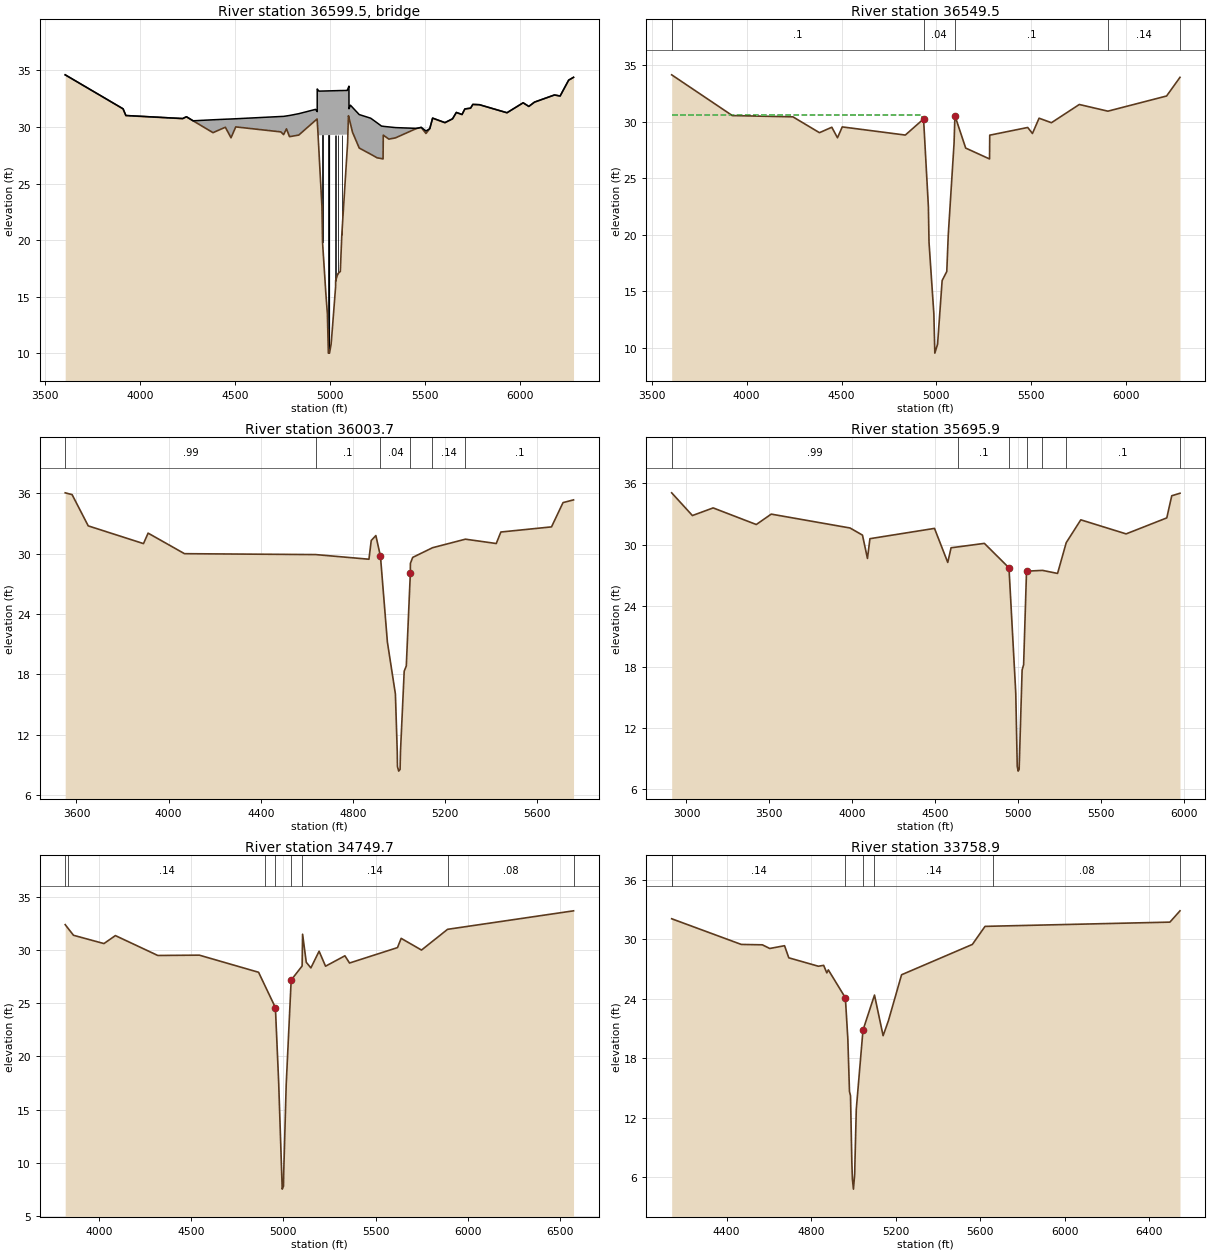
Type RM Length L Ch R = 3 ,36599.5 ,,,
BEGIN DESCRIPTION:
WALLISVILLE ROAD
Structure ID: H00-22
END DESCRIPTION:
Bridge Culvert--1,0,-1,-1, 0
Deck Dist Width WeirC Skew NumUp NumDn MinLoCord MaxHiCord MaxSubmerge Is_Ogee
10,80,2.6,0, 60, 60, , , 0.95, 0, 1,1,,
  3604.9  3909.9  3924.6  4223.9  4243.9  4278.9  4383.9  4448.9  4478.9  4503.9
  4741.1  4756.1  4771.1    4787  4836.3  4924.4  4932.5 4933.09  4933.2    4937
 4941.81  4941.9  5054.9 5091.29  5091.4  5093.3  5097.8  5100.5 5100.61  5108.2
  5119.3  5154.6  5214.9  5248.8  5272.3  5280.3  5281.3  5310.9  5345.6  5456.4
  5481.4  5506.4  5526.4  5541.4  5606.4  5646.4  5666.4  5696.4  5711.4  5741.4
  5753.4  5788.4  5933.4  6018.4  6048.4  6078.4  6183.4  6213.4  6258.4  6284.1
    34.6    31.6   31.01   30.74    30.9   30.54   30.63   30.68    30.7   30.72
   30.92   30.93   30.97   31.01   31.17   31.55   31.36   31.35   33.35   33.27
   33.16   33.16   33.21   33.22   33.22    33.3   33.49    33.6    31.6   31.92
   31.72   31.09   30.77   30.36   30.07   30.06   30.05      30   29.94   29.87
   29.96   29.64   29.85   30.78   30.38   30.72   31.28    31.1   31.59   31.66
   31.99   31.96   31.25   32.13   31.81   32.19   32.82   32.73   34.13   34.38
    34.6   31.59      31   30.73   30.89   30.54   29.49   29.97   29.04      30
   29.56   29.32   29.83   29.14   29.28   30.58    30.7   30.54   30.51   29.51
   28.01   29.26   29.31   29.32   28.07   28.57   30.99   30.81    30.8   30.28
   29.52   28.13   27.59   27.27    27.2   27.17   29.27   28.92   29.03   29.86
   29.95   29.42   29.84   30.77   30.37   30.71   31.27   31.09   31.58   31.65
   31.98   31.96   31.25   32.13   31.81   32.19   32.82   32.73   34.13   34.38
  3604.9  3909.9  3924.6  4223.9  4243.9  4278.9  4383.9  4448.9  4478.9  4503.9
  4741.1  4756.1  4771.1    4787  4836.3  4924.4  4932.5 4933.09  4933.2    4937
 4941.81  4941.9  5054.9 5091.29  5091.4  5093.3  5097.8  5100.5 5100.61  5108.2
  5119.3  5154.6  5214.9  5248.8  5272.3  5280.3  5281.3  5310.9  5345.6  5456.4
  5481.4  5506.4  5526.4  5541.4  5606.4  5646.4  5666.4  5696.4  5711.4  5741.4
  5753.4  5788.4  5933.4  6018.4  6048.4  6078.4  6183.4  6213.4  6258.4  6284.1
    34.6    31.6   31.01   30.74    30.9   30.54   30.63   30.68    30.7   30.72
   30.92   30.93   30.97   31.01   31.17   31.55   31.36   31.35   33.35   33.27
   33.16   33.16   33.21   33.22   33.22    33.3   33.49    33.6    31.6   31.92
   31.72   31.09   30.77   30.36   30.07   30.06   30.05      30   29.94   29.87
   29.96   29.64   29.85   30.78   30.38   30.72   31.28    31.1   31.59   31.66
   31.99   31.96   31.25   32.13   31.81   32.19   32.82   32.73   34.13   34.38
   34.14   31.13   30.54   30.27   30.43   30.08   29.03   29.51   28.58   29.54
    29.1   28.86   29.37   28.68   28.82   30.12   30.24   30.08   30.05   29.05
   27.55    28.8   28.85   28.86   27.61   28.11   30.53   30.35   30.34   29.82
   29.06   27.67   27.13   26.81   26.74   26.71   28.81   28.46   28.57    29.4
   29.49   28.96   29.38   30.31   29.91   30.25   30.81   30.63   31.12   31.19
   31.52    31.5   30.79   31.67   31.35   31.73   32.36   32.27   33.67   33.92
Pier Skew, UpSta & Num, DnSta & Num=  ,4961.3, 2 ,4961.3, 2 , 0 , 0 , 0 ,,
     1.4     1.4
   18.62   30.27
     1.4     1.4
   18.16   29.81
Pier Skew, UpSta & Num, DnSta & Num=  ,4991.9, 2 ,4991.9, 2 , 0 , 0 , 0 ,,
       2       2
    9.02   30.28
       2       2
    8.56   29.82
Pier Skew, UpSta & Num, DnSta & Num=  ,4994.1, 2 ,4994.1, 2 , 0 , 0 , 0 ,,
     1.2     1.2
    9.02   30.28
     1.2     1.2
    8.56   29.82
Pier Skew, UpSta & Num, DnSta & Num=  ,4996.3, 2 ,4996.3, 2 , 0 , 0 , 0 ,,
     1.3     1.3
    9.02   30.28
     1.3     1.3
    8.56   29.82
Pier Skew, UpSta & Num, DnSta & Num=  ,5028, 2 ,5028, 2 , 0 , 0 , 0 ,,
     1.4     1.4
   14.28    30.3
     1.4     1.4
   13.82   29.84
Pier Skew, UpSta & Num, DnSta & Num=  ,5030.4, 2 ,5030.4, 2 , 0 , 0 , 0 ,,
     1.6     1.6
   14.78    30.3
     1.6     1.6
   14.32   29.84
Pier Skew, UpSta & Num, DnSta & Num=  ,5042, 2 ,5042, 2 , 0 , 0 , 0 ,,
       2       2
   15.98    30.3
       2       2
   15.52   29.84
Pier Skew, UpSta & Num, DnSta & Num=  ,5062.7, 2 ,5062.7, 2 , 0 , 0 , 0 ,,
     1.4     1.4
   19.17   30.31
     1.4     1.4
   18.71   29.85
Abutment Skew #Up #Dn= , 2 , 2
  4941.7  4978.7
   29.26   15.29
  4941.7  4978.7
    28.8   14.83
Abutment Skew #Up #Dn= , 2 , 2
    5055 5091.49
   17.27   29.32
    5055 5091.49
   16.81   28.86
BR Coef= 1 , 1 , 0 ,1.25, 0 ,,,0.8,-1,2,0,
WSPro=,,,, 1 ,,,, 0 ,,,, 0 ,,,,-1 ,-1 ,-1 , 0 , 0 , 0 , 0 , 0
BR U #Sta/Elev= 88
  3604.9    34.6  3729.5   33.37  3909.9   31.59  3924.6      31  4223.9   30.73
  4243.9   30.89  4278.9   30.54  4383.9   29.49  4448.9   29.97  4478.9   29.04
  4503.9      30  4741.1   29.56  4756.1   29.32  4758.9   29.42  4771.1   29.83
    4787   29.14  4809.5    29.2  4836.3   29.28    4859   29.62  4924.4   30.58
  4932.5    30.7 4933.09   30.54  4933.2   30.51 4933.31   30.49    4937   29.51
  4941.7   28.04 4941.81   28.01  4941.9   27.98    4958   22.96  4961.3    19.8
  4978.6   15.32  4978.7   15.29  4986.8   13.48  4990.7   10.83  4991.9   10.02
    4998   10.02  5006.3    10.8  5013.2   12.22    5030   15.87  5030.4   16.43
    5042   17.03  5054.9   17.23    5055   17.27  5062.7   20.46 5091.29   28.04
  5091.4   28.07  5091.5   28.09  5093.3   28.57  5097.8   30.99 5100.39   30.81
  5100.5   30.81 5100.61    30.8  5108.2   30.28  5119.3   29.52  5154.6   28.13
  5155.9   28.12  5203.7   27.69  5214.9   27.59  5248.8   27.27  5272.3    27.2
  5280.3   27.17  5281.3   29.27  5310.9   28.92  5345.6   29.03  5456.4   29.86
  5481.4   29.95  5506.4   29.42  5526.4   29.84  5529.2   30.01  5541.4   30.77
  5606.4   30.37  5646.4   30.71  5666.4   31.27  5696.4   31.09  5711.4   31.58
  5741.4   31.65  5753.4   31.98  5772.7   31.97  5788.4   31.96  5904.1   31.39
  5933.4   31.25  6018.4   32.13  6048.4   31.81  6078.4   32.19  6183.4   32.82
  6213.4   32.73  6258.4   34.13  6284.1   34.38
BR U #Mann= 6
  3604.9      .2  3604.9      .1  4932.5     .04  5097.8      .1  5904.1     .14
  6284.1      .2
BR U Banks=4932.5,5097.8
BR D #Sta/Elev= 88
  3604.9   34.14  3729.5   32.91  3909.9   31.13  3924.6   30.54  4223.9   30.27
  4243.9   30.43  4278.9   30.08  4383.9   29.03  4448.9   29.51  4478.9   28.58
  4503.9   29.54  4741.1    29.1  4756.1   28.86  4758.9   28.96  4771.1   29.37
    4787   28.68  4809.5   28.74  4836.3   28.82    4859   29.16  4924.4   30.12
  4932.5   30.24 4933.09   30.08  4933.2   30.05 4933.31   30.03    4937   29.05
  4941.7   27.58 4941.81   27.55  4941.9   27.52    4958    22.5  4961.3   19.34
  4978.6   14.86  4978.7   14.83  4986.8   13.02  4990.7   10.37  4991.9    9.56
    4998    9.56  5006.3   10.34  5013.2   11.76    5030   15.41  5030.4   15.97
    5042   16.57  5054.9   16.77    5055   16.81  5062.7      20 5091.29   27.58
  5091.4   27.61  5091.5   27.63  5093.3   28.11  5097.8   30.53 5100.39   30.35
  5100.5   30.35 5100.61   30.34  5108.2   29.82  5119.3   29.06  5154.6   27.67
  5155.9   27.66  5203.7   27.23  5214.9   27.13  5248.8   26.81  5272.3   26.74
  5280.3   26.71  5281.3   28.81  5310.9   28.46  5345.6   28.57  5456.4    29.4
  5481.4   29.49  5506.4   28.96  5526.4   29.38  5529.2   29.55  5541.4   30.31
  5606.4   29.91  5646.4   30.25  5666.4   30.81  5696.4   30.63  5711.4   31.12
  5741.4   31.19  5753.4   31.52  5772.7   31.51  5788.4    31.5  5904.1   30.93
  5933.4   30.79  6018.4   31.67  6048.4   31.35  6078.4   31.73  6183.4   32.36
  6213.4   32.27  6258.4   33.67  6284.1   33.92
BR D #Mann= 6
  3604.9      .2  3604.9      .1  4932.5     .04  5097.8      .1  5904.1     .14
  6284.1      .2
BR D Banks=4932.5,5097.8
BC Design=,, 0 ,, 0 ,,,,,,
BC HTab HWMax=34.59
BC Use User HTab Curves=0
BC User HTab FreeFlow(D)= 0

Type RM Length L Ch R = 1 ,36549.5 ,545.8,545.8,545.8
BEGIN DESCRIPTION:
Downstream Section of Bridge/Culvert/Weir
END DESCRIPTION:
XS GIS Cut Line= 6
      3160495.41     13855978.48      3160251.52      13855771.8
      3159729.79     13855699.38      3158653.42     13855643.47
       3158259.3     13855556.84       3157912.2     13855502.27
#Sta/Elev= 30
  3604.9   34.13  3924.6   30.53  4243.9   30.42  4383.9   29.02  4448.9    29.5
  4478.9   28.57  4503.9   29.53  4836.3   28.81  4932.5   30.23    4958   22.49
  4961.3   19.33  4986.8   13.01  4991.9    9.55  5006.3   10.33  5030.4   15.96
  5054.9   16.76  5062.7   19.99  5093.3    28.1  5097.8   30.52  5154.6   27.66
  5280.3    26.7  5281.3    28.8  5481.4   29.48  5506.4   28.95  5541.4    30.3
  5606.4    29.9  5753.4   31.51  5904.1   30.92  6213.4   32.26  6284.1   33.91
#Mann= 6 , 1 , 0
  3604.9      .2       0  3604.9      .1       0  4932.5     .04       0
  5097.8      .1       0  5904.1     .14       0  6284.1      .2       0
#XS Ineff= 2 , 0
       0 4925.83   30.54 5104.47       0   29.64
Permanent Ineff=
       F       F
Bank Sta=4932.5,5097.8
XS Rating Curve= 0 ,0
Exp/Cntr=0.5,0.3

Type RM Length L Ch R = 1 ,36003.7 ,232.6,307.8,203.2
BEGIN DESCRIPTION:
Cross Section 36003.7
END DESCRIPTION:
XS GIS Cut Line= 6
      3160833.88     13855985.75      3160359.86     13855776.71
       3160030.1     13855694.27      3159691.52     13855479.34
      3159508.97     13855220.24      3159070.28     13854766.83
#Sta/Elev= 30
  3551.1   36.03  3581.1   35.85  3651.1   32.75  3891.1   30.99  3911.1   32.03
  4069.2   29.99  4639.1    29.9  4870.1   29.44  4880.1    31.3  4900.1   31.79
  4920.1   29.73  4950.1   21.24    4985   16.06    4993   10.33  4993.9    8.86
  4999.4    8.41  5005.3    8.58    5007   10.33  5023.2   18.33  5032.3   18.85
  5049.8   28.03  5050.1   29.03  5060.1   29.62    5146   30.58  5289.1   31.43
  5422.9      31  5442.9   32.14  5662.9   32.65  5712.9   35.06  5758.5   35.33
#Mann= 6 , 1 , 0
  3551.1     .99       0  4639.1      .1       0  4920.1     .04       0
  5049.8      .1       0    5146     .14       0  5289.1      .1       0
Bank Sta=4920.1,5049.8
XS Rating Curve= 0 ,0
Exp/Cntr=0.3,0.1

Type RM Length L Ch R = 1 ,35695.9 ,944.3,946.2,968.6
BEGIN DESCRIPTION:
Cross Section 35695.9
END DESCRIPTION:
XS GIS Cut Line= 6
      3161795.78     13855893.66      3160241.71     13855587.23
      3159982.21     13855435.46      3159824.75     13855155.53
      3159358.21     13855050.56      3159101.61     13854770.63
#Sta/Elev= 30
  2911.1   35.08  3036.1   32.85  3161.1    33.6  3421.1   31.97  3511.1   32.99
  3986.1   31.63  4061.1   30.93  4091.1   28.64  4106.1   30.58  4495.1   31.59
  4575.1   28.25  4595.1   29.69  4639.1   29.78  4795.7   30.12  4944.1   27.72
    4985   15.42  4993.9    8.22  4999.4    7.77  5005.3    7.94  5023.2   17.69
  5032.3   18.21  5049.8   27.39    5146   27.47  5236.9   27.17  5289.1   30.19
  5376.9   32.43  5650.1   31.05  5895.1   32.62  5925.1   34.79  5974.8   35.04
#Mann= 7 , 1 , 0
  2911.1     .99       0  4639.1      .1       0  4944.1     .04       0
  5049.8      .1       0    5146     .14       0  5289.1      .1       0
  5974.8      .2       0
Bank Sta=4944.1,5049.8
XS Rating Curve= 0 ,0
Exp/Cntr=0.3,0.1

Type RM Length L Ch R = 1 ,34749.7 ,1104.6,990.8,851.4
BEGIN DESCRIPTION:
Cross Section 34749.7
END DESCRIPTION:
XS GIS Cut Line= 6
      3161405.57     13855613.72      3161271.04     13855377.14
      3160542.07     13854601.51      3160098.85     13854292.42
      3159883.07     13854169.95      3159317.39     13853890.02
#Sta/Elev= 30
  3817.5    32.4  3831.7   32.08  3862.5    31.4  4027.5   30.62  4089.6   31.37
  4319.6    29.5  4544.6   29.53    4866   27.92  4901.6   26.62  4957.2    24.6
  4974.9   17.58  4994.2    7.52  5001.1     7.8    5002    8.85  5015.7   17.32
  5042.8   27.19  5102.1   28.51  5102.5   28.99  5104.6    31.5  5124.6   28.86
  5149.6   28.33  5194.1    29.9  5229.1   28.49  5334.1   29.47  5359.1   28.79
  5619.1   30.24  5639.1   31.11  5749.4   30.01  5890.8   31.96  6573.7    33.7
#Mann= 8 , 1 , 0
  3817.5      .1       0  3831.7     .14       0  4901.6      .1       0
  4957.2     .05       0  5042.8      .1       0  5102.5     .14       0
  5890.8     .08       0  6573.7      .2       0
Bank Sta=4957.2,5042.8
XS Rating Curve= 0 ,0
Exp/Cntr=0.3,0.1

Type RM Length L Ch R = 1 ,33758.9 ,678.5,873,833.3
BEGIN DESCRIPTION:
Cross Section 33758.9
END DESCRIPTION:
XS GIS Cut Line= 5
      3161839.06     13854206.11      3161531.14     13854089.47
       3161185.9     13853874.86      3160835.99     13853832.87
      3159520.33     13853758.22
#Sta/Elev= 30
  4139.9   32.08  4469.2   29.49  4569.2   29.45  4604.2   29.08  4674.2   29.36
  4694.2   28.14  4834.2   27.29  4859.2   27.38  4874.2   26.62  4881.4   26.92
    4962   24.11  4973.8   19.94  4981.5   14.65  4986.4   14.22  4992.7    7.51
  4995.4    5.79  5000.3     4.8  5006.2    6.33  5007.4    7.52  5013.7   12.86
  5045.4   20.84  5099.9   24.38  5140.7   20.28  5165.7   21.79  5228.1   26.43
  5563.1   29.49  5623.1   31.31  5659.2   31.33  6498.1   31.74  6545.9   32.88
#Mann= 7 , 1 , 0
  4139.9      .2       0  4139.9     .14       0    4962     .05       0
  5045.4      .1       0  5099.9     .14       0  5659.2     .08       0
  6545.9      .2       0
Bank Sta=4962,5045.4
XS Rating Curve= 0 ,0
Exp/Cntr=0.3,0.1

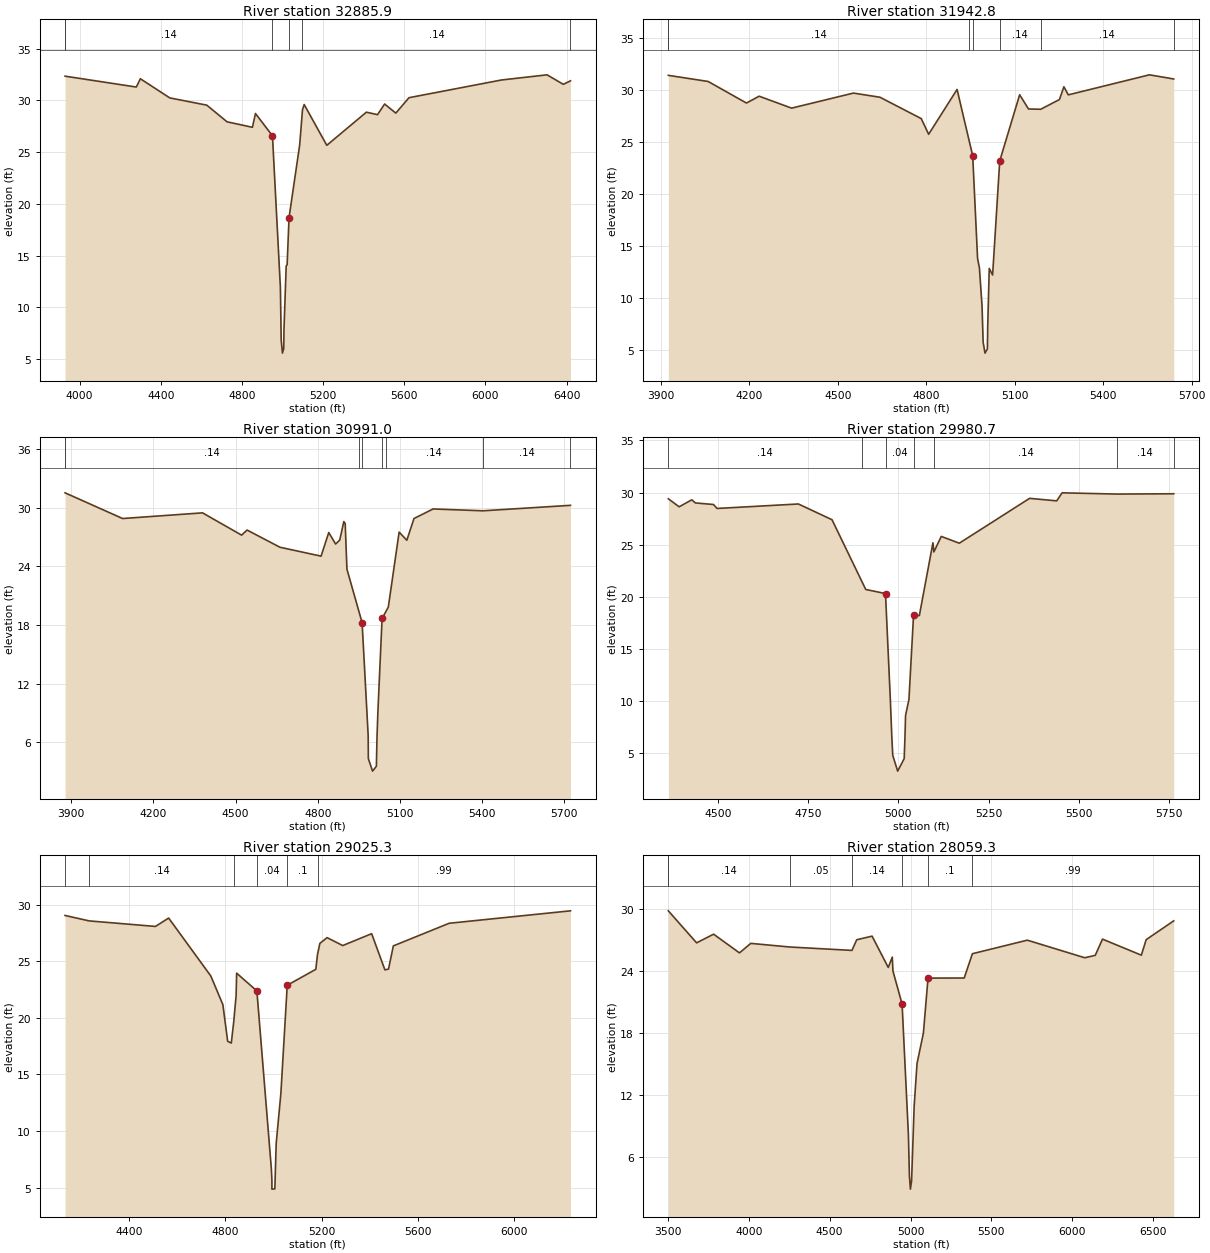
Type RM Length L Ch R = 1 ,32885.9 ,886.4,943.1,828.4
BEGIN DESCRIPTION:
Cross Section 32885.9
END DESCRIPTION:
XS GIS Cut Line= 6
      3161946.37     13854075.48      3161965.03      13853734.9
      3161783.08     13853468.97      3161283.87     13853151.72
      3160719.35     13852923.11      3160126.84      13853100.4
#Sta/Elev= 30
  3928.6   32.35  4279.7    31.3  4299.7    32.1  4444.7   30.25  4626.9   29.55
  4726.9   27.94  4851.9   27.41  4866.9   28.74  4950.6   26.59  4989.7   11.94
  4993.7    6.82  4999.9    5.59  5006.1    6.02  5007.4    7.88  5018.3   14.02
  5022.9   14.12  5032.3   18.68  5084.7    25.7  5098.6    29.1  5106.9   29.61
  5218.4   25.67  5413.4   28.87  5468.4   28.63  5503.4   29.66  5558.4   28.78
  5623.4   30.27  6078.9   31.98  6303.9   32.48  6383.9   31.56  6419.1    31.9
#Mann= 6 , 1 , 0
  3928.6      .2       0  3928.6     .14       0  4950.6     .05       0
  5032.3      .1       0  5098.6     .14       0  6419.1      .2       0
Bank Sta=4950.6,5032.3
XS Rating Curve= 0 ,0
Exp/Cntr=0.3,0.1

Type RM Length L Ch R = 1 ,31942.8 ,741.9,951.8,770.7
BEGIN DESCRIPTION:
Cross Section 31942.8
END DESCRIPTION:
XS GIS Cut Line= 5
      3162566.87     13852867.12      3162310.27     13852773.81
      3161993.02     13852615.19      3161526.48     13852400.58
      3160957.29     13852339.93
#Sta/Elev= 30
  3925.5   31.43  4060.5   30.84  4190.5   28.76  4233.5   29.42  4343.5   28.27
  4553.2   29.72  4643.2   29.32  4783.2   27.26  4808.2   25.75  4904.6   30.07
  4945.5   25.14  4957.6   23.68  4974.1   13.79  4980.4   12.87  4989.3    9.18
    4993    5.71  4999.4    4.66  5007.4    5.07  5008.5    7.24  5013.7   12.82
  5025.1   12.19  5049.3   23.19  5116.8   29.56  5146.8   28.19  5188.1   28.16
  5251.8    29.1  5266.8   30.33  5281.8   29.55  5556.8   31.48  5639.2   31.08
#Mann= 7 , 1 , 0
  3925.5      .2       0  3925.5     .14       0  4945.5      .1       0
  4957.6     .05       0  5049.3     .14       0  5188.1     .14       0
  5639.2      .2       0
Bank Sta=4957.6,5049.3
XS Rating Curve= 0 ,0
Exp/Cntr=0.3,0.1

Type RM Length L Ch R = 1 ,30991.0 ,1182.5,1010.3,626.3
BEGIN DESCRIPTION:
Cross Section 30991.0
END DESCRIPTION:
XS GIS Cut Line= 6
      3162594.87     13852876.45      3162524.89     13852409.91
      3162496.89     13852353.92      3162216.97     13852036.67
      3161825.07     13851752.08      3161423.84     13851719.42
#Sta/Elev= 30
  3877.5   31.52  4087.5   28.89  4379.3   29.47  4521.9   27.19  4541.9   27.71
  4661.9   25.95  4811.9   25.04    4840   27.46    4865   26.28    4880   26.68
    4895   28.58    4900   28.37  4906.3   23.71  4949.5   19.44  4961.7   18.23
  4983.9    6.65  4984.5    4.32  4999.8    3.04  5013.8    3.54  5016.1    6.54
  5019.4    9.16  5034.6   18.66  5047.5   19.32  5057.4   19.83  5096.8    27.5
    5125   26.67    5151   28.89    5221   29.87  5402.6   29.68  5722.2   30.24
#Mann= 8 , 1 , 0
  3877.5      .2       0  3877.5     .14       0  4949.5      .1       0
  4961.7     .04       0  5034.6      .1       0  5047.5     .14       0
  5402.6     .14       0  5722.2      .2       0
Bank Sta=4961.7,5034.6
XS Rating Curve= 0 ,0
Exp/Cntr=0.3,0.1

Type RM Length L Ch R = 1 ,29980.7 ,676.5,955.4,1066.8
BEGIN DESCRIPTION:
Cross Section 29980.7
END DESCRIPTION:
XS GIS Cut Line= 5
      3163140.62     13851398.92      3162688.18     13851374.18
      3162580.87     13851374.18      3162352.26     13851486.15
      3161769.08     13851458.16
#Sta/Elev= 30
  4363.2   29.41  4393.2   28.64  4428.2   29.31  4438.2   29.01  4488.2   28.86
  4498.2   28.48  4723.2   28.91  4816.3    27.4  4898.2   21.53  4909.7   20.71
  4964.3   20.32  4977.8   10.07  4981.8    6.55  4984.4     4.8    4998    3.29
    5016    4.49  5018.2    6.58  5019.8    8.62  5029.2   10.17  5041.9   18.22
    5058   18.21  5095.6   25.19  5098.2   24.31  5118.6    25.8  5168.6   25.15
  5363.1   29.45  5438.1   29.21  5453.1   29.98    5605   29.86    5762   29.89
#Mann= 7 , 1 , 0
  4363.2     .14       0  4898.2      .1       0  4964.3     .04       0
  5041.9      .1       0  5098.2     .14       0    5605     .14       0
    5762      .2       0
Bank Sta=4964.3,5041.9
XS Rating Curve= 0 ,0
Exp/Cntr=0.3,0.1

Type RM Length L Ch R = 1 ,29025.3 ,997.5,966,881.1
BEGIN DESCRIPTION:
Cross Section 29025.3
END DESCRIPTION:
XS GIS Cut Line= 4
      3163333.64     13851452.46      3162832.81     13850543.73
      3162277.62     13850501.74      3161778.41     13850567.05
#Sta/Elev= 30
  4135.1   29.05  4235.1   28.57  4510.1   28.08  4565.1   28.82  4740.1    23.7
  4790.1   21.17  4810.1   17.93  4825.1   17.77  4835.1   19.63  4845.1   21.98
  4847.3   23.95  4931.3   22.38  4991.5    6.62  4993.6    5.67  4993.7    4.86
  5005.8    4.88  5011.5    8.91  5030.9   13.33  5057.3   22.88  5175.9   24.29
  5182.9   25.59  5192.7   26.58  5222.7   27.09  5287.7   26.39  5407.7   27.44
  5462.7   24.24  5477.7   24.31  5497.7   26.36  5729.4   28.36  6232.9   29.46
#Mann= 6 , 1 , 0
  4135.1      .2       0  4235.1     .14       0  4835.1      .1       0
  4931.3     .04       0  5057.3      .1       0  5182.9     .99       0
Bank Sta=4931.3,5057.3
XS Rating Curve= 0 ,0
Exp/Cntr=0.3,0.1

Type RM Length L Ch R = 1 ,28059.3 ,820.5,1011,661.2
BEGIN DESCRIPTION:
Cross Section 28059.3
END DESCRIPTION:
XS GIS Cut Line= 6
       3164581.8     13850821.31      3164083.15     13850436.42
       3163630.6     13850123.84      3163145.39     13849806.58
      3162888.79     13849671.29      3161817.74     13849576.51
#Sta/Elev= 30
  3502.3   29.82  3677.3   26.72  3782.3   27.56  3942.3   25.75  4012.3   26.67
  4252.9   26.32  4637.7   25.99  4667.2   27.02  4762.2   27.37  4862.2   24.34
  4887.2   25.34  4891.2      24  4947.8    20.8  4986.9    8.13  4993.1    4.15
  4999.2    2.89  5006.5    3.69  5022.3    10.9  5040.1   15.04  5079.5   17.99
  5108.1   23.31  5331.9   23.32  5382.5   25.67    5722   26.98    6077   25.28
    6142   25.51    6187   27.08    6427   25.53    6457   27.03  6627.3   28.85
#Mann= 7 , 1 , 0
  3502.3      .2       0  3502.3     .14       0  4252.9     .05       0
  4637.7     .14       0  4947.8     .04       0  5108.1      .1       0
  5382.5     .99       0
Bank Sta=4947.8,5108.1
XS Rating Curve= 0 ,0
Exp/Cntr=0.3,0.1

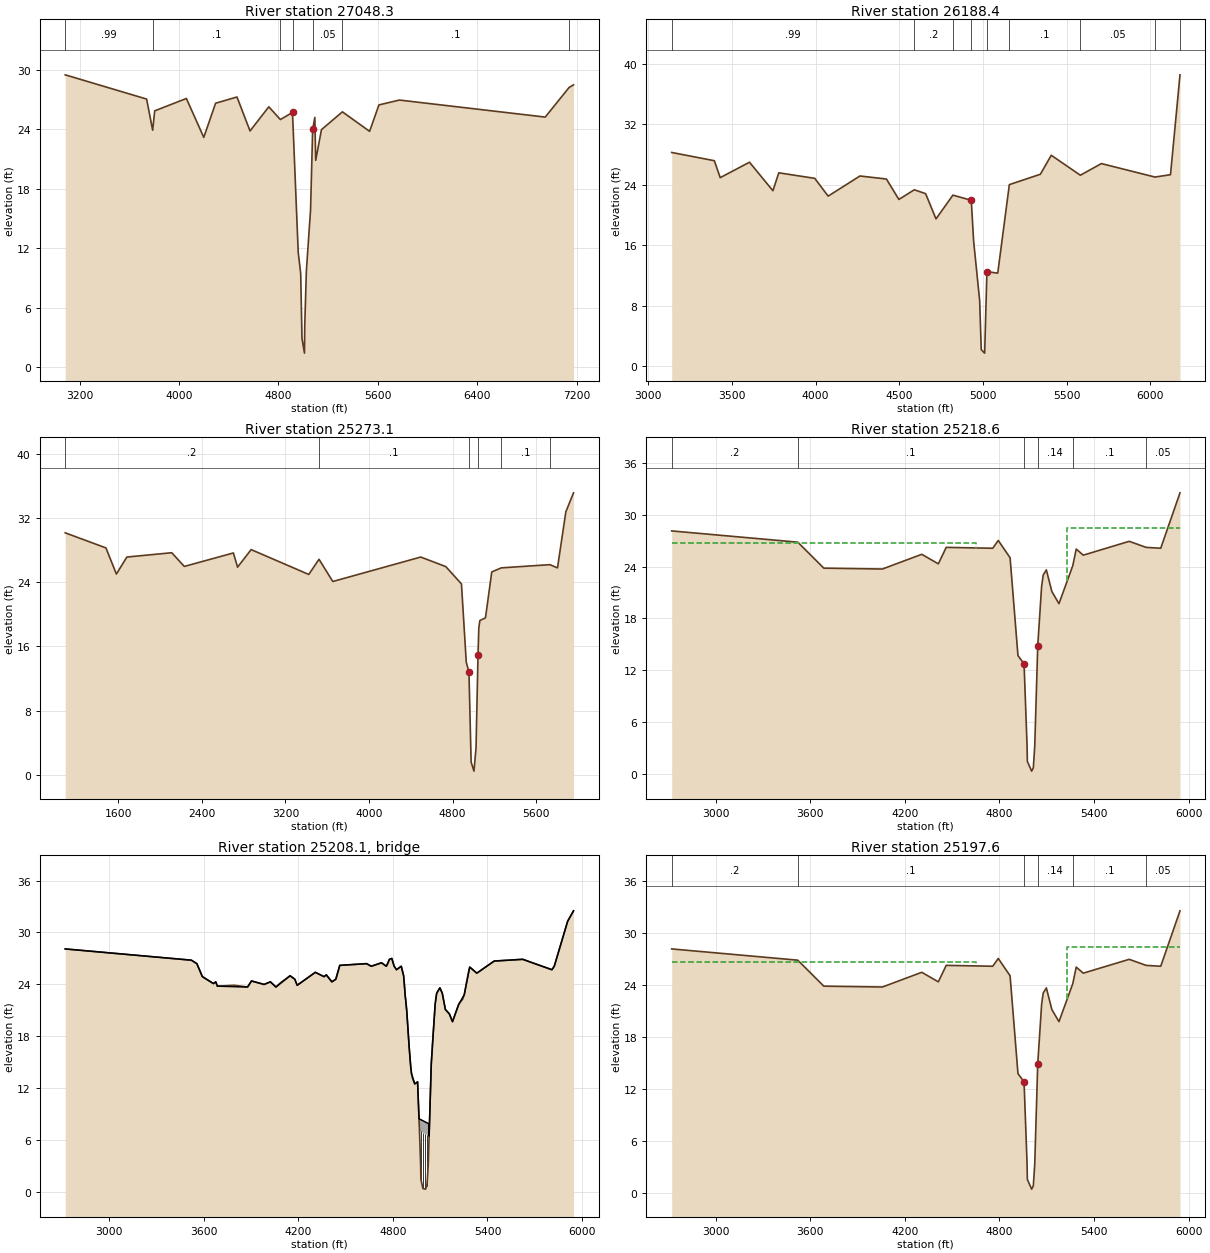
Type RM Length L Ch R = 1 ,27048.3 ,662.4,859.9,1313.7
BEGIN DESCRIPTION:
Cross Section 27048.3
END DESCRIPTION:
XS GIS Cut Line= 6
      3165279.02      13850521.5      3163910.27     13849158.99
      3163821.88     13849120.69      3163658.32     13849085.05
      3162949.14     13849160.17      3161843.41     13849565.42
#Sta/Elev= 30
  3084.7   29.51  3739.7   27.06  3788.5   23.91  3804.7   25.87  4059.7   27.12
  4199.7   23.19  4294.7   26.64  4466.9   27.27  4571.9   23.84  4722.9   26.28
    4816   24.99  4913.5   25.71  4959.7   11.54  4979.4    9.46  4989.9    2.86
  5009.8    1.39  5012.1     4.2  5025.1    9.69  5058.9   15.88  5075.8   24.02
  5093.3    25.2  5100.2   20.87  5146.5   23.97    5315   25.77  5533.9    23.8
  5608.9   26.47  5773.9   26.96    6947   25.24  7138.9   28.23  7174.7    28.5
#Mann= 7 , 1 , 0
  3084.7     .99       0  3788.5      .1       0    4816     .05       0
  4913.5     .04       0  5075.8     .05       0    5315      .1       0
  7138.9      .2       0
Bank Sta=4913.5,5075.8
XS Rating Curve= 0 ,0
Exp/Cntr=0.3,0.1

Type RM Length L Ch R = 1 ,26188.4 ,1612.6,915.3,702.1
BEGIN DESCRIPTION:
Cross Section 26188.4
END DESCRIPTION:
XS GIS Cut Line= 6
      3165404.09     13850329.06      3164802.99     13849303.97
      3164808.16     13849134.76      3164636.47     13848761.52
      3164054.22     13848250.19      3163728.78     13847884.77
#Sta/Elev= 30
  3139.7   28.25  3394.7   27.16  3429.7   24.92  3604.7   26.96  3744.7   23.19
  3779.7   25.56  3994.7   24.83  4074.7   22.48  4264.7   25.14    4423   24.74
  4497.3   22.04  4589.7   23.32  4657.3    22.8  4719.2   19.47  4820.2   22.61
  4929.9   21.93  4944.1   16.51    4980    8.68  4989.6    2.18  5009.9    1.73
  5023.4    12.5  5088.1    12.3  5157.4      24  5342.8   25.37  5407.8   27.88
  5581.7   25.24  5707.4   26.78  6027.6      25  6120.3   25.31  6177.1   38.51
#Mann= 9 , 1 , 0
  3139.7     .99       0  4589.7      .2       0  4820.2      .1       0
  4929.9     .04       0  5023.4     .14       0  5157.4      .1       0
  5581.7     .05       0  6027.6      .1       0  6177.1      .2       0
Bank Sta=4929.9,5023.4
XS Rating Curve= 0 ,0
Exp/Cntr=0.3,0.1

Type RM Length L Ch R = 1 ,25273.1 ,88.4,54.5,48.4
BEGIN DESCRIPTION:
Cross Section 25273.1
END DESCRIPTION:
XS GIS Cut Line= 6
      3168285.42     13849377.99      3165640.68     13847798.62
      3164720.29     13847865.51      3164467.09     13847900.85
      3164236.17     13847952.78      3163877.91      13847858.5
#Sta/Elev= 30
  1091.7   30.17  1481.7   28.29  1581.7   25.03  1681.7   27.15  2111.7   27.69
  2231.7   25.98  2701.7   27.66  2741.7   25.89  2871.7   28.08  3423.3   24.98
  3521.5   26.87  3653.3    24.1    4495   27.15    4735   25.96    4885    23.8
  4931.1   14.02 4956.61   12.84 4977.61    1.57 5004.81     .45 5024.41    3.35
 5043.41   14.93  5051.1   18.32  5061.1   19.23    5115   19.57    5175   25.29
  5265.7    25.8  5730.9    26.2  5804.3    25.8  5884.3   32.79  5957.8   35.16
#Mann= 6 , 1 , 0
  1091.7      .2       0  3521.5      .1       0 4956.61     .04       0
 5043.41     .14       0  5265.7      .1       0  5730.9     .05       0
Bank Sta=4956.61,5043.41
XS Rating Curve= 0 ,0
Exp/Cntr=0.5,0.3

Type RM Length L Ch R = 1 ,25218.6 ,21,21,21
BEGIN DESCRIPTION:
Upstream Section of Bridge/Culvert/Weir
END DESCRIPTION:
XS GIS Cut Line= 6
      3167080.81     13847408.66      3164863.41     13847820.74
      3164841.48     13847813.38      3164817.17     13847806.56
       3164267.8     13847904.55      3163906.54     13847875.62
#Sta/Elev= 30
  2721.5   28.11  3521.5   26.81  3686.5   23.81  4057.9   23.71  4307.9   25.41
  4412.9   24.31  4462.9   26.21    4758   26.11    4793   27.01    4868   25.01
    4918   13.71 4956.61   12.76 4975.61    3.37 4977.61    1.49 5004.81     .37
 5015.41     .76 5024.41    3.27 5043.41   14.85    5068   21.71    5078   23.01
    5098   23.61    5133   21.11    5178   19.71  5265.7    24.1  5287.4   26.01
  5332.4   25.31  5623.5   26.91  5730.9   26.21  5823.5   26.11  5945.7   32.51
#Mann= 6 , 1 , 0
  2721.5      .2       0  3521.5      .1       0 4956.61     .04       0
 5043.41     .14       0  5265.7      .1       0  5730.9     .05       0
#XS Ineff= 2 , 0
       0    4650    26.7    5230       0    28.4
Permanent Ineff=
       F       F
Bank Sta=4956.61,5043.41
XS Rating Curve= 0 ,0
Exp/Cntr=0.5,0.3

Type RM Length L Ch R = 3 ,25208.1 ,,,
BEGIN DESCRIPTION:
Pipeline
END DESCRIPTION:
Bridge Culvert--1,0,-1,-1, 0
Deck Dist Width WeirC Skew NumUp NumDn MinLoCord MaxHiCord MaxSubmerge Is_Ogee
10,1,2.6,0, 60, 60, , , 0.95, 0, 1,1,,
  2721.5  3521.5  3556.5  3591.5  3661.5  3676.5  3686.5  3878.1  3903.1  3983.1
  4023.1  4057.9  4147.9  4177.9  4192.9  4307.9  4362.9  4377.9  4412.9  4437.9
  4462.9  4632.9    4663    4728    4758    4778    4793    4808    4823    4853
    4868    4878    4888    4903    4913    4918 4938.81 4956.61 4965.81 4968.51
 5029.61 5029.71 5043.41    5068    5078    5098    5113    5133    5158    5178
  5217.4  5252.4  5287.4  5332.4  5442.4  5623.5  5808.5  5823.5  5908.5  5945.7
    28.1    26.8    26.4    24.9    24.1    24.3    23.8    23.7    24.4      24
    24.3    23.7      25    24.6    23.9    25.4    24.9    25.1    24.3    24.6
    26.2    26.4    26.1    26.5    26.1    26.9      27    26.1    25.7    26.1
      25    22.7    20.9    16.8    14.5    13.7   12.51   12.75    8.48    8.46
    7.89    6.49   14.84    21.7      23    23.6      23    21.1    20.6    19.7
    21.7    22.8      26    25.3    26.7    26.9    25.7    26.1    31.3    32.5
    28.1    26.8    26.4    24.9    24.1    24.3    23.8    23.7    24.4      24
    24.3    23.7      25    24.6    23.9    25.4    24.9    25.1    24.3    24.6
    26.2    26.4    26.1    26.5    26.1    26.9      27    26.1    25.7    26.1
      25    22.7    20.9    16.8    14.5    13.7   12.51   12.75    8.36    7.13
    6.43    6.49   14.84    21.7      23    23.6      23    21.1    20.6    19.7
    21.7    22.8      26    25.3    26.7    26.9    25.7    26.1    31.3    32.5
  2721.5  3521.5  3556.5  3591.5  3661.5  3676.5  3686.5  3878.1  3903.1  3983.1
  4023.1  4057.9  4147.9  4177.9  4192.9  4307.9  4362.9  4377.9  4412.9  4437.9
  4462.9  4632.9    4663    4728    4758    4778    4793    4808    4823    4853
    4868    4878    4888    4903    4913    4918 4938.81 4956.61 4965.81 4968.51
 5029.61 5029.71 5043.41    5068    5078    5098    5113    5133    5158    5178
  5217.4  5252.4  5287.4  5332.4  5442.4  5623.5  5808.5  5823.5  5908.5  5945.7
    28.1    26.8    26.4    24.9    24.1    24.3    23.8    23.7    24.4      24
    24.3    23.7      25    24.6    23.9    25.4    24.9    25.1    24.3    24.6
    26.2    26.4    26.1    26.5    26.1    26.9      27    26.1    25.7    26.1
      25    22.7    20.9    16.8    14.5    13.7   12.51   12.75    8.48    8.46
    7.89    6.49   14.84    21.7      23    23.6      23    21.1    20.6    19.7
    21.7    22.8      26    25.3    26.7    26.9    25.7    26.1    31.3    32.5
    28.1    26.8    26.4    24.9    24.1    24.3    23.8    23.7    24.4      24
    24.3    23.7      25    24.6    23.9    25.4    24.9    25.1    24.3    24.6
    26.2    26.4    26.1    26.5    26.1    26.9      27    26.1    25.7    26.1
      25    22.7    20.9    16.8    14.5    13.7   12.51   12.75    8.36    7.13
    6.43    6.49   14.84    21.7      23    23.6      23    21.1    20.6    19.7
    21.7    22.8      26    25.3    26.7    26.9    25.7    26.1    31.3    32.5
Pier Skew, UpSta & Num, DnSta & Num=  ,4977.6, 2 ,4977.6, 2 , 0 , 0 , 0 ,,
       1       1
     .44    8.05
       1       1
     .44    8.05
Pier Skew, UpSta & Num, DnSta & Num=  ,4989.6, 2 ,4989.6, 2 , 0 , 0 , 0 ,,
       1       1
    -.56    7.93
       1       1
    -.56    7.93
Pier Skew, UpSta & Num, DnSta & Num=  ,5004.8, 2 ,5004.8, 2 , 0 , 0 , 0 ,,
       1       1
    -.64    7.79
       1       1
    -.64    7.79
Pier Skew, UpSta & Num, DnSta & Num=  ,5015.4, 2 ,5015.4, 2 , 0 , 0 , 0 ,,
       1       1
    -.27    7.69
       1       1
    -.27    7.69
BR Coef= 1 , 1 , 0 ,1.25, 0 ,,,0.8,0,2,0,
WSPro=,,,, 1 ,,,, 0 ,,,, 0 ,,,,-1 ,-1 ,-1 , 0 , 0 , 0 , 0 , 0
BR U #Sta/Elev= 85
  2721.5    28.1  3521.5    26.8  3556.5    26.4  3591.5    24.9  3661.5    24.1
  3676.5    24.3  3686.5    23.8  3793.1    23.9  3878.1    23.7  3903.1    24.4
  3983.1      24  4023.1    24.3  4057.9    23.7  4087.9    24.2  4147.9      25
  4177.9    24.6  4192.9    23.9  4307.9    25.4  4362.9    24.9  4377.9    25.1
  4412.9    24.3  4437.9    24.6  4462.9    26.2  4632.9    26.4    4663    26.1
    4728    26.5    4758    26.1    4768    26.4    4778    26.9    4793      27
    4808    26.1    4823    25.7    4853    26.1    4868      25    4873      24
    4878    22.7    4883      22    4888    20.9    4903    16.8    4913    14.5
    4918    13.7 4925.01   13.12 4938.81   12.51 4956.61   12.75 4963.21    9.58
 4965.81    8.36 4965.92    8.31 4966.01    8.27 4968.51     7.1 4975.61    3.36
 4977.61    1.48 4988.31     .62 4989.61     .44 5004.81     .36 5006.91     .36
 5015.41     .75 5018.41    1.44 5024.41    3.26  5029.5    6.36 5029.61    6.43
 5029.71    6.49 5043.41   14.84    5053    17.7    5068    21.7    5073    22.5
    5078      23    5098    23.6    5113      23    5133    21.1    5158    20.6
    5178    19.7  5217.4    21.7  5242.4    22.3  5252.4    22.8  5265.7   24.09
  5282.4    25.7  5287.4      26  5332.4    25.3  5442.4    26.7  5623.5    26.9
  5730.9    26.2  5808.5    25.7  5823.5    26.1  5908.5    31.3  5945.7    32.5
BR U #Mann= 6
  2721.5      .2  3521.5      .1 4956.61     .04 5043.41     .14  5265.7      .1
  5730.9     .05
BR U Banks=4956.61,5043.41
BR D #Sta/Elev= 85
  2721.5    28.1  3521.5    26.8  3556.5    26.4  3591.5    24.9  3661.5    24.1
  3676.5    24.3  3686.5    23.8  3793.1    23.9  3878.1    23.7  3903.1    24.4
  3983.1      24  4023.1    24.3  4057.9    23.7  4087.9    24.2  4147.9      25
  4177.9    24.6  4192.9    23.9  4307.9    25.4  4362.9    24.9  4377.9    25.1
  4412.9    24.3  4437.9    24.6  4462.9    26.2  4632.9    26.4    4663    26.1
    4728    26.5    4758    26.1    4768    26.4    4778    26.9    4793      27
    4808    26.1    4823    25.7    4853    26.1    4868      25    4873      24
    4878    22.7    4883      22    4888    20.9    4903    16.8    4913    14.5
    4918    13.7 4925.01   13.12 4938.81   12.51 4956.61   12.75 4963.21    9.58
 4965.81    8.36 4965.92    8.31 4966.01    8.27 4968.51     7.1 4975.61    3.36
 4977.61    1.48 4988.31     .62 4989.61     .44 5004.81     .36 5006.91     .36
 5015.41     .75 5018.41    1.44 5024.41    3.26  5029.5    6.36 5029.61    6.43
 5029.71    6.49 5043.41   14.84    5053    17.7    5068    21.7    5073    22.5
    5078      23    5098    23.6    5113      23    5133    21.1    5158    20.6
    5178    19.7  5217.4    21.7  5242.4    22.3  5252.4    22.8  5265.7   24.09
  5282.4    25.7  5287.4      26  5332.4    25.3  5442.4    26.7  5623.5    26.9
  5730.9    26.2  5808.5    25.7  5823.5    26.1  5908.5    31.3  5945.7    32.5
BR D #Mann= 6
  2721.5      .2  3521.5      .1 4956.61     .04 5043.41     .14  5265.7      .1
  5730.9     .05
BR D Banks=4956.61,5043.41
BC Design=,, 0 ,, 0 ,,,,,,
BC HTab HWMax=32.51
BC Use User HTab Curves=0
BC User HTab FreeFlow(D)= 0

Type RM Length L Ch R = 1 ,25197.6 ,31.6,31.6,31.6
BEGIN DESCRIPTION:
Downstream Section of Bridge/Culvert/Weir
END DESCRIPTION:
XS GIS Cut Line= 6
      3167092.05     13847390.92      3164874.65       13847803.
      3164852.72     13847795.64      3164828.41     13847788.82
      3164279.04     13847886.81      3163917.78     13847857.88
#Sta/Elev= 30
  2721.5   28.16  3521.5   26.86  3686.5   23.86  4057.9   23.76  4307.9   25.46
  4412.9   24.36  4462.9   26.26    4758   26.16    4793   27.06    4868   25.06
    4918   13.76 4956.61   12.81 4975.61    3.42 4977.61    1.54 5004.81     .42
 5015.41     .81 5024.41    3.32 5043.41    14.9    5068   21.76    5078   23.06
    5098   23.66    5133   21.16    5178   19.76  5265.7   24.15  5287.4   26.06
  5332.4   25.36  5623.5   26.96  5730.9   26.26  5823.5   26.16  5945.7   32.56
#Mann= 6 , 1 , 0
  2721.5      .2       0  3521.5      .1       0 4956.61     .04       0
 5043.41     .14       0  5265.7      .1       0  5730.9     .05       0
#XS Ineff= 2 , 0
       0    4650    26.7    5230       0    28.4
Permanent Ineff=
       F       F
Bank Sta=4956.61,5043.41
XS Rating Curve= 0 ,0
Exp/Cntr=0.5,0.3