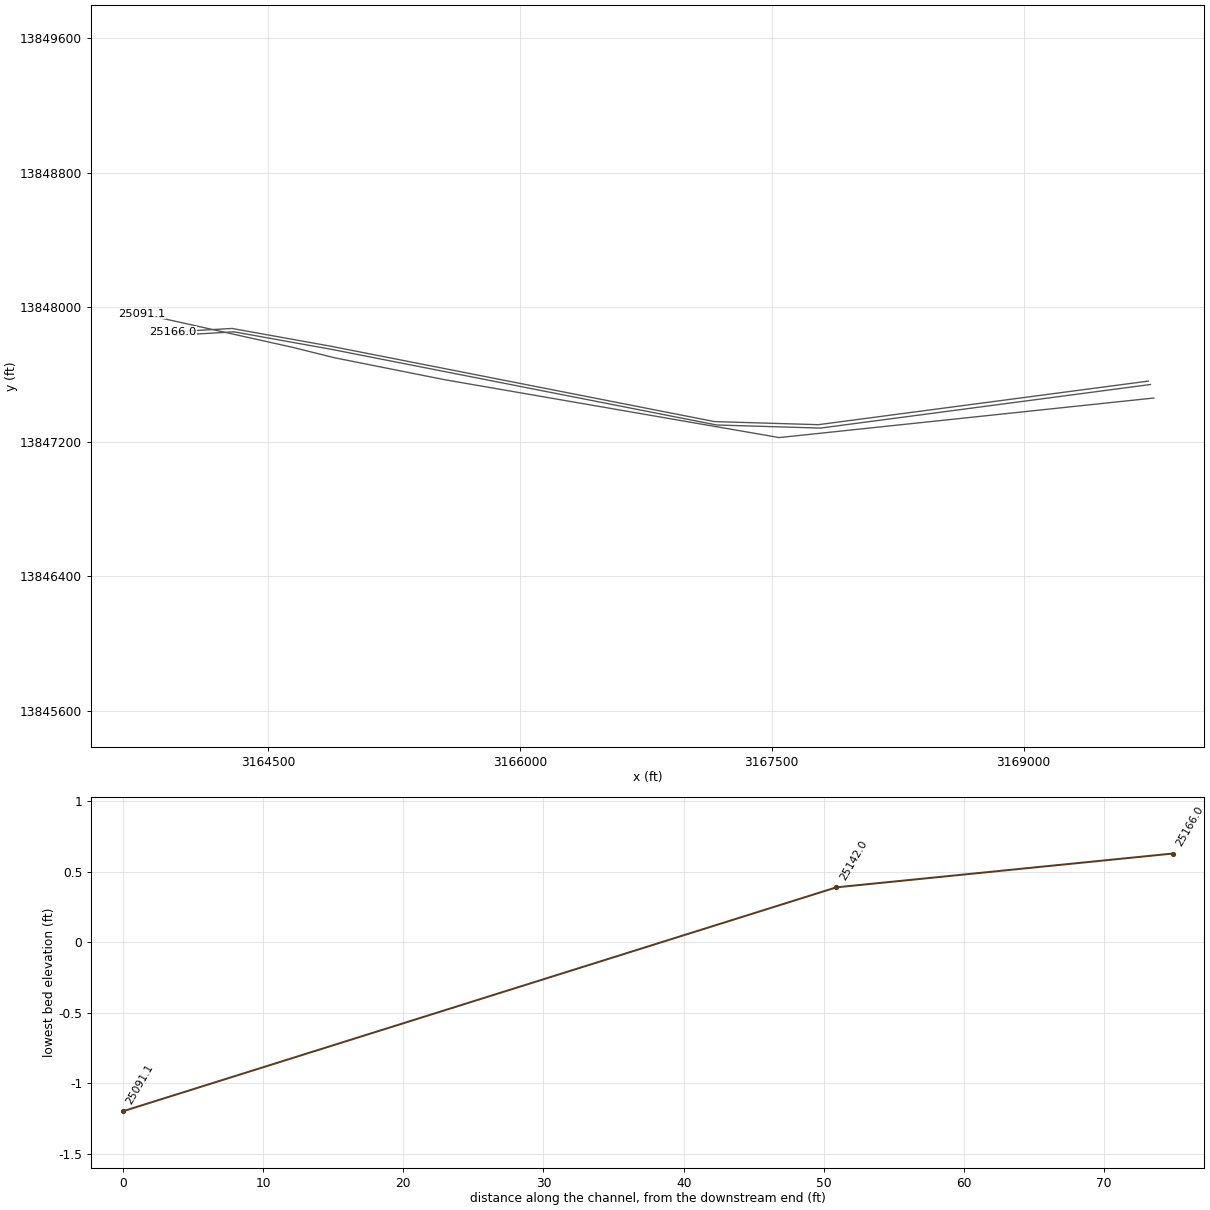
HEC-RAS study H100-00-00.prj: H100-00-00

--- H100-00-00.g01 (geometry) --- (continued)

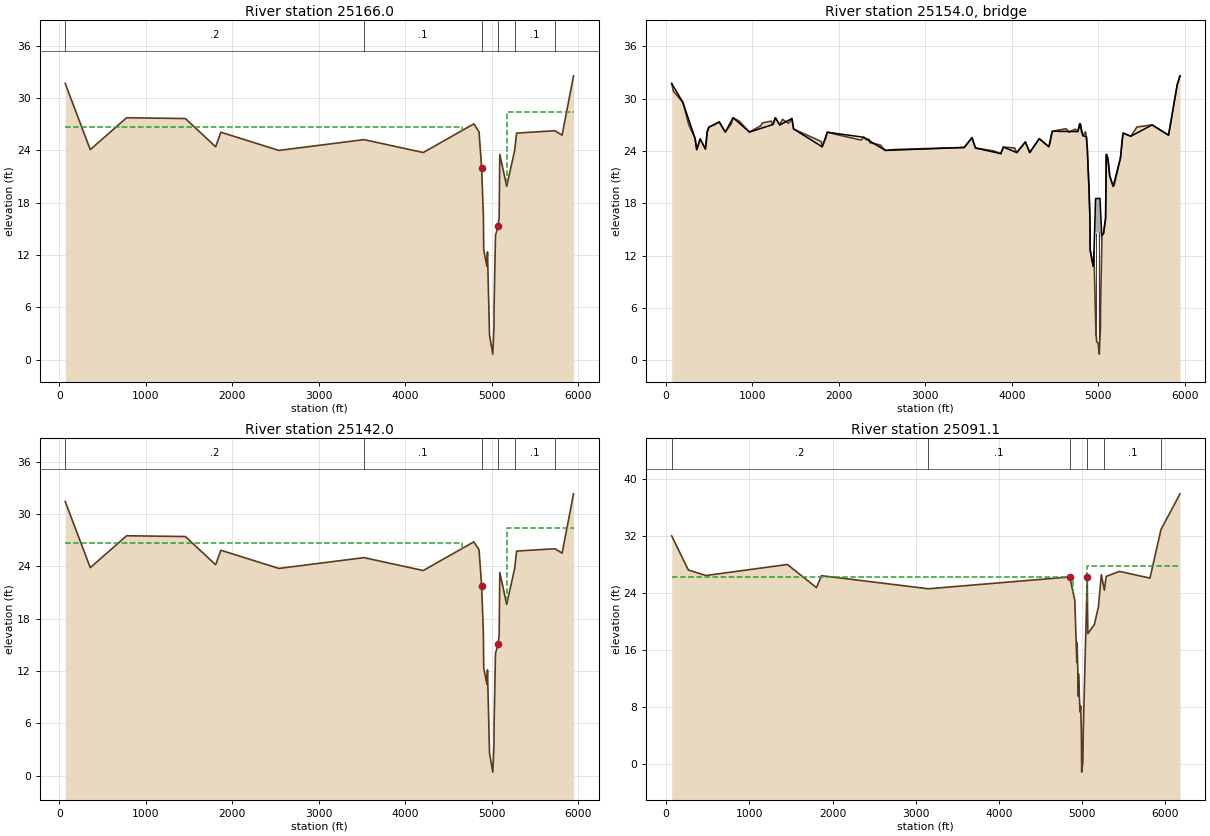
Type RM Length L Ch R = 1 ,25166.0 ,24,24,24
BEGIN DESCRIPTION:
Upstream Section of Bridge/Culvert/Weir
END DESCRIPTION:
XS GIS Cut Line= 6
      3169741.95     13847560.61      3167777.28     13847301.34
      3167158.86     13847319.69      3164869.62     13847768.95
      3164286.12     13847873.83      3163933.88     13847853.24
#Sta/Elev= 30
    66.7   31.68   356.7   24.09   776.7   27.75  1456.7   27.66  1806.7   24.42
  1866.7   26.09  2538.1      24  3521.5   25.24  4207.8   23.76  4792.9   27.05
  4852.9   26.13  4882.9   22.02  4902.9   16.56 4907.06   12.57 4944.04    10.7
 4950.53   12.36    4974    2.81 5011.93     .63 5025.96    3.79 5026.57    5.87
 5043.02   14.24  5072.9   15.33 5085.28   16.24  5092.9   23.54  5172.9   19.88
  5265.7   24.05  5287.3   25.99  5730.9   26.26  5813.4   25.75  5945.7   32.56
#Mann= 6 , 1 , 0
    66.7      .2       0  3521.5      .1       0  4882.9     .04       0
  5072.9     .14       0  5265.7      .1       0  5730.9     .05       0
#XS Ineff= 2 , 0
       0    4650    26.7    5180       0    28.4
Permanent Ineff=
       F       F
Bank Sta=4882.9,5072.9
XS Rating Curve= 0 ,0
Exp/Cntr=0.5,0.3

Type RM Length L Ch R = 3 ,25154.0 ,,,
BEGIN DESCRIPTION:
Pipeline - 30 Degree Skew
END DESCRIPTION:
Bridge Culvert--1,0,-1,-1, 0
Deck Dist Width WeirC Skew NumUp NumDn MinLoCord MaxHiCord MaxSubmerge Is_Ogee
10,4,2.6,0, 60, 60, , , 0.95, 0, 1,1,,
    66.7   196.7   336.7   356.7   396.7   456.7   476.7   496.7   616.7   686.7
   776.7   966.7  1236.7  1266.7  1316.7  1456.7  1476.7  1806.7  1866.7  2288.1
  2538.1  3450.1  3540.1  3580.1  3873.1  3903.1  4057.8  4157.8  4207.8  4317.8
  4427.8  4467.8  4762.9  4792.9  4822.9  4862.9  4872.9  4892.9  4902.9 4907.06
 4944.04 4950.53 4956.59 4968.98 5020.18 5039.45 5043.02 5061.12 5085.28  5092.9
  5112.9  5132.9  5172.9  5257.3  5287.3  5377.3  5623.4  5813.4  5913.4  5945.7
   31.75   29.58   25.47   24.16   25.39   24.24   26.18   26.74   27.34   26.18
   27.82   26.18   27.04   27.82   26.99   27.73   26.53   24.49   26.16   25.58
   24.07   24.41   25.54   24.35    23.7   24.46   23.82   25.05   23.83   25.42
    24.5   26.27   26.23   27.12   25.76   25.64   24.43   19.76   16.63   12.64
   10.77   12.43   14.38   18.55   18.57   14.63   14.31   14.53   16.31   23.61
   23.05   21.15   19.95   23.22   26.06    25.7      27   25.82    31.6   32.63
   31.75   29.58   25.47   24.16   25.39   24.24   26.18   26.74   27.34   26.18
   27.82   26.18   27.04   27.82   26.99   27.73   26.53   24.49   26.16   25.58
   24.07   24.41   25.54   24.35    23.7   24.46   23.82   25.05   23.83   25.42
    24.5   26.27   26.23   27.12   25.76   25.64   24.43   19.76   16.63   12.64
   10.77   12.43    9.96   14.64   14.66   12.49   14.31   14.53   16.31   23.61
   23.05   21.15   19.95   23.22   26.06    25.7      27   25.82    31.6   32.63
    66.7   196.7   336.7   356.7   396.7   456.7   476.7   496.7   616.7   686.7
   776.7   966.7  1236.7  1266.7  1316.7  1456.7  1476.7  1806.7  1866.7  2288.1
  2538.1  3450.1  3540.1  3580.1  3873.1  3903.1  4057.8  4157.8  4207.8  4317.8
  4427.8  4467.8  4762.9  4792.9  4822.9  4862.9  4872.9  4892.9  4902.9 4907.06
 4944.04 4950.53 4956.59 4968.98 5020.18 5039.45 5043.02 5061.12 5085.28  5092.9
  5112.9  5132.9  5172.9  5257.3  5287.3  5377.3  5623.4  5813.4  5913.4  5945.7
   31.75   29.58   25.47   24.16   25.39   24.24   26.18   26.74   27.34   26.18
   27.82   26.18   27.04   27.82   26.99   27.73   26.53   24.49   26.16   25.58
   24.07   24.41   25.54   24.35    23.7   24.46   23.82   25.05   23.83   25.42
    24.5   26.27   26.23   27.12   25.76   25.64   24.43   19.76   16.63   12.64
   10.77   12.43   14.38   18.55   18.57   14.63   14.31   14.53   16.31   23.61
   23.05   21.15   19.95   23.22   26.06    25.7      27   25.82    31.6   32.63
   31.75   29.58   25.47   24.16   25.39   24.24   26.18   26.74   27.34   26.18
   27.82   26.18   27.04   27.82   26.99   27.73   26.53   24.49   26.16   25.58
   24.07   24.41   25.54   24.35    23.7   24.46   23.82   25.05   23.83   25.42
    24.5   26.27   26.23   27.12   25.76   25.64   24.43   19.76   16.63   12.64
   10.77   12.43    9.96   14.64   14.66   12.49   14.31   14.53   16.31   23.61
   23.05   21.15   19.95   23.22   26.06    25.7      27   25.82    31.6   32.63
Pier Skew, UpSta & Num, DnSta & Num=  ,4977.1, 2 ,4977.1, 2 , 0 , 0 , 0 ,,
     1.4     1.4
    1.78   15.64
     1.4     1.4
    1.78   15.64
Pier Skew, UpSta & Num, DnSta & Num=  ,5011.9, 2 ,5011.9, 2 , 0 , 0 , 0 ,,
     1.4     1.4
    -.25   15.66
     1.4     1.4
    -.25   15.66
BR Coef= 1 , 1 , 0 ,1.25, 0 ,,,0.8,0,2,0,
WSPro=,,,, 1 ,,,, 0 ,,,, 0 ,,,,-1 ,-1 ,-1 , 0 , 0 , 0 , 0 , 0
BR U #Sta/Elev= 111
    66.7   31.75    86.7   30.87   196.7   29.58   266.7   26.96   336.7   25.47
   356.7   24.16   396.7   25.39   456.7   24.24   466.7   24.93   476.7   26.18
   496.7   26.74   556.7   26.99   616.7   27.34   686.7   26.18   756.7   27.13
   776.7   27.82   846.7   27.44   966.7   26.18  1096.7    26.9  1116.7   27.23
  1216.7   27.43  1236.7   27.04  1266.7   27.82  1316.7   26.99  1346.7   27.63
  1416.7   27.19  1456.7   27.73  1476.7   26.53  1796.7   25.09  1806.7   24.49
  1846.7    25.4  1866.7   26.16  2048.1   25.73  2258.1   25.26  2288.1   25.58
  2318.1    25.3  2348.1   25.35  2358.1   24.96  2478.1    24.7  2538.1   24.07
  2650.1   24.18  3450.1   24.41  3521.5   25.31  3540.1   25.54  3580.1   24.35
  3793.1   24.01  3873.1    23.7  3903.1   24.46  4033.1   24.35  4057.8   23.82
  4157.8   25.05  4207.8   23.83  4317.8   25.42  4427.8    24.5  4437.8   24.68
  4467.8   26.27  4627.8   26.56  4662.9   26.16  4732.9   26.51  4762.9   26.23
  4782.9   27.14  4792.9   27.12  4802.9   26.33  4822.9   25.76  4852.9    26.2
  4862.9   25.64  4872.9   24.43  4882.9   22.09  4892.9   19.76  4902.9   16.63
 4907.06   12.64 4928.36   11.35 4944.04   10.77 4949.98   12.29 4950.53   12.43
 4956.59    9.96 4956.68    9.93 4968.98    4.92    4974    2.88 4977.12    2.91
 4981.28    2.15 4999.64    1.93 5010.55     .79 5011.93      .7 5020.18    2.56
 5025.96    3.86 5026.57    5.94 5039.45   12.49 5039.56   12.55 5043.02   14.31
 5045.68   14.34 5061.12   14.53  5072.9    15.4 5085.28   16.31  5092.9   23.61
  5102.9   23.55  5112.9   23.05  5132.9   21.15  5172.9   19.95  5182.9   20.02
  5257.3   23.22  5265.7   24.12  5277.3   25.36  5287.3   26.06  5377.3    25.7
  5447.3   26.76  5623.4      27  5730.9   26.33  5813.4   25.82  5913.4    31.6
  5945.7   32.63
BR U #Mann= 6
    66.7      .2  3521.5      .1  4882.9     .04  5072.9     .14  5265.7      .1
  5730.9     .05
BR U Banks=4882.9,5072.9
BR D #Sta/Elev= 111
    66.7   31.75    86.7   30.87   196.7   29.58   266.7   26.96   336.7   25.47
   356.7   24.16   396.7   25.39   456.7   24.24   466.7   24.93   476.7   26.18
   496.7   26.74   556.7   26.99   616.7   27.34   686.7   26.18   756.7   27.13
   776.7   27.82   846.7   27.44   966.7   26.18  1096.7    26.9  1116.7   27.23
  1216.7   27.43  1236.7   27.04  1266.7   27.82  1316.7   26.99  1346.7   27.63
  1416.7   27.19  1456.7   27.73  1476.7   26.53  1796.7   25.09  1806.7   24.49
  1846.7    25.4  1866.7   26.16  2048.1   25.73  2258.1   25.26  2288.1   25.58
  2318.1    25.3  2348.1   25.35  2358.1   24.96  2478.1    24.7  2538.1   24.07
  2650.1   24.18  3450.1   24.41  3521.5   25.31  3540.1   25.54  3580.1   24.35
  3793.1   24.01  3873.1    23.7  3903.1   24.46  4033.1   24.35  4057.8   23.82
  4157.8   25.05  4207.8   23.83  4317.8   25.42  4427.8    24.5  4437.8   24.68
  4467.8   26.27  4627.8   26.56  4662.9   26.16  4732.9   26.51  4762.9   26.23
  4782.9   27.14  4792.9   27.12  4802.9   26.33  4822.9   25.76  4852.9    26.2
  4862.9   25.64  4872.9   24.43  4882.9   22.09  4892.9   19.76  4902.9   16.63
 4907.06   12.64 4928.36   11.35 4944.04   10.77 4949.98   12.29 4950.53   12.43
 4956.59    9.96 4956.68    9.93 4968.98    4.92    4974    2.88 4977.12    2.91
 4981.28    2.15 4999.64    1.93 5010.55     .79 5011.93      .7 5020.18    2.56
 5025.96    3.86 5026.57    5.94 5039.45   12.49 5039.56   12.55 5043.02   14.31
 5045.68   14.34 5061.12   14.53  5072.9    15.4 5085.28   16.31  5092.9   23.61
  5102.9   23.55  5112.9   23.05  5132.9   21.15  5172.9   19.95  5182.9   20.02
  5257.3   23.22  5265.7   24.12  5277.3   25.36  5287.3   26.06  5377.3    25.7
  5447.3   26.76  5623.4      27  5730.9   26.33  5813.4   25.82  5913.4    31.6
  5945.7   32.63
BR D #Mann= 6
    66.7      .2  3521.5      .1  4882.9     .04  5072.9     .14  5265.7      .1
  5730.9     .05
BR D Banks=4882.9,5072.9
BC Design=,, 0 ,, 0 ,,,,,,
BC HTab HWMax=32.56
BC Use User HTab Curves=0
BC User HTab FreeFlow(D)= 0

Type RM Length L Ch R = 1 ,25142.0 ,50.9,50.9,50.9
BEGIN DESCRIPTION:
Downstream Section of Bridge/Culvert/Weir
END DESCRIPTION:
XS GIS Cut Line= 6
       3169754.8     13847540.34      3167790.12     13847281.06
       3167171.7     13847299.41      3164882.46     13847748.67
      3164298.96     13847853.55      3163946.72     13847832.97
#Sta/Elev= 30
    66.7   31.44   356.7   23.85   776.7   27.51  1456.7   27.42  1806.7   24.18
  1866.7   25.85  2538.1   23.76  3521.5      25  4207.8   23.52  4792.9   26.81
  4852.9   25.89  4882.9   21.78  4902.9   16.32 4907.06   12.33 4944.04   10.46
 4950.53   12.12    4974    2.57 5011.93     .39 5025.96    3.55 5026.57    5.63
 5043.02      14  5072.9   15.09 5085.28      16  5092.9    23.3  5172.9   19.64
  5265.7   23.81  5287.3   25.75  5730.9   26.02  5813.4   25.51  5945.7   32.32
#Mann= 6 , 1 , 0
    66.7      .2       0  3521.5      .1       0  4882.9     .04       0
  5072.9     .14       0  5265.7      .1       0  5730.9     .05       0
#XS Ineff= 2 , 0
       0    4650    26.7    5180       0    28.4
Permanent Ineff=
       F       F
Bank Sta=4882.9,5072.9
XS Rating Curve= 0 ,0
Exp/Cntr=0.5,0.3

Type RM Length L Ch R = 1 ,25091.1 ,356,356,356
BEGIN DESCRIPTION:
Upstream Section of Bridge/Culvert/Weir
END DESCRIPTION:
XS GIS Cut Line= 6
      3169774.15     13847459.87      3167544.76     13847224.58
      3165555.95      13847568.2      3164895.64     13847699.57
      3164651.47     13847760.44      3163750.69     13847960.64
#Sta/Elev= 30
    66.7   31.97   266.7   27.18   476.7    26.4  1456.7   27.95  1806.7   24.71
  1866.7   26.38  3150.6   24.54 4849.63    26.2 4910.22   22.93 4934.81   14.18
 4938.49   16.95 4953.89    9.43 4954.35   12.61 4973.04    7.24 4981.16    8.09
  4989.2    4.46 4993.11    -1.2 5006.97     .16 5012.64    4.84 5059.52   26.16
 5067.03   18.24 5146.15   19.53 5194.56   22.03 5229.49   26.52  5265.7   24.34
  5287.3   26.28  5447.3   26.98  5813.4   26.04  5945.7   32.85  6174.4   37.87
#Mann= 6 , 1 , 0
    66.7      .2       0  3150.6      .1       0 4849.63    .035       0
 5059.52     .14       0  5265.7      .1       0  5945.7      .2       0
#XS Ineff= 2 , 0
       0    4890   26.15    5052       0   27.75
Permanent Ineff=
       F       F
Bank Sta=4849.63,5059.52
XS Rating Curve= 0 ,0
Exp/Cntr=0.5,0.3