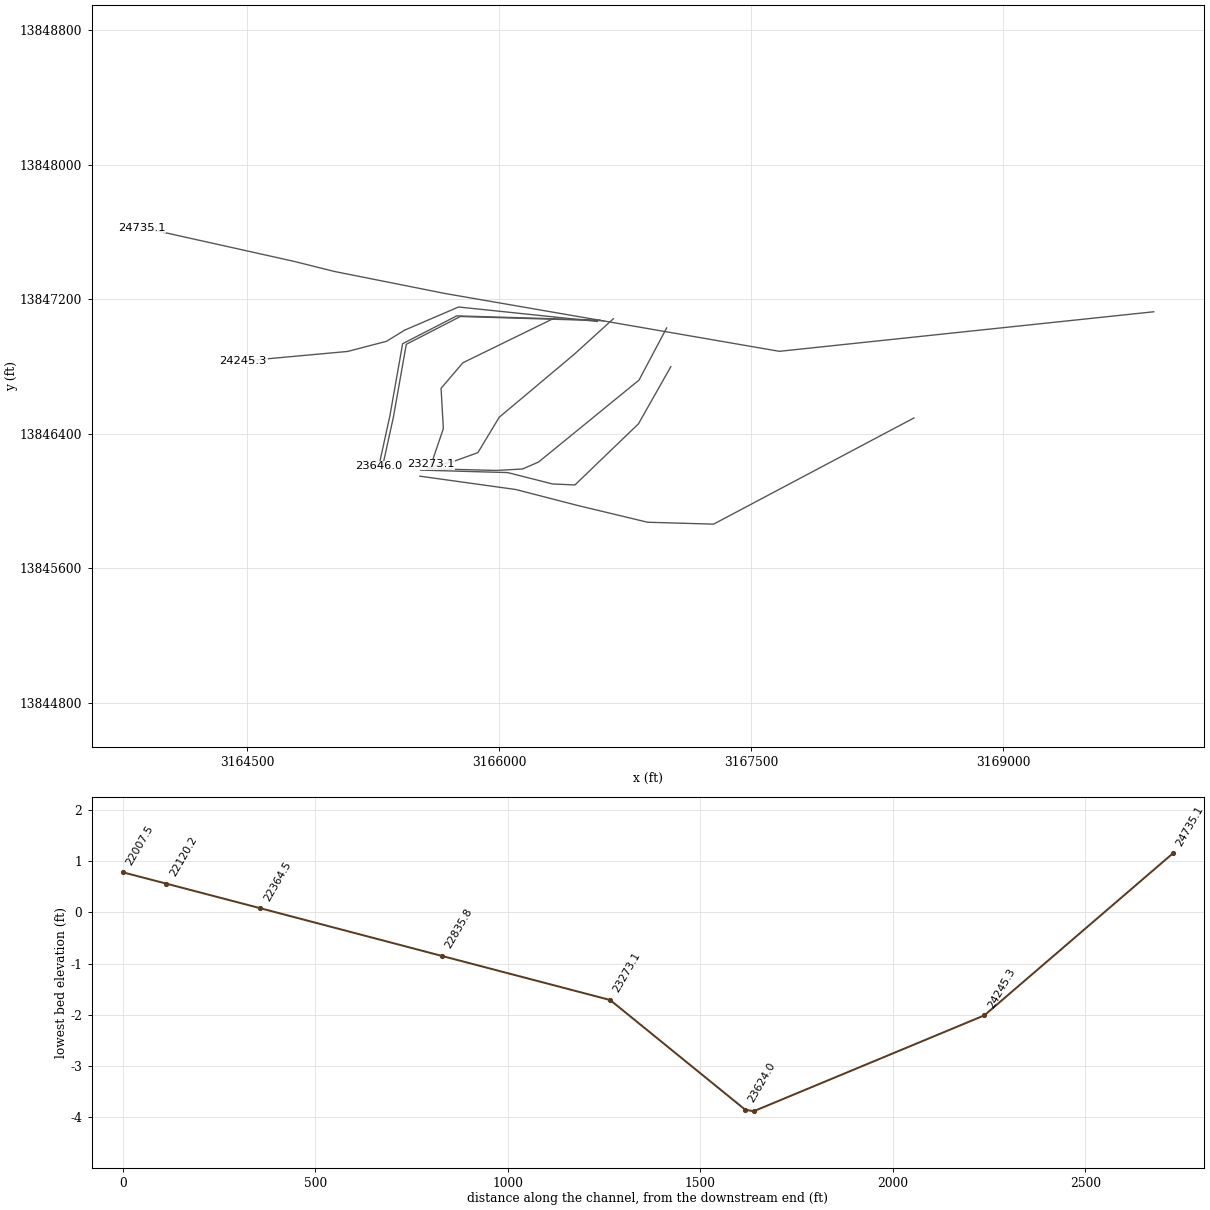
HEC-RAS study H100-00-00.prj: H100-00-00

--- H100-00-00.g01 (geometry) --- (continued)

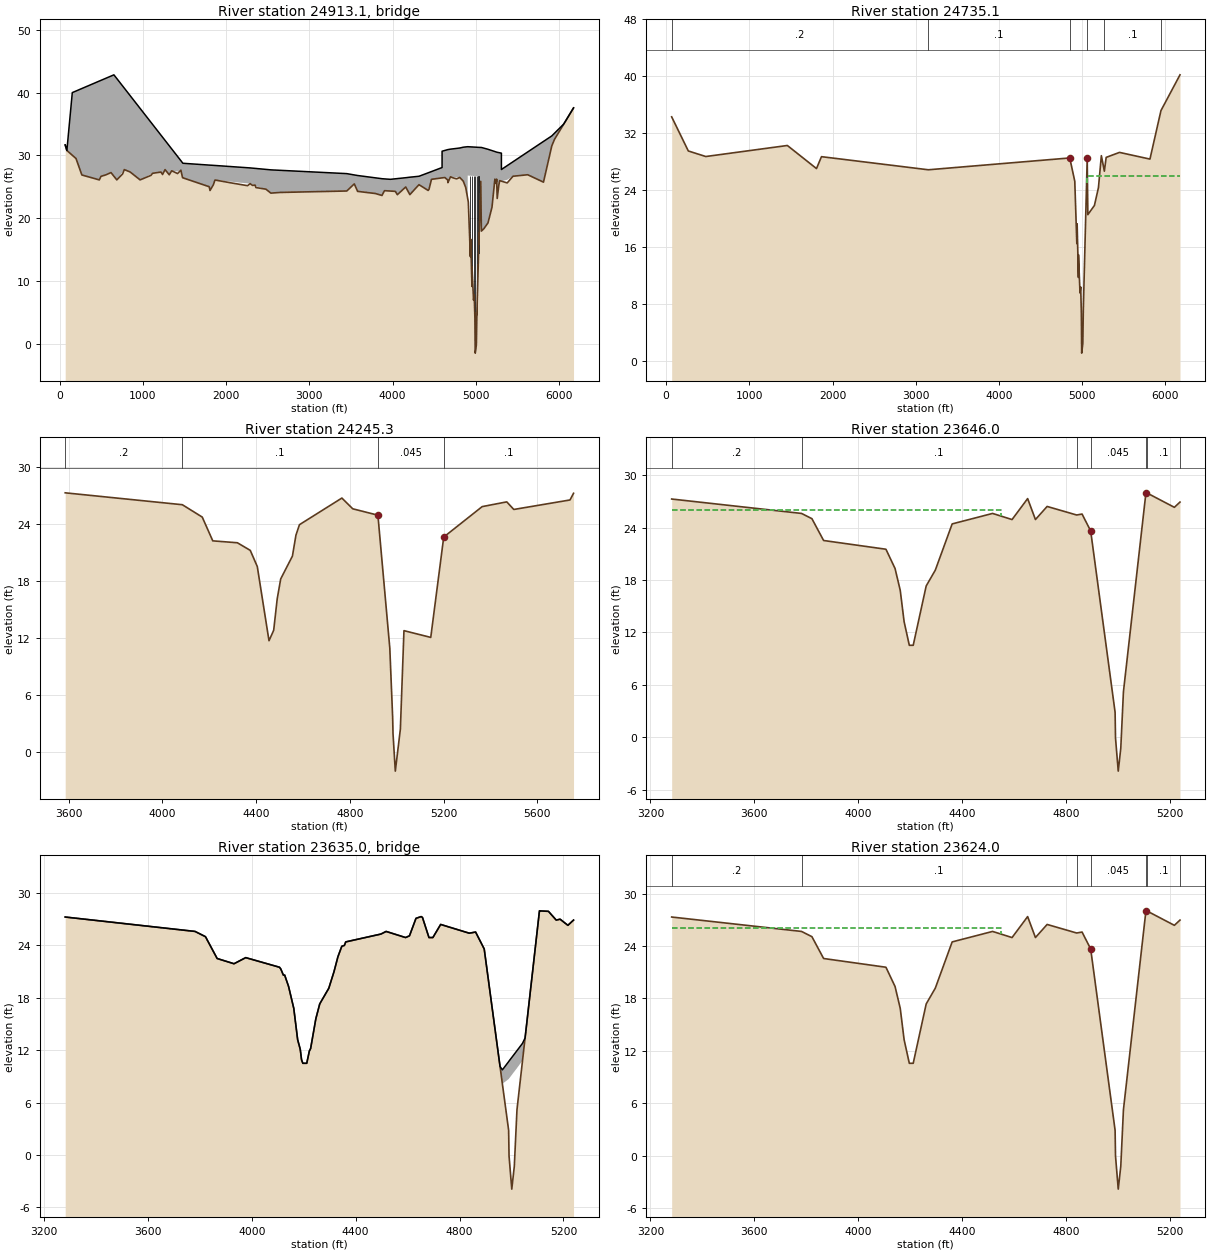
Type RM Length L Ch R = 3 ,24913.1 ,,,
BEGIN DESCRIPTION:
INTERSTATE 10 - 40 Degree Skew
Structure ID: H00-15
END DESCRIPTION:
Bridge Culvert--1,0,-1,-1, 0
Deck Dist Width WeirC Skew NumUp NumDn MinLoCord MaxHiCord MaxSubmerge Is_Ogee
10,336,2.6,0, 60, 60, , , 0.95, 0, 1,1,,
    66.7    86.7   151.8   196.7   266.7   476.7   616.7   651.8   686.7   776.7
   966.7  1116.7  1236.7  1266.7  1316.7  1456.7  1480.8  1796.7  1806.7  1866.7
  2288.1  2538.1  3450.1  3540.1  3580.1  3873.1  3903.1  3973.5  4057.8  4157.8
  4207.8  4317.8  4427.8  4467.8 4594.79  4594.9 4665.03  4696.2 4807.04 4849.63
 4902.55 4902.64 5041.87 5041.98 5059.52 5067.03 5146.15 5194.56 5229.49 5239.68
 5250.25  5257.3  5287.3  5307.9 5308.01  5623.4  5813.4  5913.4  6056.7  6174.4
   31.66   30.78      40   40.25   40.65   41.84   42.63   42.83   42.24   40.71
   37.48   34.93   32.89   32.38   31.53   29.15   28.74   28.45   28.44   28.39
      28   27.69   27.09   26.88   26.79   26.28   26.25   26.18    26.3   26.44
   26.52   26.67   27.22   27.42   28.06   30.66   30.92   30.99   31.17    31.3
   31.38   31.38   31.27   31.27   31.26   31.26   30.97   30.76   30.61   30.56
   30.52   30.49   30.41   30.35   27.75   30.54   32.22    33.1   34.99   37.56
   31.66   30.78   30.02   29.49   26.87   26.09   27.25   26.67   26.09   27.73
   26.09   27.14   26.95   27.73    26.9   27.64   26.42      25    24.4   26.07
   25.49   23.98   24.32   25.45   24.26   23.61   24.37   24.31   23.73   24.96
   23.74   25.33   24.41   26.18   26.41   26.41   25.65   26.58   26.48   25.89
   23.18   26.78   26.67   18.38   25.85   17.93   19.22   21.72   26.21   25.57
   26.22   23.13   25.97   25.89   25.89   26.91   25.73   31.51   34.98   37.56
    66.7    86.7   151.8   196.7   266.7   476.7   616.7   651.8   686.7   776.7
   966.7  1116.7  1236.7  1266.7  1316.7  1456.7  1480.8  1796.7  1806.7  1866.7
  2288.1  2538.1  3450.1  3540.1  3580.1  3873.1  3903.1  3973.5  4057.8  4157.8
  4207.8  4317.8  4427.8  4467.8 4594.79  4594.9 4665.03  4696.2 4807.04 4849.63
 4902.55 4902.64 5041.87 5041.98 5059.52 5067.03 5146.15 5194.56 5229.49 5239.68
 5250.25  5257.3  5287.3  5307.9 5308.01  5623.4  5813.4  5913.4  6056.7  6174.4
   31.71   30.83      40   40.25   40.65   41.84   42.63   42.83   42.24   40.71
   37.48   34.93   32.89   32.38   31.53   29.15   28.74   28.45   28.44   28.39
      28   27.69   27.09   26.88   26.79   26.28   26.25   26.18    26.3   26.44
   26.52   26.67   27.22   27.42   28.06   30.66   30.92   30.99   31.17    31.3
   31.38   31.38   31.27   31.27   31.26   31.26   30.97   30.76   30.61   30.56
   30.52   30.49   30.41   30.35   27.75   30.54   32.22    33.1   35.03   37.61
   31.71   30.83   30.07   29.54   26.92   26.14    27.3   26.72   26.14   27.78
   26.14   27.19      27   27.78   26.95   27.69   26.47   25.05   24.45   26.12
   25.54   24.03   24.37    25.5   24.31   23.66   24.42   24.36   23.78   25.01
   23.79   25.38   24.46   26.23   26.46   26.46    25.7   26.63   26.53   25.94
   23.23   26.83   26.72   18.43    25.9   17.98   19.27   21.77   26.26   25.62
   26.27   23.18   26.02   25.94   25.94   26.96   25.78   31.56   35.03   37.61
Pier Skew, UpSta & Num, DnSta & Num=  ,4934.8, 2 ,4934.8, 2 , 0 , 0 , 0 ,,
     1.4     1.4
   13.12   27.77
     1.4     1.4
   13.17   27.82
Pier Skew, UpSta & Num, DnSta & Num=  ,4953.9, 2 ,4953.9, 2 , 0 , 0 , 0 ,,
     1.4     1.4
    8.46   27.76
     1.4     1.4
    8.51   27.81
Pier Skew, UpSta & Num, DnSta & Num=  ,4980.7, 2 ,4980.7, 2 , 0 , 0 , 0 ,,
     1.4     1.4
    6.66   27.73
     1.4     1.4
    6.71   27.78
Pier Skew, UpSta & Num, DnSta & Num=  ,4993.1, 2 ,4993.1, 2 , 0 , 0 , 0 ,,
     1.4     1.4
   -2.45   27.72
     1.4     1.4
    -2.4   27.77
Pier Skew, UpSta & Num, DnSta & Num=  ,5012.6, 2 ,5012.6, 2 , 0 , 0 , 0 ,,
     1.4     1.4
    2.95   27.69
     1.4     1.4
       3   27.74
Pier Skew, UpSta & Num, DnSta & Num=  ,5032.8, 2 ,5032.8, 2 , 0 , 0 , 0 ,,
     1.4     1.4
   13.12   27.68
     1.4     1.4
   13.17   27.73
Abutment Skew #Up #Dn= , 2 , 2
 4902.44 4910.38
   26.78   22.56
 4902.44 4910.38
   26.83   22.61
Abutment Skew #Up #Dn= , 2 , 2
 5034.24 5042.07
   15.08   26.67
 5034.24 5042.07
   15.13   26.72
BR Coef= 1 , 1 , 0 ,1.25, 0 ,,,0.8,0,2,0,
WSPro=,,,, 1 ,,,, 0 ,,,, 0 ,,,,-1 ,-1 ,-1 , 0 , 0 , 0 , 0 , 0
BR U #Sta/Elev= 133
    66.7   31.66    86.7   30.78   151.8   30.02   196.7   29.49   266.7   26.87
   476.7   26.09   496.7   26.65   556.7    26.9   616.7   27.25   651.8   26.67
   686.7   26.09   756.7   27.04   776.7   27.73   846.7   27.35   966.7   26.09
  1096.7   26.81  1116.7   27.14  1216.7   27.34  1236.7   26.95  1266.7   27.73
  1316.7    26.9  1346.7   27.54  1416.7    27.1  1456.7   27.64  1476.7   26.44
  1480.8   26.42  1796.7      25  1806.7    24.4  1846.7   25.31  1866.7   26.07
  2048.1   25.64  2258.1   25.17  2288.1   25.49  2318.1   25.21  2348.1   25.26
  2355.7   24.96  2358.1   24.87  2478.1   24.61  2538.1   23.98  2643.8   24.08
  2650.1   24.09  2833.8   24.14  2842.5   24.15  3031.4    24.2  3150.6   24.23
  3265.1   24.27  3450.1   24.32  3540.1   25.45  3580.1   24.26  3732.2   24.02
  3793.1   23.92  3873.1   23.61  3903.1   24.37  3973.5   24.31  4033.1   24.26
  4057.8   23.73  4157.8   24.96  4207.8   23.74  4317.8   25.33  4322.1   25.29
  4427.8   24.41  4437.8   24.59  4467.8   26.18  4594.7   26.41 4594.79   26.41
  4594.9   26.41 4595.01   26.41  4627.8   26.47  4655.6   26.15  4662.9   26.07
 4665.03   25.65  4696.2   26.58  4716.3   26.48 4730.98    26.4 4770.58   26.26
  4774.9   26.29 4807.04   26.48    4836   26.08 4849.63   25.89 4879.43   24.85
  4895.7   23.67 4902.55   23.18 4902.64   23.17 4910.22   22.62 4910.38   22.56
 4934.81   13.87 4938.49   16.64 4953.89    9.12 4954.35    12.3  4955.9   11.85
 4973.04    6.93 4981.16    7.78  4989.2    4.15 4993.11   -1.51 4999.08   -1.01
 5006.97    -.15 5012.64    4.53  5014.1    5.24 5018.77    7.53 5032.78   14.46
 5034.24   15.08 5041.87   18.33 5041.98   18.38 5059.52   25.85 5067.03   17.93
  5075.2   18.03  5096.9   18.31  5134.9   19.01 5146.15   19.22  5194.5   21.72
 5194.56   21.72 5229.49   26.21 5231.26   25.83 5239.68   25.57 5248.87   25.81
 5250.25   26.22  5254.2   24.49  5257.3   23.13  5265.7   24.03  5277.3   25.27
  5287.3   25.97  5307.6   25.89 5307.79   25.89  5307.9   25.89 5308.01   25.89
  5377.3   25.61  5447.3   26.67  5623.4   26.91  5813.4   25.73  5913.4   31.51
  5945.7   32.54  6056.7   34.98  6174.4   37.56
BR U #Mann= 6
    66.7      .2  3150.6      .1 4849.63    .035 5059.52     .14  5265.7      .1
  5945.7      .2
BR U Banks=4849.63,5059.52
BR D #Sta/Elev= 133
    66.7   31.71    86.7   30.83   151.8   30.07   196.7   29.54   266.7   26.92
   476.7   26.14   496.7    26.7   556.7   26.95   616.7    27.3   651.8   26.72
   686.7   26.14   756.7   27.09   776.7   27.78   846.7    27.4   966.7   26.14
  1096.7   26.86  1116.7   27.19  1216.7   27.39  1236.7      27  1266.7   27.78
  1316.7   26.95  1346.7   27.59  1416.7   27.15  1456.7   27.69  1476.7   26.49
  1480.8   26.47  1796.7   25.05  1806.7   24.45  1846.7   25.36  1866.7   26.12
  2048.1   25.69  2258.1   25.22  2288.1   25.54  2318.1   25.26  2348.1   25.31
  2355.7   25.01  2358.1   24.92  2478.1   24.66  2538.1   24.03  2643.8   24.13
  2650.1   24.14  2833.8   24.19  2842.5    24.2  3031.4   24.25  3150.6   24.28
  3265.1   24.32  3450.1   24.37  3540.1    25.5  3580.1   24.31  3732.2   24.07
  3793.1   23.97  3873.1   23.66  3903.1   24.42  3973.5   24.36  4033.1   24.31
  4057.8   23.78  4157.8   25.01  4207.8   23.79  4317.8   25.38  4322.1   25.34
  4427.8   24.46  4437.8   24.64  4467.8   26.23  4594.7   26.46 4594.79   26.46
  4594.9   26.46 4595.01   26.46  4627.8   26.52  4655.6    26.2  4662.9   26.12
 4665.03    25.7  4696.2   26.63  4716.3   26.53 4730.98   26.45 4770.58   26.31
  4774.9   26.34 4807.04   26.53    4836   26.13 4849.63   25.94 4879.43    24.9
  4895.7   23.72 4902.55   23.23 4902.64   23.22 4910.22   22.67 4910.38   22.61
 4934.81   13.92 4938.49   16.69 4953.89    9.17 4954.35   12.35  4955.9    11.9
 4973.04    6.98 4981.16    7.83  4989.2     4.2 4993.11   -1.46 4999.08    -.96
 5006.97     -.1 5012.64    4.58  5014.1    5.29 5018.77    7.58 5032.78   14.51
 5034.24   15.13 5041.87   18.38 5041.98   18.43 5059.52    25.9 5067.03   17.98
  5075.2   18.08  5096.9   18.36  5134.9   19.06 5146.15   19.27  5194.5   21.77
 5194.56   21.77 5229.49   26.26 5231.26   25.88 5239.68   25.62 5248.87   25.86
 5250.25   26.27  5254.2   24.54  5257.3   23.18  5265.7   24.08  5277.3   25.32
  5287.3   26.02  5307.6   25.94 5307.79   25.94  5307.9   25.94 5308.01   25.94
  5377.3   25.66  5447.3   26.72  5623.4   26.96  5813.4   25.78  5913.4   31.56
  5945.7   32.59  6056.7   35.03  6174.4   37.61
BR D #Mann= 6
    66.7      .2  3150.6      .1 4849.63    .035 5059.52     .14  5265.7      .1
  5945.7      .2
BR D Banks=4849.63,5059.52
BC Design=,, 0 ,, 0 ,,,,,,
BC HTab HWMax=37.87
BC Use User HTab Curves=0
BC User HTab FreeFlow(D)= 0

Type RM Length L Ch R = 1 ,24735.1 ,489.8,489.8,489.8
BEGIN DESCRIPTION:
Downstream Section of Bridge/Culvert/Weir
END DESCRIPTION:
XS GIS Cut Line= 6
      3169898.11     13847126.15      3167668.72     13846890.86
      3165679.91     13847234.48       3165019.6     13847365.85
      3164775.43     13847426.72      3163874.65     13847626.92
#Sta/Elev= 30
    66.7   34.32   266.7   29.53   476.7   28.75  1456.7    30.3  1806.7   27.06
  1866.7   28.73  3150.6   26.89 4849.63   28.55 4910.22   25.28 4934.81   16.53
 4938.49    19.3 4953.89   11.78 4954.35   14.96 4973.04    9.59 4981.16   10.44
  4989.2    6.81 4993.11    1.15 5006.97    2.51 5012.64    7.19 5059.52   28.51
 5067.03   20.59 5146.15   21.88 5194.56   24.38 5229.49   28.87  5265.7   26.69
  5287.3   28.63  5447.3   29.33  5813.4   28.39  5945.7    35.2  6174.4   40.22
#Mann= 6 , 1 , 0
    66.7      .2       0  3150.6      .1       0 4849.63    .035       0
 5059.52     .14       0  5265.7      .1       0  5945.7      .2       0
#XS Ineff= 2 , 0
       0    4890      26    5052       0      26
Permanent Ineff=
       F       F
Bank Sta=4849.63,5059.52
XS Rating Curve= 0 ,0
Exp/Cntr=0.5,0.3

Type RM Length L Ch R = 1 ,24245.3 ,68.5,599.3,733
BEGIN DESCRIPTION:
Cross Section 24245.3
END DESCRIPTION:
XS GIS Cut Line= 6
      3166584.57     13847068.54      3165758.65     13847154.47
      3165436.41     13847016.23      3165330.52     13846950.67
      3165098.57     13846890.17      3164476.87     13846833.35
#Sta/Elev= 30
  3584.9   27.25  4084.9      26  4169.9    24.7  4214.9    22.2  4319.9      22
  4374.9    21.2  4404.9    19.5  4454.9    11.7  4474.9    12.8  4489.9    16.1
  4504.9    18.2  4554.9    20.6  4569.9    22.8  4584.9    23.9    4766    26.7
  4812.4   25.57  4919.8    24.9  4970.6   10.92  4982.7    3.66  4984.3    1.93
  4994.1   -2.01  5015.7    2.41    5031   12.76  5145.4   12.05  5200.8    22.6
  5364.9    25.8  5469.9    26.3  5499.9    25.5  5739.9    26.5  5754.9    27.2
#Mann= 4 , 1 , 0
  3584.9      .2       0  4084.9      .1       0  4919.8    .045       0
  5200.8      .1       0
#XS Ineff= 2 , 0
       0    4730      26               0
Permanent Ineff=
       F       F
Bank Sta=4919.8,5200.8
XS Rating Curve= 0 ,0
Exp/Cntr=0.5,0.3

Type RM Length L Ch R = 1 ,23646.0 ,22,22,22
BEGIN DESCRIPTION:
Upstream Section of Bridge/Culvert/Weir
END DESCRIPTION:
XS GIS Cut Line= 6
      3166600.85      13847076.4      3165747.93      13847101.7
      3165425.75     13846936.14      3165349.14     13846502.99
      3165335.48     13846441.59      3165284.31     13846208.33
#Sta/Elev= 30
  3281.7   27.28  3781.7   25.63  3821.7   25.03  3866.7   22.53  4106.7   21.53
  4141.7   19.33  4161.7   16.83  4176.7   13.23  4196.7   10.53  4211.7   10.53
  4261.7   17.33  4296.7   19.13  4361.7   24.43  4517.3   25.63  4592.3   24.93
  4652.3   27.33  4682.3   24.93  4727.3   26.43  4841.1   25.45 4861.82   25.56
 4895.02   23.62 4989.02    2.86 4990.62    -.09 5001.12   -3.88 5010.92   -1.25
 5021.12    5.21 5107.72   27.99  5111.3   27.98  5217.2   26.33  5238.9   26.93
#Mann= 7 , 1 , 0
  3281.7      .2       0  3781.7      .1       0  4841.1     .14       0
 4895.02    .045       0 5107.72     .12       0  5111.3      .1       0
  5238.9      .2       0
#XS Ineff= 2 , 0
       0    4550      26               0
Permanent Ineff=
       F       F
Bank Sta=4895.02,5107.72
XS Rating Curve= 0 ,0
Exp/Cntr=0.5,0.3

Type RM Length L Ch R = 3 ,23635.0 ,,,
BEGIN DESCRIPTION:
Pipeline
END DESCRIPTION:
Bridge Culvert--1,0,-1,-1, 0
Deck Dist Width WeirC Skew NumUp NumDn MinLoCord MaxHiCord MaxSubmerge Is_Ogee
10,2,2.6,0, 60, 60, , , 0.95, 0, 1,1,,
  3281.7  3781.7  3821.7  3866.7  3931.7  3976.7  4106.7  4111.7  4121.7  4126.7
  4141.7  4161.7  4176.7  4186.7  4191.7  4196.7  4211.7  4221.7  4226.7  4246.7
  4261.7  4296.7  4316.7  4331.7  4346.7  4356.7  4361.7  4497.3  4517.3  4592.3
  4607.3  4632.3  4652.3  4657.3  4682.3  4697.3  4707.3  4727.3  4837.3  4841.1
 4861.82 4895.02 4955.83 4955.92 4964.92 4989.02 4990.62 5001.12 5010.92 5021.12
 5042.52 5052.41 5052.52 5107.72  5111.3 5142.32  5172.2  5187.2  5217.2  5238.9
   27.25    25.6      25    22.5    21.9    22.6    21.5    21.3    20.6    20.6
    19.3    16.8    13.2    12.1    10.9    10.5    10.5    11.9    12.2    15.6
    17.3    19.1      21    22.7    23.9      24    24.4    25.3    25.6    24.9
    25.1    27.1    27.3    27.2    24.9    24.9    25.4    26.4    25.4   25.42
   25.53   23.59   10.16   10.14    9.75   10.69   10.76   11.17   11.55   11.95
   12.79   13.41   13.44   27.96   27.95    27.9    26.9      27    26.3    26.9
   27.25    25.6      25    22.5    21.9    22.6    21.5    21.3    20.6    20.6
    19.3    16.8    13.2    12.1    10.9    10.5    10.5    11.9    12.2    15.6
    17.3    19.1      21    22.7    23.9      24    24.4    25.3    25.6    24.9
    25.1    27.1    27.3    27.2    24.9    24.9    25.4    26.4    25.4   25.42
   25.53   23.59   10.16   10.14    8.15    8.69    8.76    9.17    9.55    9.95
   10.81   13.41   13.44   27.96   27.95    27.9    26.9      27    26.3    26.9
  3281.7  3781.7  3821.7  3866.7  3931.7  3976.7  4106.7  4111.7  4121.7  4126.7
  4141.7  4161.7  4176.7  4186.7  4191.7  4196.7  4211.7  4221.7  4226.7  4246.7
  4261.7  4296.7  4316.7  4331.7  4346.7  4356.7  4361.7  4497.3  4517.3  4592.3
  4607.3  4632.3  4652.3  4657.3  4682.3  4697.3  4707.3  4727.3  4837.3  4841.1
 4861.82 4895.02 4955.83 4955.92 4964.92 4989.02 4990.62 5001.12 5010.92 5021.12
 5042.52 5052.41 5052.52 5107.72  5111.3 5142.32  5172.2  5187.2  5217.2  5238.9
   27.25    25.6      25    22.5    21.9    22.6    21.5    21.3    20.6    20.6
    19.3    16.8    13.2    12.1    10.9    10.5    10.5    11.9    12.2    15.6
    17.3    19.1      21    22.7    23.9      24    24.4    25.3    25.6    24.9
    25.1    27.1    27.3    27.2    24.9    24.9    25.4    26.4    25.4   25.42
   25.53   23.59   10.16   10.14    9.75   10.69   10.76   11.17   11.55   11.95
   12.79   13.41   13.44   27.96   27.95    27.9    26.9      27    26.3    26.9
   27.25    25.6      25    22.5    21.9    22.6    21.5    21.3    20.6    20.6
    19.3    16.8    13.2    12.1    10.9    10.5    10.5    11.9    12.2    15.6
    17.3    19.1      21    22.7    23.9      24    24.4    25.3    25.6    24.9
    25.1    27.1    27.3    27.2    24.9    24.9    25.4    26.4    25.4   25.42
   25.53   23.59   10.16   10.14    8.15    8.69    8.76    9.17    9.55    9.95
   10.81   13.41   13.44   27.96   27.95    27.9    26.9      27    26.3    26.9
BR Coef= 1 , 1 , 0 ,1.25, 0 ,,,0.8,0,2,0,
WSPro=,,,, 1 ,,,, 0 ,,,, 0 ,,,,-1 ,-1 ,-1 , 0 , 0 , 0 , 0 , 0
BR U #Sta/Elev= 60
  3281.7   27.25  3781.7    25.6  3821.7      25  3866.7    22.5  3931.7    21.9
  3976.7    22.6  4106.7    21.5  4111.7    21.3  4121.7    20.6  4126.7    20.6
  4141.7    19.3  4161.7    16.8  4176.7    13.2  4186.7    12.1  4191.7    10.9
  4196.7    10.5  4211.7    10.5  4221.7    11.9  4226.7    12.2  4246.7    15.6
  4261.7    17.3  4296.7    19.1  4316.7      21  4331.7    22.7  4346.7    23.9
  4356.7      24  4361.7    24.4  4497.3    25.3  4517.3    25.6  4592.3    24.9
  4607.3    25.1  4632.3    27.1  4652.3    27.3  4657.3    27.2  4682.3    24.9
  4697.3    24.9  4707.3    25.4  4727.3    26.4  4837.3    25.4  4841.1   25.42
 4861.82   25.53 4895.02   23.59 4955.83   10.16 4955.92   10.14 4964.92    8.15
 4989.02    2.83 4990.62    -.12 5001.12   -3.91 5010.92   -1.28 5021.12    5.18
 5042.52   10.81 5052.41   13.41 5052.52   13.44 5107.72   27.96  5111.3   27.95
 5142.32    27.9  5172.2    26.9  5187.2      27  5217.2    26.3  5238.9    26.9
BR U #Mann= 7
  3281.7      .2  3781.7      .1  4841.1     .14 4895.02    .045 5107.72     .12
  5111.3      .1  5238.9      .2
BR U Banks=4895.02,5107.72
BR D #Sta/Elev= 60
  3281.7   27.25  3781.7    25.6  3821.7      25  3866.7    22.5  3931.7    21.9
  3976.7    22.6  4106.7    21.5  4111.7    21.3  4121.7    20.6  4126.7    20.6
  4141.7    19.3  4161.7    16.8  4176.7    13.2  4186.7    12.1  4191.7    10.9
  4196.7    10.5  4211.7    10.5  4221.7    11.9  4226.7    12.2  4246.7    15.6
  4261.7    17.3  4296.7    19.1  4316.7      21  4331.7    22.7  4346.7    23.9
  4356.7      24  4361.7    24.4  4497.3    25.3  4517.3    25.6  4592.3    24.9
  4607.3    25.1  4632.3    27.1  4652.3    27.3  4657.3    27.2  4682.3    24.9
  4697.3    24.9  4707.3    25.4  4727.3    26.4  4837.3    25.4  4841.1   25.42
 4861.82   25.53 4895.02   23.59 4955.83   10.16 4955.92   10.14 4964.92    8.15
 4989.02    2.83 4990.62    -.12 5001.12   -3.91 5010.92   -1.28 5021.12    5.18
 5042.52   10.81 5052.41   13.41 5052.52   13.44 5107.72   27.96  5111.3   27.95
 5142.32    27.9  5172.2    26.9  5187.2      27  5217.2    26.3  5238.9    26.9
BR D #Mann= 7
  3281.7      .2  3781.7      .1  4841.1     .14 4895.02    .045 5107.72     .12
  5111.3      .1  5238.9      .2
BR D Banks=4895.02,5107.72
BC Design=,, 0 ,, 0 ,,,,,,
BC HTab HWMax=27.99
BC Use User HTab Curves=0
BC User HTab FreeFlow(D)= 0

Type RM Length L Ch R = 1 ,23624.0 ,350.9,350.9,350.9
BEGIN DESCRIPTION:
Downstream Section of Bridge/Culvert/Weir
END DESCRIPTION:
XS GIS Cut Line= 6
      3166622.55     13847072.78      3165769.63     13847098.08
      3165447.45     13846932.52      3165370.84     13846499.37
      3165357.18     13846437.97      3165306.01     13846204.71
#Sta/Elev= 30
  3281.7   27.31  3781.7   25.66  3821.7   25.06  3866.7   22.56  4106.7   21.56
  4141.7   19.36  4161.7   16.86  4176.7   13.26  4196.7   10.56  4211.7   10.56
  4261.7   17.36  4296.7   19.16  4361.7   24.46  4517.3   25.66  4592.3   24.96
  4652.3   27.36  4682.3   24.96  4727.3   26.46  4841.1   25.48 4861.82   25.59
 4895.02   23.65 4989.02    2.89 4990.62    -.06 5001.12   -3.85 5010.92   -1.22
 5021.12    5.24 5107.72   28.02  5111.3   28.01  5217.2   26.36  5238.9   26.96
#Mann= 7 , 1 , 0
  3281.7      .2       0  3781.7      .1       0  4841.1     .14       0
 4895.02    .045       0 5107.72     .12       0  5111.3      .1       0
  5238.9      .2       0
#XS Ineff= 2 , 0
       0    4550      26               0
Permanent Ineff=
       F       F
Bank Sta=4895.02,5107.72
XS Rating Curve= 0 ,0
Exp/Cntr=0.5,0.3

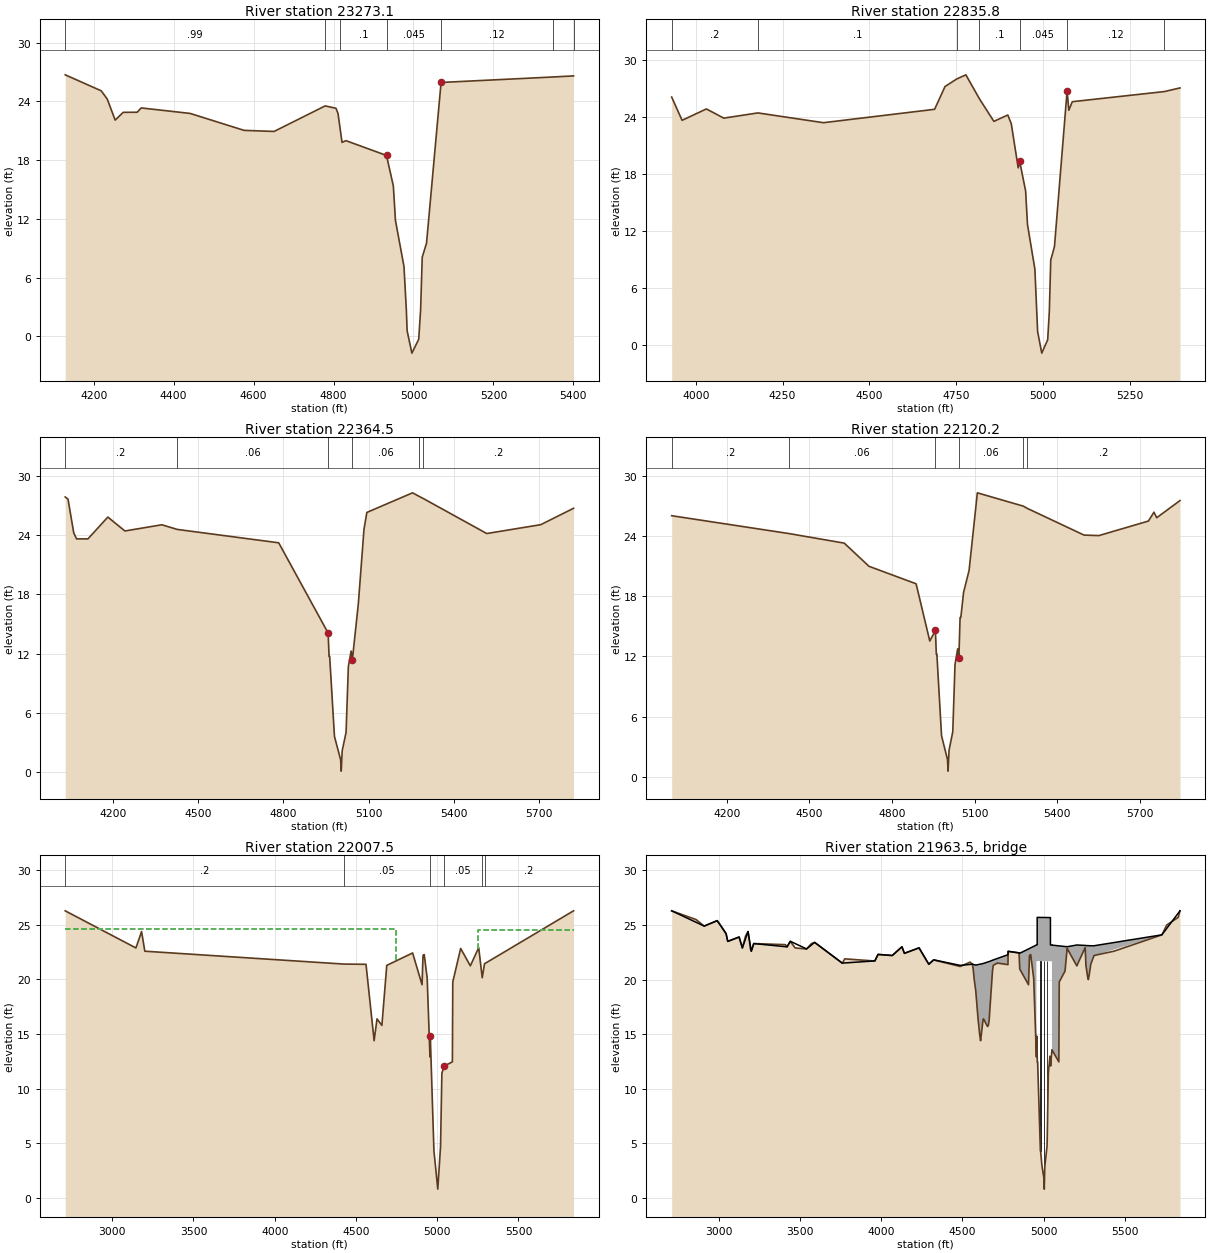
Type RM Length L Ch R = 1 ,23273.1 ,419.6,437.3,265.4
BEGIN DESCRIPTION:
Cross Section 23273.1
END DESCRIPTION:
XS GIS Cut Line= 5
      3166329.73     13847088.77      3165784.69     13846822.91
      3165654.63     13846670.92      3165668.21     13846431.05
      3165595.72     13846218.31
#Sta/Elev= 30
  4128.9    26.7  4218.9   25.07  4233.9   24.24  4253.9   22.08  4273.9   22.87
  4308.9   22.88  4318.9   23.32  4441.3   22.76  4576.3   21.03  4651.3   20.92
  4779.2   23.53  4806.3   23.28  4811.3   22.74  4816.4   21.24  4821.3    19.8
    4831   19.98  4932.5   18.47  4949.6   15.36  4954.9   11.84  4976.2    7.14
  4982.2    2.66  4984.1     .57    4996   -1.71  5013.1     -.3  5017.8    2.68
  5021.9    8.09  5032.6    9.51    5069   25.92  5349.2   26.48  5400.3   26.59
#Mann= 7 , 1 , 0
  4128.9     .99       0  4779.2     .14       0  4816.4      .1       0
  4932.5    .045       0    5069     .12       0  5349.2      .1       0
  5400.3      .2       0
Bank Sta=4932.5,5069
XS Rating Curve= 0 ,0
Exp/Cntr=0.3,0.1

Type RM Length L Ch R = 1 ,22835.8 ,370.3,471.3,442.3
BEGIN DESCRIPTION:
Cross Section 22835.8
END DESCRIPTION:
XS GIS Cut Line= 6
      3166680.56     13847084.57      3166445.81     13846871.82
      3166000.92     13846498.73      3165874.01     13846288.38
      3165729.72     13846236.23      3165568.04     13846196.24
#Sta/Elev= 30
  3930.8   26.11  3960.8   23.66  4030.8   24.86  4080.8   23.89  4178.9   24.44
  4367.6   23.41  4687.6   24.82  4717.6   27.22  4751.2   28.01  4777.6   28.45
  4816.4   25.94  4858.2   23.55  4898.2   24.22  4908.2   23.32  4928.2   18.66
  4932.5   19.33  4949.6   16.22  4954.9    12.7  4976.2       8  4984.1    1.43
    4996    -.85  5013.1     .56  5017.8    3.54  5021.9    8.95  5032.6   10.37
    5069   26.78  5073.9   24.72  5083.9   25.62  5349.2   26.69  5393.9   27.07
#Mann= 7 , 1 , 0
  3930.8      .2       0  4178.9      .1       0  4751.2     .14       0
  4816.4      .1       0  4932.5    .045       0    5069     .12       0
  5349.2      .1       0
Bank Sta=4932.5,5069
XS Rating Curve= 0 ,0
Exp/Cntr=0.3,0.1

Type RM Length L Ch R = 1 ,22364.5 ,286.6,244.3,174.5
BEGIN DESCRIPTION:
Cross Section 22364.5
END DESCRIPTION:
XS GIS Cut Line= 6
      3166997.61     13847029.68      3166833.09     13846719.59
      3166235.61     13846232.75        3166140.     13846191.03
      3165983.54     13846182.34      3165578.48     13846192.77
#Sta/Elev= 30
  4032.5   27.89  4042.5   27.66  4062.5   24.25  4072.5   23.64  4112.5   23.64
  4182.5   25.85  4242.5   24.44  4372.5   25.07  4426.3    24.6  4783.5   23.24
  4957.3   14.09  4960.7   11.71  4962.7   11.73  4979.6     3.6  5001.2    1.24
  5003.3     .08  5006.8    2.15  5020.4    4.01  5028.5    10.7  5038.2   12.26
  5042.5   11.36  5063.5   17.04  5083.5   24.63  5093.5   26.32  5254.3   28.31
  5276.8   27.96  5290.9   27.75  5515.3   24.18  5705.3   25.08  5820.5   26.74
#Mann= 6 , 1 , 0
  4032.5      .2       0  4426.3     .06       0  4957.3    .045       0
  5042.5     .06       0  5276.8      .1       0  5290.9      .2       0
Bank Sta=4957.3,5042.5
XS Rating Curve= 0 ,0
Exp/Cntr=0.3,0.1

Type RM Length L Ch R = 1 ,22120.2 ,168.1,112.7,107.5
BEGIN DESCRIPTION:
Cross Section 22120.2
END DESCRIPTION:
XS GIS Cut Line= 6
      3167022.69     13846799.76      3166830.06     13846459.77
      3166451.51     13846096.02      3166319.02     13846101.91
      3166051.09     13846169.63       3165532.9     13846184.35
#Sta/Elev= 30
    4000      26  4426.3   24.22  4626.4   23.27  4716.4   20.96  4887.3   19.22
  4936.9   13.52  4957.3   14.57  4960.7   12.19  4962.7   12.21  4979.6    4.08
  5001.2    1.72  5003.3     .56  5006.8    2.63  5020.4    4.49  5028.5   11.18
  5038.2   12.74  5042.5   11.84  5046.9   15.86  5049.6   15.86  5059.6   18.36
  5079.6   20.55  5109.6   28.28  5276.8   26.95  5290.9   26.73  5496.8   24.07
  5550.7   24.02  5730.7   25.47  5750.7   26.35  5760.7    25.8  5845.2   27.51
#Mann= 6 , 1 , 0
    4000      .2       0  4426.3     .06       0  4957.3    .045       0
  5042.5     .06       0  5276.8      .1       0  5290.9      .2       0
Bank Sta=4957.3,5042.5
XS Rating Curve= 0 ,0
Exp/Cntr=0.5,0.3

Type RM Length L Ch R = 1 ,22007.5 ,88,88,88
BEGIN DESCRIPTION:
Upstream Section of Bridge/Culvert/Weir
END DESCRIPTION:
XS GIS Cut Line= 6
      3168470.31     13846494.57      3167277.25     13845862.98
      3166884.42     13845874.29      3166467.04     13845974.27
      3166099.48     13846068.98      3165528.57     13846148.24
#Sta/Elev= 30
  2710.6   26.28  3145.6   22.88  3180.6   24.38  3200.6   22.58  4426.3    21.4
  4561.6   21.38  4611.6   14.38  4629.4   16.38  4659.4   15.78  4689.4   21.28
  4848.5   22.42  4906.5   19.51  4912.5   22.19  4919.9   22.27  4938.1   20.13
  4955.3   12.89  4957.3   14.79  4979.6     4.3  5003.3     .78  5020.4    4.71
  5028.5    11.4  5042.5   12.06  5093.2   12.44  5095.6   19.76  5144.2   22.83
  5203.7   21.24  5255.2   22.91  5276.8   20.15  5290.9   21.43  5838.7   26.28
#Mann= 6 , 1 , 0
  2710.6      .2       0  4426.3     .05       0  4957.3    .045       0
  5042.5     .05       0  5276.8      .1       0  5290.9      .2       0
#XS Ineff= 2 , 0
       0    4745   24.57    5250       0    24.5
Permanent Ineff=
       F       F
Bank Sta=4957.3,5042.5
XS Rating Curve= 0 ,0
Exp/Cntr=0.5,0.3

Type RM Length L Ch R = 3 ,21963.5 ,,,
BEGIN DESCRIPTION:
MARKET STREET
Structure ID: H00-10
END DESCRIPTION:
Bridge Culvert--1,0,-1,-1, 0
Deck Dist Width WeirC Skew NumUp NumDn MinLoCord MaxHiCord MaxSubmerge Is_Ogee
10,68,2.6,0, 60, 60, , , 0.95, 0, 1,1,,
  2710.6  2910.6  2990.6  3045.6  3055.6  3125.6  3145.6  3180.6  3200.6  3215.6
  3420.6  3440.6  3540.6  3590.6  3760.6  3960.6  3980.6  4067.8  4127.8  4142.8
  4232.8  4292.8  4322.8  4486.6  4561.6  4581.6  4611.6  4629.4  4659.4  4664.4
  4689.4  4780.2  4780.8  4848.5  4852.6  4906.5  4912.5  4919.9  4938.1  4955.1
  4955.2 4959.79  4959.9  5041.4 5041.51  5050.6 5050.69  5050.8  5093.2  5095.6
  5131.2  5144.2  5203.7  5255.2  5259.7  5274.7  5289.7  5309.7  5727.2  5838.7
    26.3    24.9    25.4    24.2    23.5    23.9    22.9    24.4    22.6    23.3
      23   23.51   22.81   23.41   21.51   21.71   22.31   22.21   23.01   22.41
   22.91   21.41   21.81    21.3   21.41   21.33   21.42   21.48   21.63   21.65
    21.8   22.28   22.59   22.45   22.41   22.81   22.85   22.91   23.04   23.17
   23.17    23.2    25.7   25.68   23.18   23.17   23.16   23.16   23.09   23.09
   23.03   23.01   23.17   23.13   23.12   23.11    23.1    23.1    24.1    26.3
    26.3    24.9    25.4    24.2    23.5    23.9    22.9    24.4    22.6    23.3
      23    23.5    22.8    23.4    21.5    21.7    22.3    22.2      23    22.4
    22.9    21.4    21.8    21.2    21.4      19    14.4    16.4    15.8    16.3
    21.3   21.37   22.58   22.44   20.96   19.53   22.21   22.29   20.15   12.99
   21.67    21.7    21.7   21.68   21.68   21.67   21.66   13.56   12.46   19.78
   20.77   22.85   21.26   22.93    21.3      20    21.4    22.2    24.1    26.3
  2710.6  2910.6  2990.6  3045.6  3055.6  3125.6  3145.6  3180.6  3200.6  3215.6
  3420.6  3440.6  3540.6  3590.6  3760.6  3960.6  3980.6  4067.8  4127.8  4142.8
  4232.8  4292.8  4322.8  4486.6  4561.6  4581.6  4611.6  4629.4  4659.4  4664.4
  4689.4  4780.2  4780.8  4848.5  4852.6  4906.5  4912.5  4919.9  4938.1  4955.1
  4955.2 4959.79  4959.9  5041.4 5041.51  5050.6 5050.69  5050.8  5093.2  5095.6
  5131.2  5144.2  5203.7  5255.2  5259.7  5274.7  5289.7  5309.7  5727.2  5838.7
    26.3    24.9    25.4    24.2    23.5    23.9    22.9    24.4    22.6    23.3
      23   23.51   22.81   23.41   21.51   21.71   22.31   22.21   23.01   22.41
   22.91   21.41   21.81    21.3   21.41   21.33   21.42   21.48   21.63   21.65
    21.8   22.28   22.59   22.45   22.41   22.81   22.85   22.91   23.04   23.17
   23.17    23.2    25.7   25.68   23.18   23.17   23.16   23.16   23.09   23.09
   23.03   23.01   23.17   23.13   23.12   23.11    23.1    23.1    24.1    26.3
    26.1    24.7    25.2      24    23.3    23.7    22.7    24.2    22.4    23.1
    22.8    23.3    22.6    23.2    21.3    21.5    22.1      22    22.8    22.2
    22.7    21.2    21.6      21    21.2    18.8    14.2    16.2    15.6    16.1
    21.1   21.17   22.38   22.24   20.76   19.33   22.01   22.09   19.95   12.79
   21.47    21.5    21.5   21.48   21.48   21.47   21.46   13.36   12.26   19.58
   20.57   22.65   21.06   22.73    21.1    19.8    21.2      22    23.9    26.1
Pier Skew, UpSta & Num, DnSta & Num=  ,4980.8, 2 ,4980.8, 2 , 0 , 0 , 0 ,,
       2       2
    3.16    22.7
       2       2
    2.96    22.5
Pier Skew, UpSta & Num, DnSta & Num=  ,5001.2, 2 ,5001.2, 2 , 0 , 0 , 0 ,,
       2       2
     .41   22.69
       2       2
     .21   22.49
Pier Skew, UpSta & Num, DnSta & Num=  ,5021.5, 2 ,5021.5, 2 , 0 , 0 , 0 ,,
       2       2
    3.78   22.69
       2       2
    3.58   22.49
BR Coef= 1 , 1 , 0 ,1.25, 0 ,,,0.8,-1,2,0,
WSPro=,,,, 1 ,,,, 0 ,,,, 0 ,,,,-1 ,-1 ,-1 , 0 , 0 , 0 , 0 , 0
BR U #Sta/Elev= 115
  2710.6    26.3  2860.6    25.5  2910.6    24.9  2990.6    25.4  3015.6    24.9
  3045.6    24.2  3055.6    23.5  3125.6    23.9  3145.6    22.9  3165.6      24
  3180.6    24.4  3195.6    22.8  3200.6    22.6  3215.6    23.3  3410.6    23.2
  3420.6      23  3426.3   23.14  3440.6    23.5  3470.6    22.9  3540.6    22.8
  3570.6    23.3  3590.6    23.4  3760.6    21.5  3775.6    21.9  3960.6    21.7
  3980.6    22.3  4067.8    22.2  4127.8      23  4142.8    22.4  4232.8    22.9
  4292.8    21.4  4322.8    21.8  4426.3   21.42  4486.6    21.2  4546.6    21.6
  4561.6    21.4  4566.6    20.9  4571.6    20.1  4572.5      20  4581.6      19
  4596.6    16.3  4606.6    14.9  4611.6    14.4  4626.6    16.3  4629.4    16.4
  4637.5   16.17  4654.4    15.7  4659.4    15.8  4664.4    16.3  4684.4    20.7
  4689.4    21.3  4715.1   21.51  4716.2   21.51  4780.2   21.37  4780.8   22.58
  4783.1   22.58  4848.5   22.44  4848.7   22.37  4852.6   20.96  4906.5   19.53
  4912.5   22.21  4919.9   22.29  4938.1   20.15 4955.01   13.03  4955.1   12.99
  4955.2   12.95  4955.3   12.91  4957.3   14.81 4959.79   13.07  4959.9   12.99
 4960.01   12.91  4960.7   12.43  4962.7   12.45  4979.6    4.32  4980.8    4.33
  4988.3    3.05  4999.5    1.95  5001.2    1.96  5003.3      .8  5006.8    2.87
  5020.4    4.73  5021.5    5.33  5028.5   11.42  5038.2   12.98 5041.29   12.33
  5041.4   12.31 5041.51   12.29  5042.5   12.08  5050.5   13.55  5050.6   13.57
 5050.69   13.57  5050.8   13.56  5093.2   12.46  5095.6   19.78  5131.2   20.77
  5144.2   22.85  5144.6   22.84  5202.1    21.3  5203.7   21.26  5255.2   22.93
  5259.7    21.3  5269.7    20.3  5274.7      20  5276.8   20.17  5279.7    20.4
  5289.7    21.4  5290.9   21.45  5309.7    22.2  5338.3    22.3  5432.2    22.6
  5476.3   22.82  5727.2    24.1  5757.2      25  5827.2    25.7  5838.7    26.3
BR U #Mann= 6
  2710.6      .2  4426.3     .05  4957.3    .045  5042.5     .05  5276.8      .1
  5290.9      .2
BR U Banks=4957.3,5042.5
BR D #Sta/Elev= 115
  2710.6    26.1  2860.6    25.3  2910.6    24.7  2990.6    25.2  3015.6    24.7
  3045.6      24  3055.6    23.3  3125.6    23.7  3145.6    22.7  3165.6    23.8
  3180.6    24.2  3195.6    22.6  3200.6    22.4  3215.6    23.1  3410.6      23
  3420.6    22.8  3426.3   22.94  3440.6    23.3  3470.6    22.7  3540.6    22.6
  3570.6    23.1  3590.6    23.2  3760.6    21.3  3775.6    21.7  3960.6    21.5
  3980.6    22.1  4067.8      22  4127.8    22.8  4142.8    22.2  4232.8    22.7
  4292.8    21.2  4322.8    21.6  4426.3   21.22  4486.6      21  4546.6    21.4
  4561.6    21.2  4566.6    20.7  4571.6    19.9  4572.5    19.8  4581.6    18.8
  4596.6    16.1  4606.6    14.7  4611.6    14.2  4626.6    16.1  4629.4    16.2
  4637.5   15.97  4654.4    15.5  4659.4    15.6  4664.4    16.1  4684.4    20.5
  4689.4    21.1  4715.1   21.31  4716.2   21.31  4780.2   21.17  4780.8   22.38
  4783.1   22.38  4848.5   22.24  4848.7   22.17  4852.6   20.76  4906.5   19.33
  4912.5   22.01  4919.9   22.09  4938.1   19.95 4955.01   12.83  4955.1   12.79
  4955.2   12.75  4955.3   12.71  4957.3   14.61 4959.79   12.87  4959.9   12.79
 4960.01   12.71  4960.7   12.23  4962.7   12.25  4979.6    4.12  4980.8    4.13
  4988.3    2.85  4999.5    1.75  5001.2    1.76  5003.3      .6  5006.8    2.67
  5020.4    4.53  5021.5    5.13  5028.5   11.22  5038.2   12.78 5041.29   12.13
  5041.4   12.11 5041.51   12.09  5042.5   11.88  5050.5   13.35  5050.6   13.37
 5050.69   13.37  5050.8   13.36  5093.2   12.26  5095.6   19.58  5131.2   20.57
  5144.2   22.65  5144.6   22.64  5202.1    21.1  5203.7   21.06  5255.2   22.73
  5259.7    21.1  5269.7    20.1  5274.7    19.8  5276.8   19.97  5279.7    20.2
  5289.7    21.2  5290.9   21.25  5309.7      22  5338.3    22.1  5432.2    22.4
  5476.3   22.62  5727.2    23.9  5757.2    24.8  5827.2    25.5  5838.7    26.1
BR D #Mann= 6
  2710.6      .2  4426.3     .05  4957.3    .045  5042.5     .05  5276.8      .1
  5290.9      .2
BR D Banks=4957.3,5042.5
BC Design=,, 0 ,, 0 ,,,,,,
BC HTab HWMax=26.28
BC Use User HTab Curves=0
BC User HTab FreeFlow(D)= 0