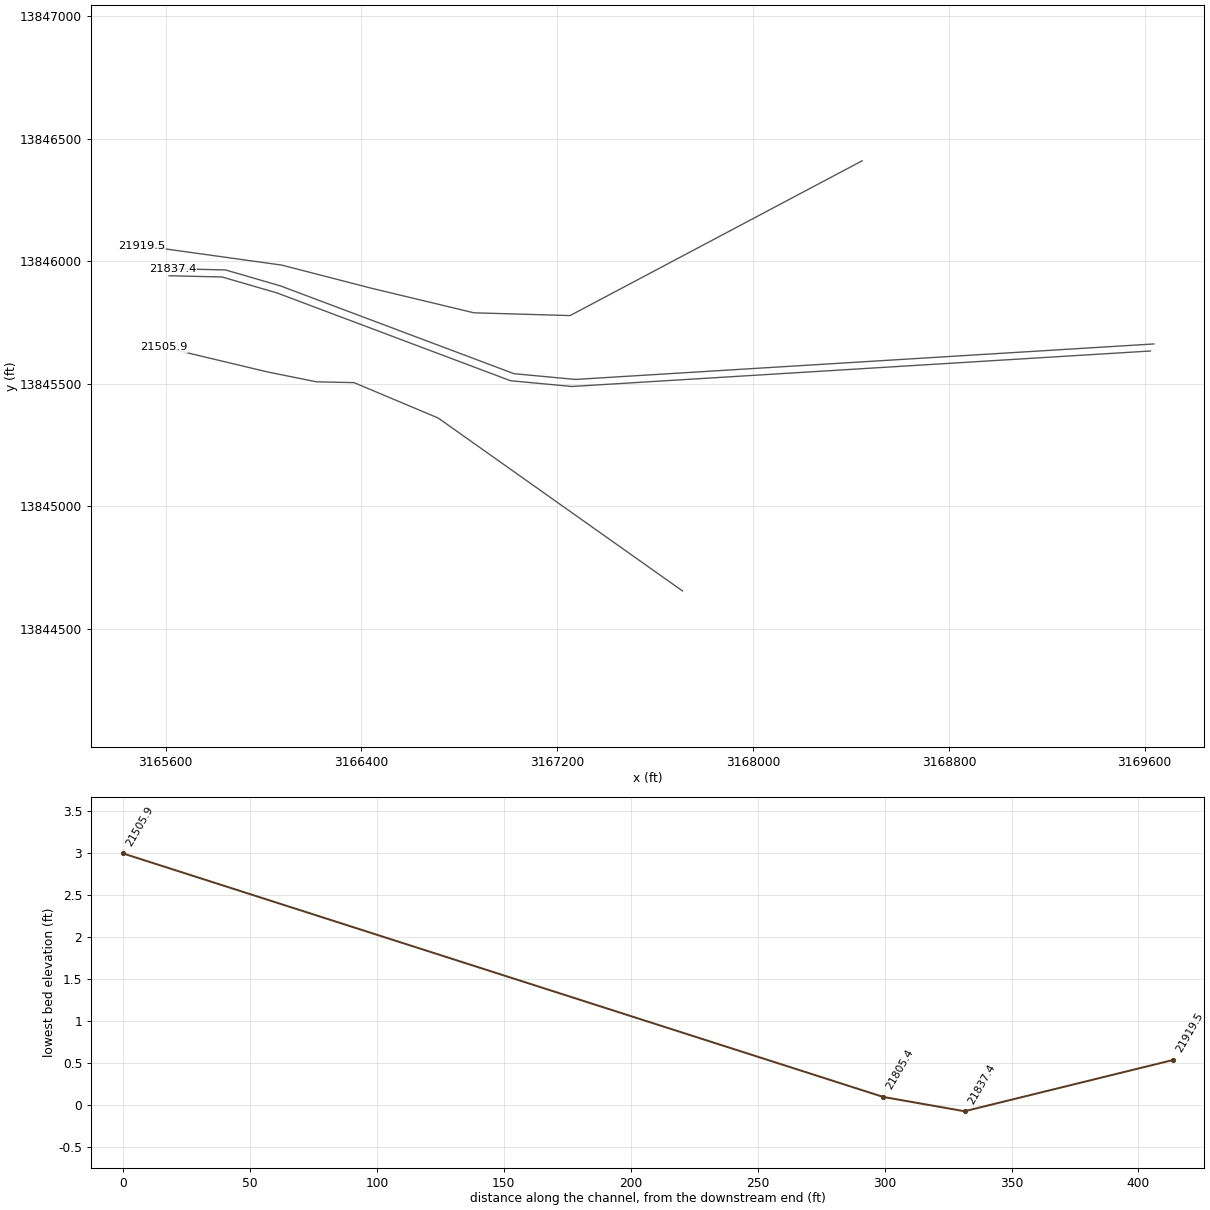
HEC-RAS study H100-00-00.prj: H100-00-00

--- H100-00-00.g01 (geometry) --- (continued)

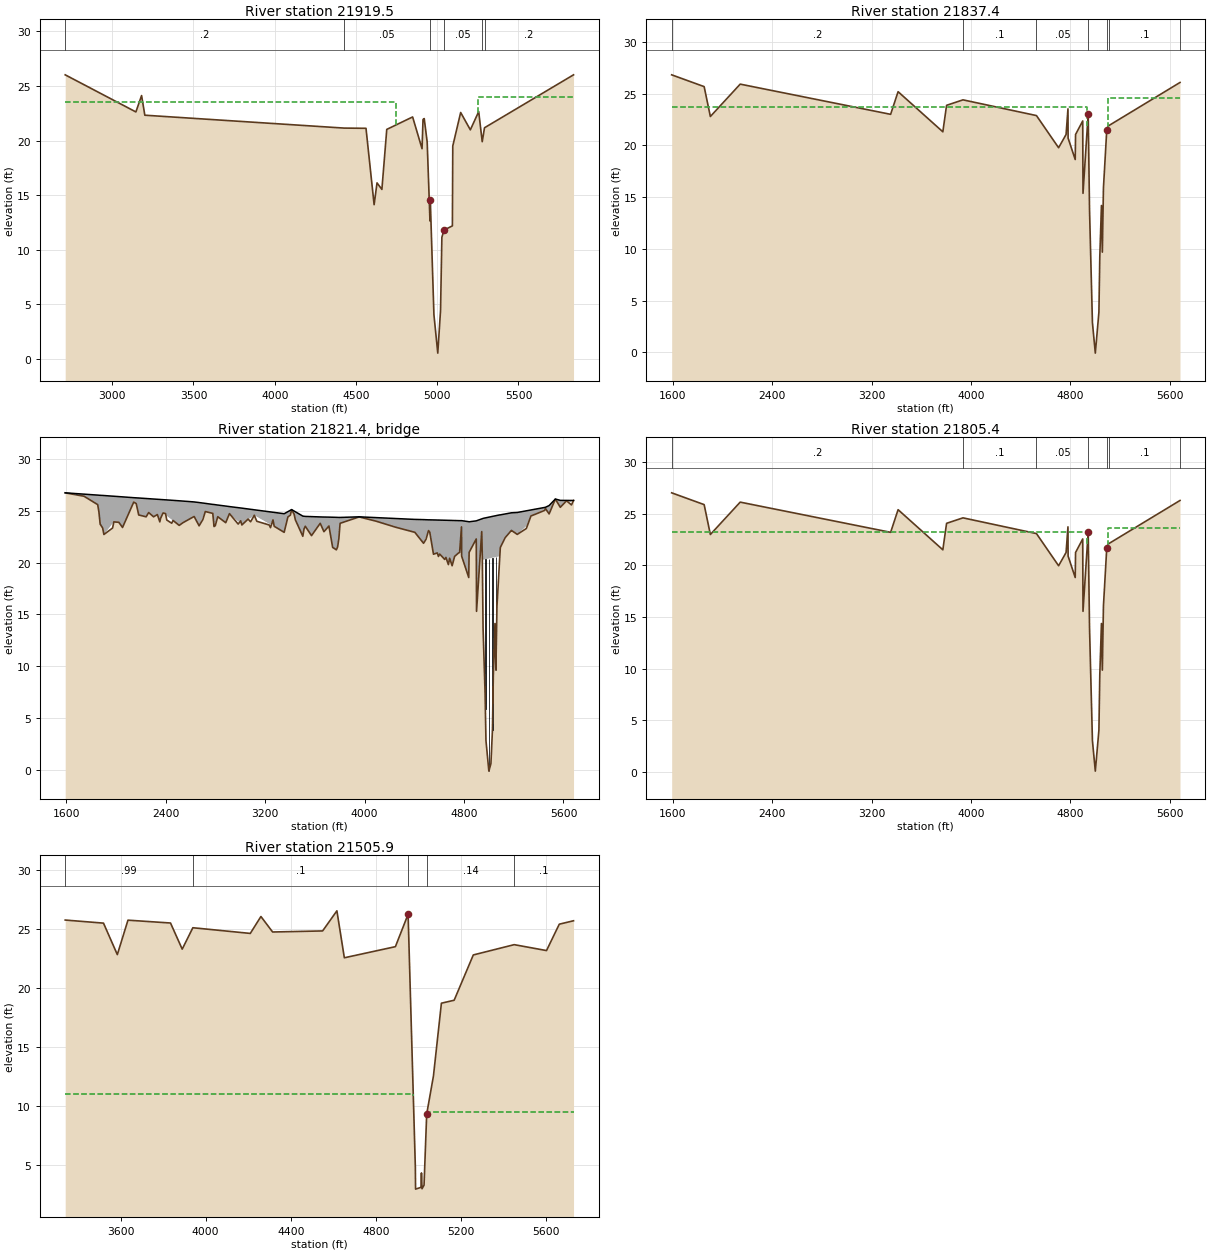
Type RM Length L Ch R = 1 ,21919.5 ,82.1,82.1,82.1
BEGIN DESCRIPTION:
Downstream Section of Bridge/Culvert/Weir
END DESCRIPTION:
XS GIS Cut Line= 6
      3168445.78     13846410.06      3167252.71     13845778.46
      3166859.88     13845789.77       3166442.5     13845889.75
      3166074.94     13845984.46      3165504.04     13846063.73
#Sta/Elev= 30
  2710.6   26.03  3145.6   22.63  3180.6   24.13  3200.6   22.33  4426.3   21.15
  4561.6   21.13  4611.6   14.13  4629.4   16.13  4659.4   15.53  4689.4   21.03
  4848.5   22.17  4906.5   19.26  4912.5   21.94  4919.9   22.02  4938.1   19.88
  4955.3   12.64  4957.3   14.54  4979.6    4.05  5003.3     .53  5020.4    4.46
  5028.5   11.15  5042.5   11.81  5093.2   12.19  5095.6   19.51  5144.2   22.58
  5203.7   20.99  5255.2   22.66  5276.8    19.9  5290.9   21.18  5838.7   26.03
#Mann= 6 , 1 , 0
  2710.6      .2       0  4426.3     .05       0  4957.3    .045       0
  5042.5     .05       0  5276.8      .1       0  5290.9      .2       0
#XS Ineff= 2 , 0
       0    4745   23.57    5250       0      24
Permanent Ineff=
       F       F
Bank Sta=4957.3,5042.5
XS Rating Curve= 0 ,0
Exp/Cntr=0.5,0.3

Type RM Length L Ch R = 1 ,21837.4 ,32,32,32
BEGIN DESCRIPTION:
Upstream Section of Bridge/Culvert/Weir
END DESCRIPTION:
XS GIS Cut Line= 6
      3169637.47     13845662.72      3167274.38     13845517.88
      3167023.33     13845541.41      3166069.71     13845899.58
      3165844.94     13845964.76      3165628.81     13845969.67
#Sta/Elev= 30
    1592   26.83  1853.2   25.69  1903.2    22.8  2143.2   25.93  3353.3   23.01
  3413.3    25.2  3773.3   21.32  3803.3   23.88  3935.3   24.41  4526.3   22.89
  4704.5   19.78  4764.6   21.06  4779.8   23.54  4780.9   20.71  4838.2   18.64
  4840.9   21.06  4898.5   22.37  4900.8   15.37  4942.5   23.08  4953.3   13.76
  4976.6    2.87  4999.8    -.08  5028.7    3.88  5035.8     9.2    5049   14.19
  5056.4    9.69  5065.2   15.88    5092   21.54  5107.1   21.91    5681   26.09
#Mann= 7 , 1 , 0
    1592      .2       0  3935.3      .1       0  4526.3     .05       0
  4942.5    .045       0    5092     .05       0  5107.1      .1       0
    5681      .2       0
#XS Ineff= 2 , 0
       0    4936    23.7    5100       0    24.6
Permanent Ineff=
       F       F
Bank Sta=4942.5,5092
XS Rating Curve= 0 ,0
Exp/Cntr=0.5,0.3

Type RM Length L Ch R = 3 ,21821.4 ,,,
BEGIN DESCRIPTION:
Union Pacific Railroad
Structure ID: H00-8A
END DESCRIPTION:
Bridge Culvert--1,0,-1,-1, 0
Deck Dist Width WeirC Skew NumUp NumDn MinLoCord MaxHiCord MaxSubmerge Is_Ogee
10,12,2.6,0, 60, 60, , , 0.95, 0, 1,1,,
    1592  1853.2  1873.2  1903.2  1983.2  2053.2  2143.2  2183.2  2353.2  2379.1
  2509.1  2629.1  2669.1  2719.1  2779.1  2789.1  2819.1  2883.3  2913.3  3013.3
  3113.3  3353.3  3413.3  3503.3  3523.3  3573.3  3643.3  3673.3  3713.3  3743.3
  3773.3  3793.3  3803.3  3956.5  4404.5  4474.5  4514.5  4554.5  4704.5  4764.6
  4779.8  4780.1  4780.9  4838.2  4840.9  4898.5  4900.8  4942.5  4947.4  4953.3
 5083.69  5083.8    5092  5181.5  5228.4  5454.7  5484.7  5534.7  5574.7    5681
   26.76   26.54   26.52    26.5   26.43   26.37   26.29   26.26   26.12    26.1
   25.99   25.88   25.82   25.74   25.64   25.63   25.58   25.48   25.43   25.28
   25.12   24.74   25.14   24.51   24.48   24.46   24.43   24.42   24.41    24.4
   24.39   24.38   24.38   24.44   24.19   24.17   24.15   24.14   24.09   24.07
   24.07   24.07   24.07   23.97   23.96   24.05   24.06   24.24   24.26   24.29
   24.62   24.62   24.63   24.83   24.86   25.36   25.53   26.16   26.03   26.02
   26.76   25.62   23.73   22.73   23.95   23.41   25.86   24.62   23.95   24.81
   23.61   24.47   23.57   24.95   24.77    23.5   24.45   23.87   24.75   23.65
   24.59   22.94   25.13   22.56   23.52   22.62   23.81      23   23.55   21.48
   21.25   22.32   23.81   24.43   22.94   21.88   23.11   20.82   19.71   20.99
   23.47   21.06   20.64   18.57   20.99    22.3    15.3   23.01   20.43   20.29
   20.62   19.74   21.47   23.13   22.74   25.24   24.72   26.15   25.36   26.02
    1592  1853.2  1873.2  1903.2  1983.2  2053.2  2143.2  2183.2  2353.2  2379.1
  2509.1  2629.1  2669.1  2719.1  2779.1  2789.1  2819.1  2883.3  2913.3  3013.3
  3113.3  3353.3  3413.3  3503.3  3523.3  3573.3  3643.3  3673.3  3713.3  3743.3
  3773.3  3793.3  3803.3  3956.5  4404.5  4474.5  4514.5  4554.5  4704.5  4764.6
  4779.8  4780.1  4780.9  4838.2  4840.9  4898.5  4900.8  4942.5  4947.4  4953.3
 5083.69  5083.8    5092  5181.5  5228.4  5454.7  5484.7  5534.7  5574.7    5681
   26.92   26.54   26.52    26.5   26.43   26.37   26.29   26.26   26.12    26.1
   25.99   25.88   25.82   25.74   25.64   25.63   25.58   25.48   25.43   25.28
   25.12   24.74   25.29   24.51   24.48   24.46   24.43   24.42   24.41    24.4
   24.39   24.38   24.38   24.59   24.19   24.17   24.15   24.14   24.09   24.07
   24.07   24.07   24.07   23.97   23.96   24.05   24.06   24.24   24.26   24.29
   24.62   24.62   24.63   24.83   24.86    25.4   25.53   26.31   26.03   26.18
   26.92   25.78   23.89   22.89   24.11   23.57   26.02   24.78   24.11   24.97
   23.77   24.63   23.73   25.11   24.93   23.66   24.61   24.03   24.91   23.81
   24.75    23.1   25.29   22.72   23.68   22.78   23.97   23.16   23.71   21.64
   21.41   22.48   23.97   24.59    23.1   22.04   23.27   20.98   19.87   21.15
   23.63   21.22    20.8   18.73   21.15   22.46   15.46   23.17   20.59   20.45
   20.78    19.9   21.63   23.29    22.9    25.4   24.88   26.31   25.52   26.18
Pier Skew, UpSta & Num, DnSta & Num=  ,4972, 2 ,4972, 2 , 0 , 0 , 0 ,,
       2       2
    4.18   21.38
       2       2
    4.34   21.54
Pier Skew, UpSta & Num, DnSta & Num=  ,4999.9, 2 ,4999.9, 2 , 0 , 0 , 0 ,,
       2       2
   -1.11   21.44
       2       2
    -.95    21.6
Pier Skew, UpSta & Num, DnSta & Num=  ,5028.6, 2 ,5028.6, 2 , 0 , 0 , 0 ,,
       2       2
    2.54    21.5
       2       2
     2.7   21.66
Pier Skew, UpSta & Num, DnSta & Num=  ,5056.4, 2 ,5056.4, 2 , 0 , 0 , 0 ,,
       2       2
    9.23   21.56
       2       2
    9.39   21.72
BR Coef= 1 , 1 , 0 ,1.25, 0 ,,,0.8,0,2,0,
WSPro=,,,, 1 ,,,, 0 ,,,, 0 ,,,,-1 ,-1 ,-1 , 0 , 0 , 0 , 0 , 0
BR U #Sta/Elev= 143
    1592   26.76  1743.2   26.43  1853.2   25.62  1863.2   24.91  1873.2   23.73
  1893.2   23.36  1903.2   22.73  1973.2   23.36  1983.2   23.95  2023.2   23.91
  2053.2   23.41  2143.2   25.86  2163.2   25.72  2183.2   24.62  2243.2   24.44
  2263.2   24.85  2303.2   24.44  2333.2   24.66  2353.2   23.95  2359.1   24.28
  2379.1   24.81  2399.1   24.75  2409.1   24.13  2449.1   23.82  2459.1   24.09
  2509.1   23.61  2539.1   23.87    2622   24.42  2629.1   24.47  2669.1   23.57
  2699.1   24.17  2719.1   24.95  2779.1   24.77  2789.1    23.5  2799.1   23.58
  2819.1   24.45  2883.3   23.87  2913.3   24.75  2983.3   23.74  3003.3   24.05
  3013.3   23.65  3063.3   24.22  3083.3   23.96  3113.3   24.59  3133.3   24.01
  3233.3   23.65  3243.3   23.39  3263.3   24.14  3273.3   23.52  3353.3   22.94
  3383.3   24.42  3403.3   24.61  3413.3   25.13  3433.3   24.69  3443.3   24.15
  3503.3   22.56  3513.3   23.27  3523.3   23.52  3526.9   23.46  3573.3   22.62
  3643.3   23.81  3673.3      23  3713.3   23.55  3743.3   21.48  3773.3   21.25
  3783.3   21.53  3793.3   22.32  3803.3   23.81  3935.3   24.34  3956.5   24.43
  4092.1   24.02  4248.4   23.44  4404.5   22.94  4474.5   21.88  4494.5   22.27
  4514.5   23.11  4524.5   22.95  4526.3   22.82  4554.5   20.82  4584.5   20.95
  4594.5   20.61  4604.5   20.84  4644.5   20.32  4654.5   20.51  4674.5   19.82
  4684.5   20.43  4704.5   19.71  4724.5   20.61  4754.5   20.93  4764.6   20.99
  4779.8   23.47    4780   21.86  4780.1   21.06  4780.9   20.64  4838.2   18.57
  4840.9   20.99  4841.2      21  4898.5    22.3  4899.4   19.56  4900.8    15.3
 4936.41   21.88  4936.5    21.9  4936.6   21.92  4942.5   23.01  4947.4   20.43
  4953.3   13.69  4969.5    7.38    4972    5.84  4973.8    4.65  4976.6     2.8
  4999.8    -.15  4999.9    -.15  5016.4     .57  5028.6    3.81  5028.7    3.81
  5035.8    9.13    5049   14.12  5056.4    9.62  5065.2   15.81  5083.3   19.63
  5083.6    19.7 5083.69   19.71  5083.8   19.74    5092   21.47  5107.1   21.84
  5130.8   22.41  5131.1   22.42  5181.5   23.13  5182.2   23.12  5228.4   22.74
  5301.2   23.31  5316.4   23.79  5338.3   24.52    5380   24.72  5448.3   25.06
  5454.7   25.24  5484.7   24.72  5534.7   26.15  5574.7   25.36  5624.7   25.99
  5656.9   25.67  5664.7   25.59    5681   26.02
BR U #Mann= 7
    1592      .2  3935.3      .1  4526.3     .05  4942.5    .045    5092     .05
  5107.1      .1    5681      .2
BR U Banks=4942.5,5092
BR D #Sta/Elev= 143
    1592   26.92  1743.2   26.59  1853.2   25.78  1863.2   25.07  1873.2   23.89
  1893.2   23.52  1903.2   22.89  1973.2   23.52  1983.2   24.11  2023.2   24.07
  2053.2   23.57  2143.2   26.02  2163.2   25.88  2183.2   24.78  2243.2    24.6
  2263.2   25.01  2303.2    24.6  2333.2   24.82  2353.2   24.11  2359.1   24.44
  2379.1   24.97  2399.1   24.91  2409.1   24.29  2449.1   23.98  2459.1   24.25
  2509.1   23.77  2539.1   24.03    2622   24.58  2629.1   24.63  2669.1   23.73
  2699.1   24.33  2719.1   25.11  2779.1   24.93  2789.1   23.66  2799.1   23.74
  2819.1   24.61  2883.3   24.03  2913.3   24.91  2983.3    23.9  3003.3   24.21
  3013.3   23.81  3063.3   24.38  3083.3   24.12  3113.3   24.75  3133.3   24.17
  3233.3   23.81  3243.3   23.55  3263.3    24.3  3273.3   23.68  3353.3    23.1
  3383.3   24.58  3403.3   24.77  3413.3   25.29  3433.3   24.85  3443.3   24.31
  3503.3   22.72  3513.3   23.43  3523.3   23.68  3526.9   23.62  3573.3   22.78
  3643.3   23.97  3673.3   23.16  3713.3   23.71  3743.3   21.64  3773.3   21.41
  3783.3   21.69  3793.3   22.48  3803.3   23.97  3935.3    24.5  3956.5   24.59
  4092.1   24.18  4248.4    23.6  4404.5    23.1  4474.5   22.04  4494.5   22.43
  4514.5   23.27  4524.5   23.11  4526.3   22.98  4554.5   20.98  4584.5   21.11
  4594.5   20.77  4604.5      21  4644.5   20.48  4654.5   20.67  4674.5   19.98
  4684.5   20.59  4704.5   19.87  4724.5   20.77  4754.5   21.09  4764.6   21.15
  4779.8   23.63    4780   22.02  4780.1   21.22  4780.9    20.8  4838.2   18.73
  4840.9   21.15  4841.2   21.16  4898.5   22.46  4899.4   19.72  4900.8   15.46
 4936.41   22.04  4936.5   22.06  4936.6   22.08  4942.5   23.17  4947.4   20.59
  4953.3   13.85  4969.5    7.54    4972       6  4973.8    4.81  4976.6    2.96
  4999.8     .01  4999.9     .01  5016.4     .73  5028.6    3.97  5028.7    3.97
  5035.8    9.29    5049   14.28  5056.4    9.78  5065.2   15.97  5083.3   19.79
  5083.6   19.86 5083.69   19.87  5083.8    19.9    5092   21.63  5107.1      22
  5130.8   22.57  5131.1   22.58  5181.5   23.29  5182.2   23.28  5228.4    22.9
  5301.2   23.47  5316.4   23.95  5338.3   24.68    5380   24.88  5448.3   25.22
  5454.7    25.4  5484.7   24.88  5534.7   26.31  5574.7   25.52  5624.7   26.15
  5656.9   25.83  5664.7   25.75    5681   26.18
BR D #Mann= 7
    1592      .2  3935.3      .1  4526.3     .05  4942.5    .045    5092     .05
  5107.1      .1    5681      .2
BR D Banks=4942.5,5092
BC Design=,, 0 ,, 0 ,,,,,,
BC HTab HWMax=26.83
BC Use User HTab Curves=0
BC User HTab FreeFlow(D)= 0

Type RM Length L Ch R = 1 ,21805.4 ,299.5,299.5,299.5
BEGIN DESCRIPTION:
Downstream Section of Bridge/Culvert/Weir
END DESCRIPTION:
XS GIS Cut Line= 6
      3169623.39     13845633.98       3167260.3     13845489.14
      3167009.25     13845512.67      3166055.63     13845870.84
      3165830.86     13845936.02      3165614.72     13845940.94
#Sta/Elev= 30
    1592      27  1853.2   25.86  1903.2   22.97  2143.2    26.1  3353.3   23.18
  3413.3   25.37  3773.3   21.49  3803.3   24.05  3935.3   24.58  4526.3   23.06
  4704.5   19.95  4764.6   21.23  4779.8   23.71  4780.9   20.88  4838.2   18.81
  4840.9   21.23  4898.5   22.54  4900.8   15.54  4942.5   23.25  4953.3   13.93
  4976.6    3.04  4999.8     .09  5028.7    4.05  5035.8    9.37    5049   14.36
  5056.4    9.86  5065.2   16.05    5092   21.71  5107.1   22.08    5681   26.26
#Mann= 7 , 1 , 0
    1592      .2       0  3935.3      .1       0  4526.3     .05       0
  4942.5    .045       0    5092     .05       0  5107.1      .1       0
    5681      .2       0
#XS Ineff= 2 , 0
       0    4936    23.2    5100       0    23.6
Permanent Ineff=
       F       F
Bank Sta=4942.5,5092
XS Rating Curve= 0 ,0
Exp/Cntr=0.5,0.3

Type RM Length L Ch R = 1 ,21505.9 ,22,22,22
BEGIN DESCRIPTION:
Upstream Section of Bridge/Culvert/Weir
END DESCRIPTION:
XS GIS Cut Line= 6
      3167711.64     13844654.99      3166713.77     13845360.56
      3166370.01     13845504.94      3166216.72     13845508.17
      3166016.64     13845548.51      3165591.53     13845649.77
#Sta/Elev= 30
  3339.8   25.74  3519.8   25.48  3584.8   22.82  3634.8   25.73  3834.8   25.49
  3889.8   23.28  3939.8   25.09  4209.8   24.61  4259.8   26.04  4314.8   24.73
  4549.8   24.82  4616.9   26.52  4651.9   22.55  4891.9   23.49 4951.57   26.23
 4985.67    4.83 4986.67    2.99 5012.07    3.14 5014.37    4.36 5016.97    3.02
 5026.47    3.32 5038.97    9.33 5070.77   12.56  5108.1   18.71  5168.1   18.96
  5258.1   22.79  5450.3   23.66  5602.2   23.16  5662.2   25.39  5729.2   25.68
#Mann= 5 , 1 , 0
  3339.8     .99       0  3939.8      .1       0 4951.57    .045       0
 5038.97     .14       0  5450.3      .1       0
#XS Ineff= 2 , 0
       0    4976      11    5039       0     9.5
Permanent Ineff=
       F       F
Bank Sta=4951.57,5038.97
XS Rating Curve= 0 ,0
Exp/Cntr=0.5,0.3