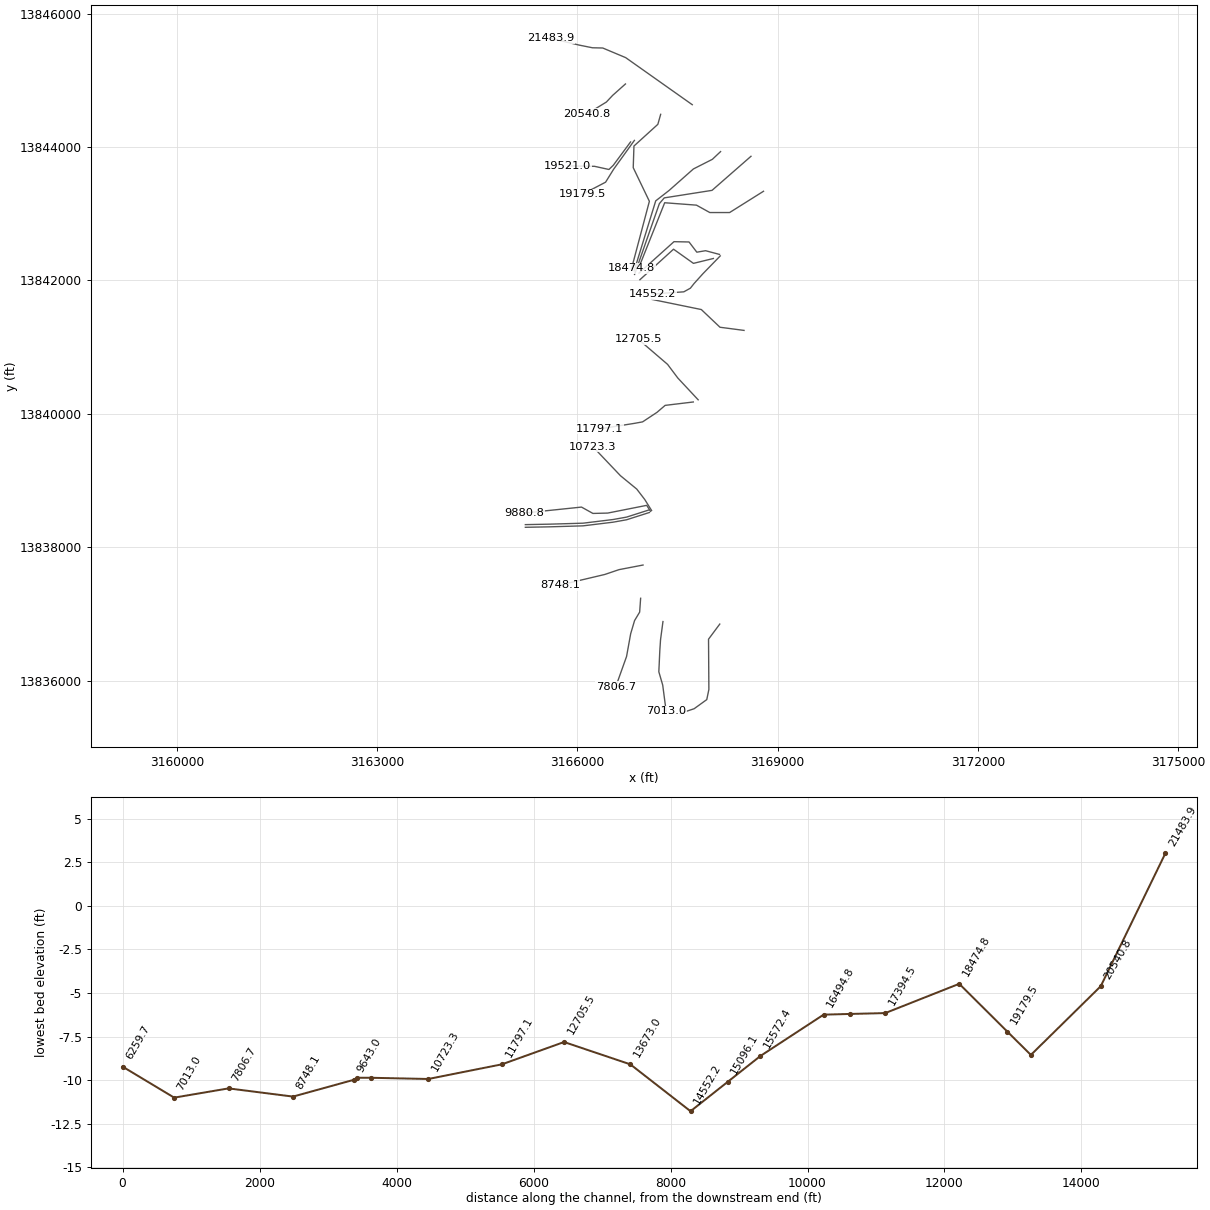
HEC-RAS study H100-00-00.prj: H100-00-00

--- H100-00-00.g01 (geometry) --- (continued)

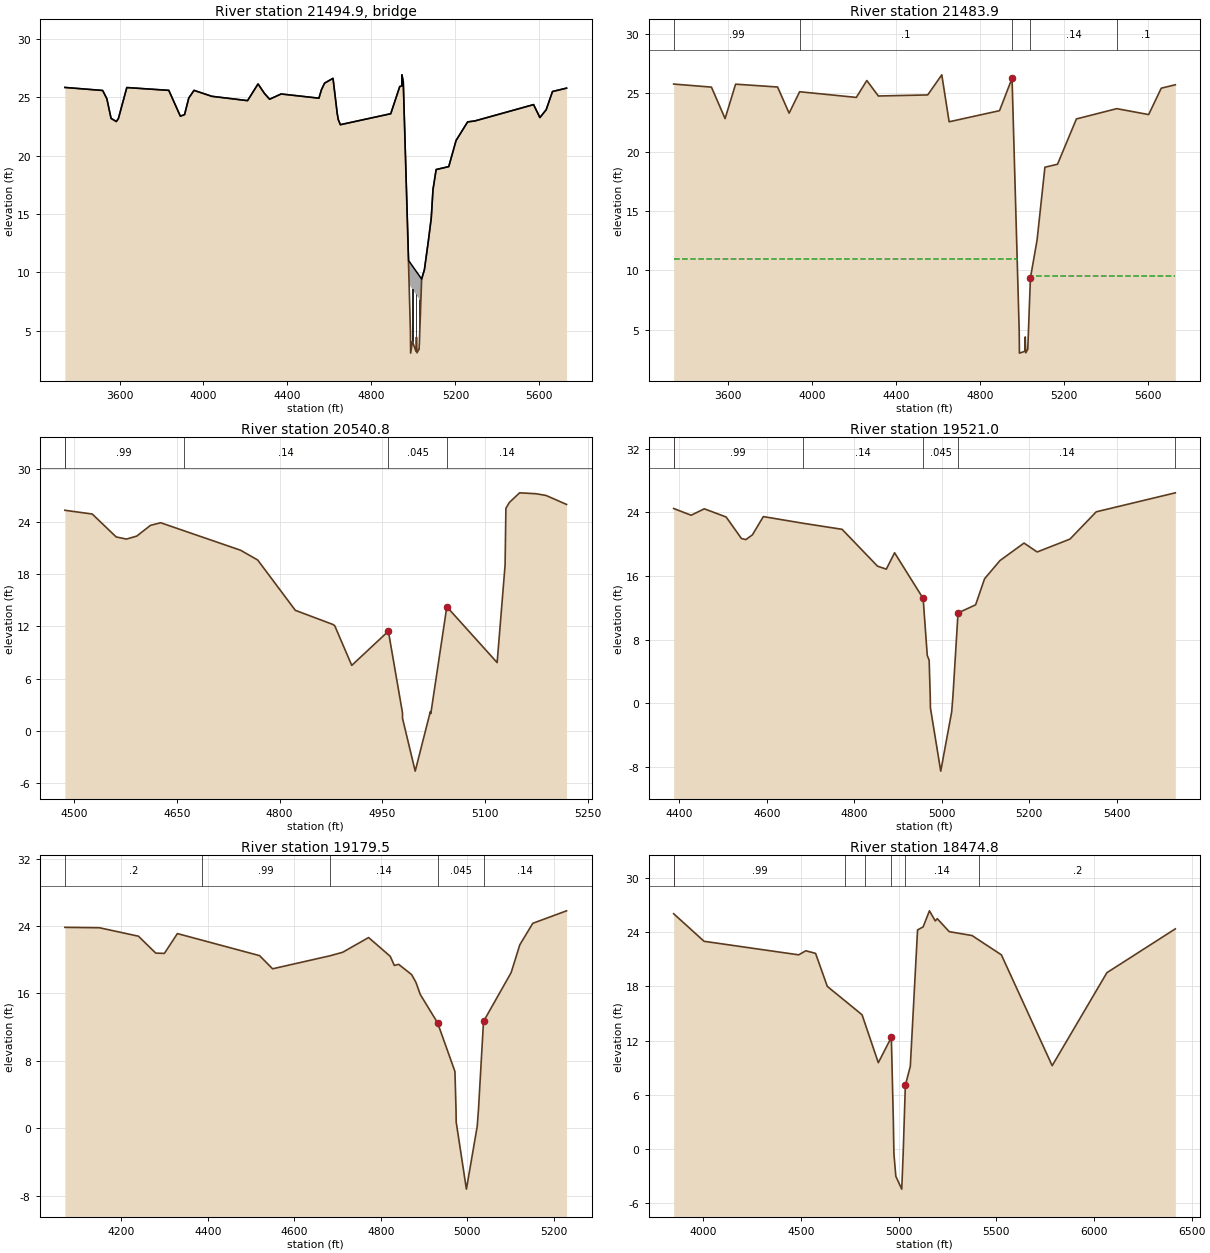
Type RM Length L Ch R = 3 ,21494.9 ,,,
BEGIN DESCRIPTION:
Pipeline
END DESCRIPTION:
Bridge Culvert--1,0,-1,-1, 0
Deck Dist Width WeirC Skew NumUp NumDn MinLoCord MaxHiCord MaxSubmerge Is_Ogee
10,2,2.6,0, 49, 49, , , 0.95, 0, 1,1,,
  3339.8  3519.8  3539.8  3559.8  3584.8  3594.8  3634.8  3834.8  3889.8  3909.8
  3929.8  3954.8  4039.8  4209.8  4259.8  4289.8  4314.8  4369.8  4549.8  4561.9
  4576.9  4616.9  4636.9  4641.9  4651.9  4891.9  4934.8  4944.8 4944.97 4951.57
 4976.97 4979.17 4986.67 5035.07 5038.97 5052.27 5070.77  5084.8  5093.1  5108.1
  5168.1  5203.1  5258.1  5292.2  5572.2  5602.2  5632.2  5662.2  5729.2
   25.84   25.58   24.87   23.19   22.92   23.18   25.83   25.59   23.38   23.51
   24.93   25.59   25.08   24.71   26.14   25.34   24.83   25.28   24.92   25.65
   26.21   26.62   23.62   23.09   22.65   23.59   25.92   25.97   26.92   26.33
   11.02   10.96   10.77    9.53    9.43   10.24   12.66   14.65    17.1   18.81
   19.06    21.3   22.89   22.97   24.37   23.26   23.93   25.49   25.78
   25.84   25.58   24.87   23.19   22.92   23.18   25.83   25.59   23.38   23.51
   24.93   25.59   25.08   24.71   26.14   25.34   24.83   25.28   24.92   25.65
   26.21   26.62   23.62   23.09   22.65   23.59   25.92   25.97   26.92   26.33
   10.47     9.1    8.77    7.53    9.43   10.24   12.66   14.65    17.1   18.81
   19.06    21.3   22.89   22.97   24.37   23.26   23.93   25.49   25.78
  3339.8  3519.8  3539.8  3559.8  3584.8  3594.8  3634.8  3834.8  3889.8  3909.8
  3929.8  3954.8  4039.8  4209.8  4259.8  4289.8  4314.8  4369.8  4549.8  4561.9
  4576.9  4616.9  4636.9  4641.9  4651.9  4891.9  4934.8  4944.8 4944.97 4951.57
 4976.97 4979.17 4986.67 5035.07 5038.97 5052.27 5070.77  5084.8  5093.1  5108.1
  5168.1  5203.1  5258.1  5292.2  5572.2  5602.2  5632.2  5662.2  5729.2
   25.84   25.58   24.87   23.19   22.92   23.18   25.83   25.59   23.38   23.51
   24.93   25.59   25.08   24.71   26.14   25.34   24.83   25.28   24.92   25.65
   26.21   26.62   23.62   23.09   22.65   23.59   25.92   25.97   26.92   26.33
   11.02   10.96   10.77    9.53    9.43   10.24   12.66   14.65    17.1   18.81
   19.06    21.3   22.89   22.97   24.37   23.26   23.93   25.49   25.78
   25.84   25.58   24.87   23.19   22.92   23.18   25.83   25.59   23.38   23.51
   24.93   25.59   25.08   24.71   26.14   25.34   24.83   25.28   24.92   25.65
   26.21   26.62   23.62   23.09   22.65   23.59   25.92   25.97   26.92   26.33
   10.47     9.1    8.77    7.53    9.43   10.24   12.66   14.65    17.1   18.81
   19.06    21.3   22.89   22.97   24.37   23.26   23.93   25.49   25.78
Pier Skew, UpSta & Num, DnSta & Num=  ,4995.1, 2 ,4995.1, 2 , 0 , 0 , 0 ,,
     1.4     1.4
    2.99    9.57
     1.4     1.4
    2.99    9.57
Pier Skew, UpSta & Num, DnSta & Num=  ,5012.1, 2 ,5012.1, 2 , 0 , 0 , 0 ,,
     1.4     1.4
    2.28    9.14
     1.4     1.4
    2.28    9.14
Pier Skew, UpSta & Num, DnSta & Num=  ,5026.5, 2 ,5026.5, 2 , 0 , 0 , 0 ,,
     1.4     1.4
     2.4    8.77
     1.4     1.4
     2.4    8.77
BR Coef= 1 , 1 , 0 ,1.25, 0 ,,,0.8,-1,2,0,
WSPro=,,,, 1 ,,,, 0 ,,,, 0 ,,,,-1 ,-1 ,-1 , 0 , 0 , 0 , 0 , 0
BR U #Sta/Elev= 65
  3339.8   25.84  3519.8   25.58  3539.8   24.87  3559.8   23.19  3584.8   22.92
  3594.8   23.18  3634.8   25.83  3834.8   25.59  3889.8   23.38  3909.8   23.51
  3929.8   24.93  3939.8   25.19  3954.8   25.59  4039.8   25.08  4209.8   24.71
  4259.8   26.14  4289.8   25.34  4314.8   24.83  4369.8   25.28  4549.8   24.92
  4561.9   25.65  4576.9   26.21  4616.9   26.62  4636.9   23.62  4641.9   23.09
  4651.9   22.65  4891.9   23.59  4934.8   25.92  4944.8   25.97 4944.97   26.92
 4951.57   26.33 4976.97   10.47 4977.08    10.4 4977.17   10.35 4979.17     9.1
 4985.67    4.93 4986.67    3.09 4994.37    3.99 4995.07     4.1 5012.07    3.24
 5014.37    4.46 5016.97    3.12 5026.47    3.42 5028.07    3.88 5035.07     7.4
 5038.86    9.37 5038.97    9.43 5039.07    9.44 5039.17    9.44 5052.27   10.24
 5070.77   12.66  5084.8   14.65  5088.1   15.61  5093.1    17.1  5108.1   18.81
  5168.1   19.06  5203.1    21.3  5258.1   22.89  5292.2   22.97  5450.3   23.76
  5572.2   24.37  5602.2   23.26  5632.2   23.93  5662.2   25.49  5729.2   25.78
BR U #Mann= 5
  3339.8     .99  3939.8      .1 4951.57    .045 5038.97     .14  5450.3      .1
BR U Banks=4951.57,5038.97
BR D #Sta/Elev= 65
  3339.8   25.84  3519.8   25.58  3539.8   24.87  3559.8   23.19  3584.8   22.92
  3594.8   23.18  3634.8   25.83  3834.8   25.59  3889.8   23.38  3909.8   23.51
  3929.8   24.93  3939.8   25.19  3954.8   25.59  4039.8   25.08  4209.8   24.71
  4259.8   26.14  4289.8   25.34  4314.8   24.83  4369.8   25.28  4549.8   24.92
  4561.9   25.65  4576.9   26.21  4616.9   26.62  4636.9   23.62  4641.9   23.09
  4651.9   22.65  4891.9   23.59  4934.8   25.92  4944.8   25.97 4944.97   26.92
 4951.57   26.33 4976.97   10.47 4977.08    10.4 4977.17   10.35 4979.17     9.1
 4985.67    4.93 4986.67    3.09 4994.37    3.99 4995.07     4.1 5012.07    3.24
 5014.37    4.46 5016.97    3.12 5026.47    3.42 5028.07    3.88 5035.07     7.4
 5038.86    9.37 5038.97    9.43 5039.07    9.44 5039.17    9.44 5052.27   10.24
 5070.77   12.66  5084.8   14.65  5088.1   15.61  5093.1    17.1  5108.1   18.81
  5168.1   19.06  5203.1    21.3  5258.1   22.89  5292.2   22.97  5450.3   23.76
  5572.2   24.37  5602.2   23.26  5632.2   23.93  5662.2   25.49  5729.2   25.78
BR D #Mann= 5
  3339.8     .99  3939.8      .1 4951.57    .045 5038.97     .14  5450.3      .1
BR D Banks=4951.57,5038.97
BC Design=,, 0 ,, 0 ,,,,,,
BC HTab HWMax=26.82
BC Use User HTab Curves=0
BC User HTab FreeFlow(D)= 0

Type RM Length L Ch R = 1 ,21483.9 ,841.4,943.1,996.3
BEGIN DESCRIPTION:
Downstream Section of Bridge/Culvert/Weir
END DESCRIPTION:
XS GIS Cut Line= 6
       3167719.8     13844634.57      3166721.93     13845340.14
      3166378.17     13845484.52      3166224.88     13845487.75
       3166024.8     13845528.09      3165599.69     13845629.35
#Sta/Elev= 30
  3339.8   25.76  3519.8    25.5  3584.8   22.84  3634.8   25.75  3834.8   25.51
  3889.8    23.3  3939.8   25.11  4209.8   24.63  4259.8   26.06  4314.8   24.75
  4549.8   24.84  4616.9   26.54  4651.9   22.57  4891.9   23.51 4951.57   26.25
 4985.67    4.85 4986.67    3.01 5012.07    3.16 5014.37    4.38 5016.97    3.04
 5026.47    3.34 5038.97    9.35 5070.77   12.58  5108.1   18.73  5168.1   18.98
  5258.1   22.81  5450.3   23.68  5602.2   23.18  5662.2   25.41  5729.2    25.7
#Mann= 5 , 1 , 0
  3339.8     .99       0  3939.8      .1       0 4951.57    .045       0
 5038.97     .14       0  5450.3      .1       0
#XS Ineff= 2 , 0
       0    4976      11    5039       0     9.5
Permanent Ineff=
       F       F
Bank Sta=4951.57,5038.97
XS Rating Curve= 0 ,0
Exp/Cntr=0.5,0.3

Type RM Length L Ch R = 1 ,20540.8 ,1042.5,1019.8,868.5
BEGIN DESCRIPTION:
Cross Section 20540.8
END DESCRIPTION:
XS GIS Cut Line= 5
      3166718.36     13844945.39      3166526.83     13844774.49
      3166432.54      13844674.3      3166182.08     13844521.08
      3166141.81     13844500.95
#Sta/Elev= 29
  4486.4   25.29  4526.4   24.86  4561.4   22.23  4576.4   21.99  4591.4   22.33
  4611.4   23.56  4626.4   23.86  4659.7   22.96  4743.1   20.71  4768.1   19.59
  4823.1   13.82  4878.1    12.2  4880.7   12.05  4905.5    7.51    4959   11.43
  4979.6    2.08  4979.7    1.43  4998.2   -4.61  5020.3    2.21    5021    1.99
  5044.4   14.23  5117.9    7.83  5129.5      19  5130.7   25.51  5135.7   26.18
  5150.7   27.29  5174.3   27.19  5189.3   26.99  5219.3   25.96
#Mann= 5 , 1 , 0
  4486.4      .2       0  4486.4     .99       0  4659.7     .14       0
    4959    .045       0  5044.4     .14       0
Bank Sta=4959,5044.4
XS Rating Curve= 0 ,0
Exp/Cntr=0.3,0.1

Type RM Length L Ch R = 1 ,19521.0 ,255.3,341.5,398.3
BEGIN DESCRIPTION:
Cross Section 19521.0
END DESCRIPTION:
XS GIS Cut Line= 6
      3166794.97     13844076.15      3166535.67     13843725.51
      3166470.85     13843663.63      3166255.75     13843710.77
      3165905.11     13843716.67      3165855.01     13843716.67
#Sta/Elev= 30
  4387.3   24.49  4427.3   23.64  4457.3   24.45  4507.3   23.42  4542.3   20.71
  4552.3   20.58  4567.3   21.17  4592.3   23.47  4682.2   22.64  4772.3   21.87
  4853.4   17.23  4873.4   16.86  4892.3   18.92  4957.6   13.17    4967       6
  4971.3    5.41  4973.8     .89  4974.2    -.59  4997.8   -8.55  5022.8   -1.09
  5025.7     .91  5037.3   11.35  5077.5   12.37    5098   15.65  5133.2   17.94
  5188.2   20.14  5218.2   19.02  5293.2   20.64  5353.2   24.07    5534   26.46
#Mann= 6 , 1 , 0
  4387.3      .2       0  4387.3     .99       0  4682.2     .14       0
  4957.6    .045       0  5037.3     .14       0    5534      .2       0
Bank Sta=4957.6,5037.3
XS Rating Curve= 0 ,0
Exp/Cntr=0.3,0.1

Type RM Length L Ch R = 1 ,19179.5 ,476,704.7,916.5
BEGIN DESCRIPTION:
Cross Section 19179.5
END DESCRIPTION:
XS GIS Cut Line= 4
      3166852.47     13844099.57      3166541.82     13843667.83
      3166420.73     13843473.02      3166067.96     13843288.74
#Sta/Elev= 30
  4069.9   23.85  4149.9    23.8  4239.9    22.8  4279.9   20.79  4299.9   20.76
  4329.9   23.11  4387.3   22.32  4519.9   20.49  4549.9   18.93  4682.2   20.47
  4711.8   20.89  4771.8   22.64  4821.8   20.41  4831.2   19.33  4841.2   19.46
  4871.2   18.24  4881.2   17.32  4891.2   15.88  4931.2   12.52  4971.3    6.74
  4973.8    2.22  4974.2     .74  4997.8   -7.22  5022.8     .24  5025.7    2.24
  5037.3   12.68  5101.2   18.48  5121.2   21.78  5151.2   24.33  5229.2   25.81
#Mann= 5 , 1 , 0
  4069.9      .2       0  4387.3     .99       0  4682.2     .14       0
  4931.2    .045       0  5037.3     .14       0
Bank Sta=4931.2,5037.3
XS Rating Curve= 0 ,0
Exp/Cntr=0.3,0.1

Type RM Length L Ch R = 1 ,18474.8 ,1131.7,1080.3,322.5
BEGIN DESCRIPTION:
Cross Section 18474.8
END DESCRIPTION:
XS GIS Cut Line= 6
      3167246.37      13844490.4      3167204.12     13844340.41
        3166846.     13844015.05       3166835.1     13843690.63
      3167077.11     13843186.53      3166810.52     13842181.07
#Sta/Elev= 30
  3849.1   26.07  4004.9   23.01  4488.8   21.51  4525.5   21.96  4575.5   21.67
  4635.5   18.01  4726.1   16.41  4813.4   14.86  4825.9   14.06  4896.5    9.55
  4963.2   12.36  4973.5       3  4976.3    -.54  4986.2   -3.05  5016.4   -4.47
  5023.8    -.47  5034.8    7.04  5060.2    9.14  5097.3   24.27  5125.9   24.61
  5158.1   26.39  5188.1   25.27  5198.1   25.52  5259.4   24.08  5376.3   23.65
  5413.2   23.12  5526.3   21.51  5786.3    9.22  6066.3   19.53  6416.5   24.39
#Mann= 7 , 1 , 0
  3849.1      .2       0  3849.1     .99       0  4726.1     .06       0
  4825.9     .14       0  4963.2    .045       0  5034.8     .14       0
  5413.2      .2       0
Bank Sta=4963.2,5034.8
XS Rating Curve= 0 ,0
Exp/Cntr=0.3,0.1

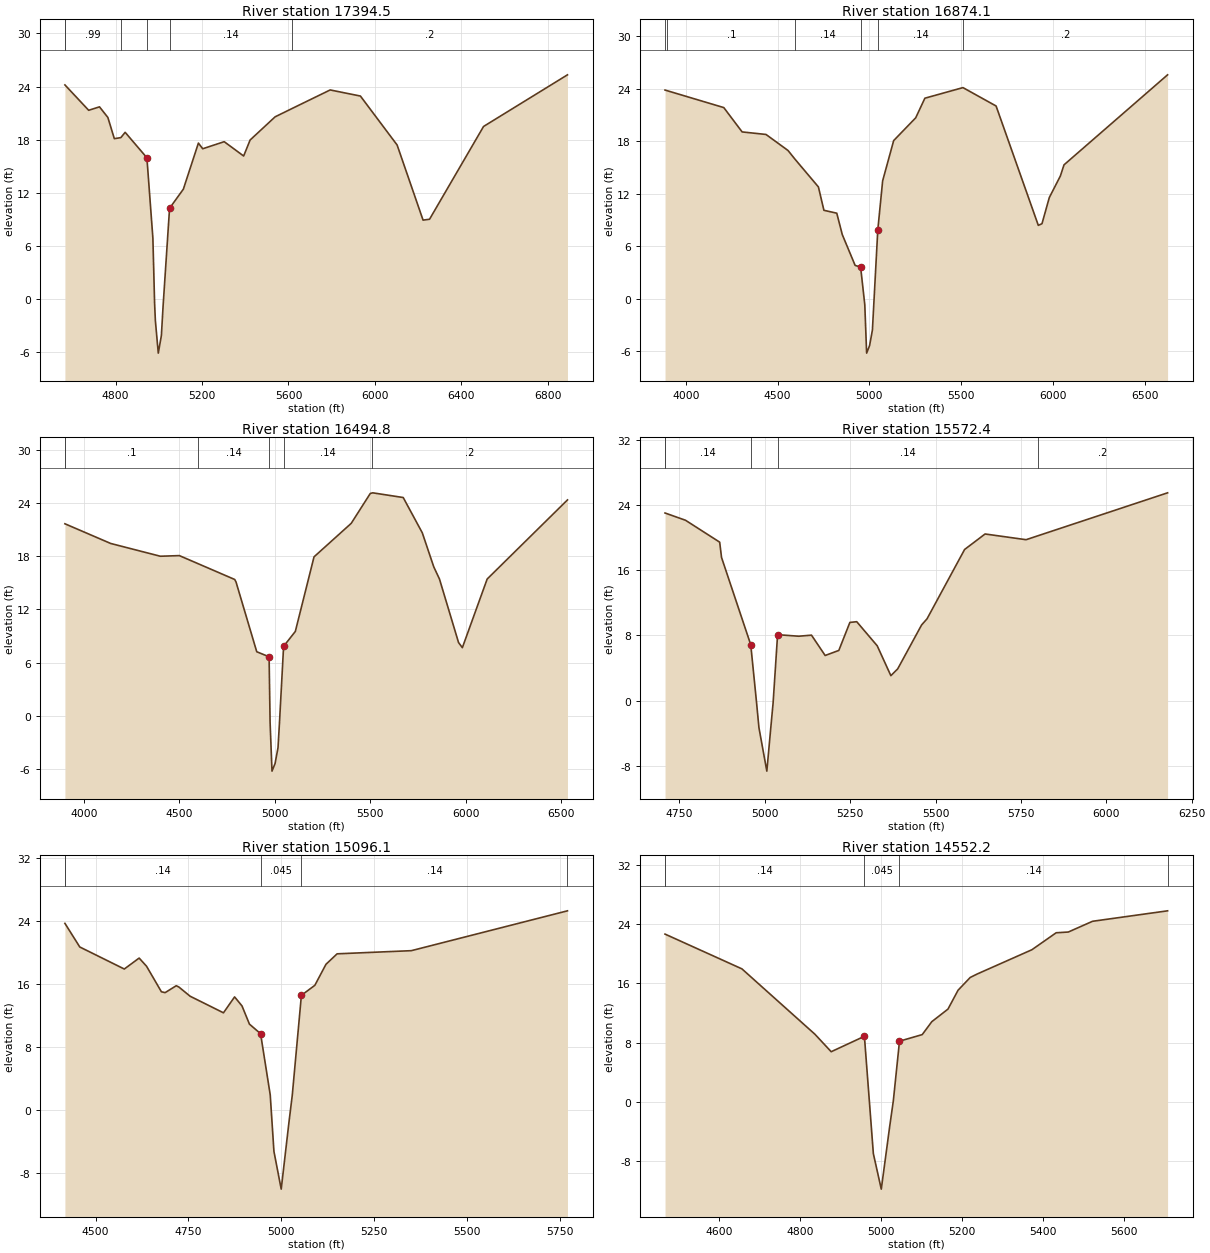
Type RM Length L Ch R = 1 ,17394.5 ,406.9,520.4,76.6
BEGIN DESCRIPTION:
Cross Section 17394.5
END DESCRIPTION:
XS GIS Cut Line= 6
        3168144.     13843931.68      3168021.06     13843815.97
      3167736.62     13843671.35      3167373.37     13843349.91
       3167172.3     13843193.37      3166848.83     13842143.66
#Sta/Elev= 30
  4565.2   24.18  4675.2   21.31  4725.2    21.7    4764    20.5    4794    18.1
  4824.2   18.22    4844   18.82  4944.7   15.94  4972.4    6.85  4980.4    -.58
  4983.9   -2.48  4997.4   -6.15  5011.7   -4.16  5019.7     -.8  5049.6   10.23
  5113.4   12.39  5183.1    17.6  5203.1   16.96  5302.5   17.76  5392.5   16.14
  5422.5   17.95  5538.2   20.57  5616.6   21.51    5793   23.61    5933   22.92
    6103   17.38    6223    8.89    6253    8.99    6503   19.48  6891.4   25.32
#Mann= 6 , 1 , 0
  4565.2      .2       0  4565.2     .99       0  4824.2     .14       0
  4944.7    .045       0  5049.6     .14       0  5616.6      .2       0
Bank Sta=4944.7,5049.6
XS Rating Curve= 0 ,0
Exp/Cntr=0.3,0.1

Type RM Length L Ch R = 1 ,16874.1 ,307.5,379.3,136.2
BEGIN DESCRIPTION:
Cross Section 16874.1
END DESCRIPTION:
XS GIS Cut Line= 5
      3168599.59     13843861.27        3168016.     13843350.63
      3167299.78     13843237.89      3167226.83     13843151.68
      3166855.46     13842090.61
#Sta/Elev= 30
  3887.1   23.84  3899.9   23.76  4207.1   21.84  4307.1   19.06  4437.1   18.77
  4557.1   16.94  4596.9    15.9  4722.6   12.78  4752.6   10.11  4822.6    9.78
  4852.6    7.34  4922.6    3.82  4952.6    3.62  4975.3    -.68  4985.3    -6.2
  5001.4   -5.34  5016.8   -3.56  5046.1    7.87  5072.6   13.48  5132.6   18.07
  5252.6   20.67  5302.6   22.91    5510   24.12  5690.5   22.02  5920.5    8.39
  5940.5    8.58  5980.5   11.57  6040.5   14.02  6060.5    15.3  6624.7   25.58
#Mann= 6 , 1 , 0
  3887.1      .2       0  3899.9      .1       0  4596.9     .14       0
  4952.6    .045       0  5046.1     .14       0    5510      .2       0
Bank Sta=4952.6,5046.1
XS Rating Curve= 0 ,0
Exp/Cntr=0.3,0.1

Type RM Length L Ch R = 1 ,16494.8 ,604.5,922.4,227.3
BEGIN DESCRIPTION:
Cross Section 16494.8
END DESCRIPTION:
XS GIS Cut Line= 6
      3168787.39     13843337.25      3168279.42      13843018.1
      3167982.49      13843018.1      3167782.42     13843128.98
      3167306.41     13843164.94      3166928.41     13842216.61
#Sta/Elev= 29
  3899.9   21.65  4139.9   19.43  4399.9   17.99  4499.8   18.06  4596.9   17.16
  4789.8   15.37  4796.7   15.09  4905.4    7.22  4970.1    6.65  4975.3    -.72
  4985.3   -6.24  5001.4   -5.38  5016.8    -3.6  5024.8    -.67  5046.1    7.83
  5107.6    9.51  5205.6   17.92  5400.6    21.7  5500.6   25.07    5510   25.12
  5513.1   25.14  5673.1   24.61  5773.1   20.63  5833.1    16.8  5863.1   15.42
  5963.1    8.26  5983.1    7.68  6113.1   15.42    6534   24.34
#Mann= 6 , 1 , 0
  3899.9      .2       0  3899.9      .1       0  4596.9     .14       0
  4970.1    .045       0  5046.1     .14       0    5510      .2       0
Bank Sta=4970.1,5046.1
XS Rating Curve= 0 ,0
Exp/Cntr=0.3,0.1

Type RM Length L Ch R = 1 ,15572.4 ,180.3,476.3,112.7
BEGIN DESCRIPTION:
Cross Section 15572.4
END DESCRIPTION:
XS GIS Cut Line= 6
      3168127.41     13842390.56      3167918.84      13842446.1
      3167788.01     13842423.88      3167671.54     13842576.98
      3167445.68     13842581.35      3166921.78      13842110.5
#Sta/Elev= 27
  4707.7      23  4767.7   22.11  4867.7   19.43  4873.2   17.55  4958.7    6.87
  4975.8    -.26  4982.7   -3.29  5005.8   -8.61  5017.1   -3.43  5024.2    -.24
  5037.3     8.1  5098.9    7.91  5136.6    8.04  5176.6    5.55  5216.6    6.17
    5249     9.6    5269    9.69    5329    6.74    5369    3.08    5389    3.91
    5459    9.29  5474.9   10.04  5584.9   18.53  5644.9   20.43  5764.9   19.73
  5799.6   20.21  6179.3   25.47
#Mann= 5 , 1 , 0
  4707.7      .2       0  4707.7     .14       0  4958.7    .045       0
  5037.3     .14       0  5799.6      .2       0
Bank Sta=4958.7,5037.3
XS Rating Curve= 0 ,0
Exp/Cntr=0.3,0.1

Type RM Length L Ch R = 1 ,15096.1 ,210.5,543.9,678.7
BEGIN DESCRIPTION:
Cross Section 15096.1
END DESCRIPTION:
XS GIS Cut Line= 4
       3168035.9     13842329.35      3167737.47      13842256.4
      3167439.05     13842468.61      3166935.04     13842011.03
#Sta/Elev= 26
  4417.1   23.66  4457.1   20.66  4577.1   17.86  4617.1   19.25  4637.1   18.21
  4677.1   14.97  4687.1   14.86  4717.1   15.74  4724.3   15.57  4754.3   14.41
  4844.3    12.3  4874.3   14.32  4894.3   13.17  4914.3   10.86  4944.3    9.65
  4970.3    1.88  4980.3    -5.3  4999.9  -10.09  5020.8   -1.59  5029.7    1.84
  5054.3   14.52  5090.5   15.79  5120.5   18.46  5150.5   19.79  5350.5   20.19
  5771.2   25.25
#Mann= 5 , 1 , 0
  4417.1      .2       0  4417.1     .14       0  4944.3    .045       0
  5054.3     .14       0  5771.2      .2       0
Bank Sta=4944.3,5054.3
XS Rating Curve= 0 ,0
Exp/Cntr=0.3,0.1

Type RM Length L Ch R = 1 ,14552.2 ,934.1,879.2,440.8
BEGIN DESCRIPTION:
Cross Section 14552.2
END DESCRIPTION:
XS GIS Cut Line= 6
      3168138.97     13842367.98      3167880.75     13842102.49
      3167746.18     13841953.37      3167691.63     13841884.27
      3167593.43     13841829.72      3167124.28     13841796.99
#Sta/Elev= 22
  4465.5   22.63  4655.5   17.94  4835.9    9.12  4876.1    6.76  4958.2    8.84
  4970.3     .19  4980.3   -6.99  4999.9  -11.78  5020.8   -3.28  5029.7     .15
  5044.9    8.18  5101.1    9.07  5124.7   10.81  5164.7   12.51  5189.7   15.06
  5219.7   16.78  5237.1   17.25  5372.1   20.52  5432.1   22.81  5462.1   22.91
  5522.1   24.36  5707.4   25.77
#Mann= 5 , 1 , 0
  4465.5      .2       0  4465.5     .14       0  4958.2    .045       0
  5044.9     .14       0  5707.4      .2       0
Bank Sta=4958.2,5044.9
XS Rating Curve= 0 ,0
Exp/Cntr=0.3,0.1

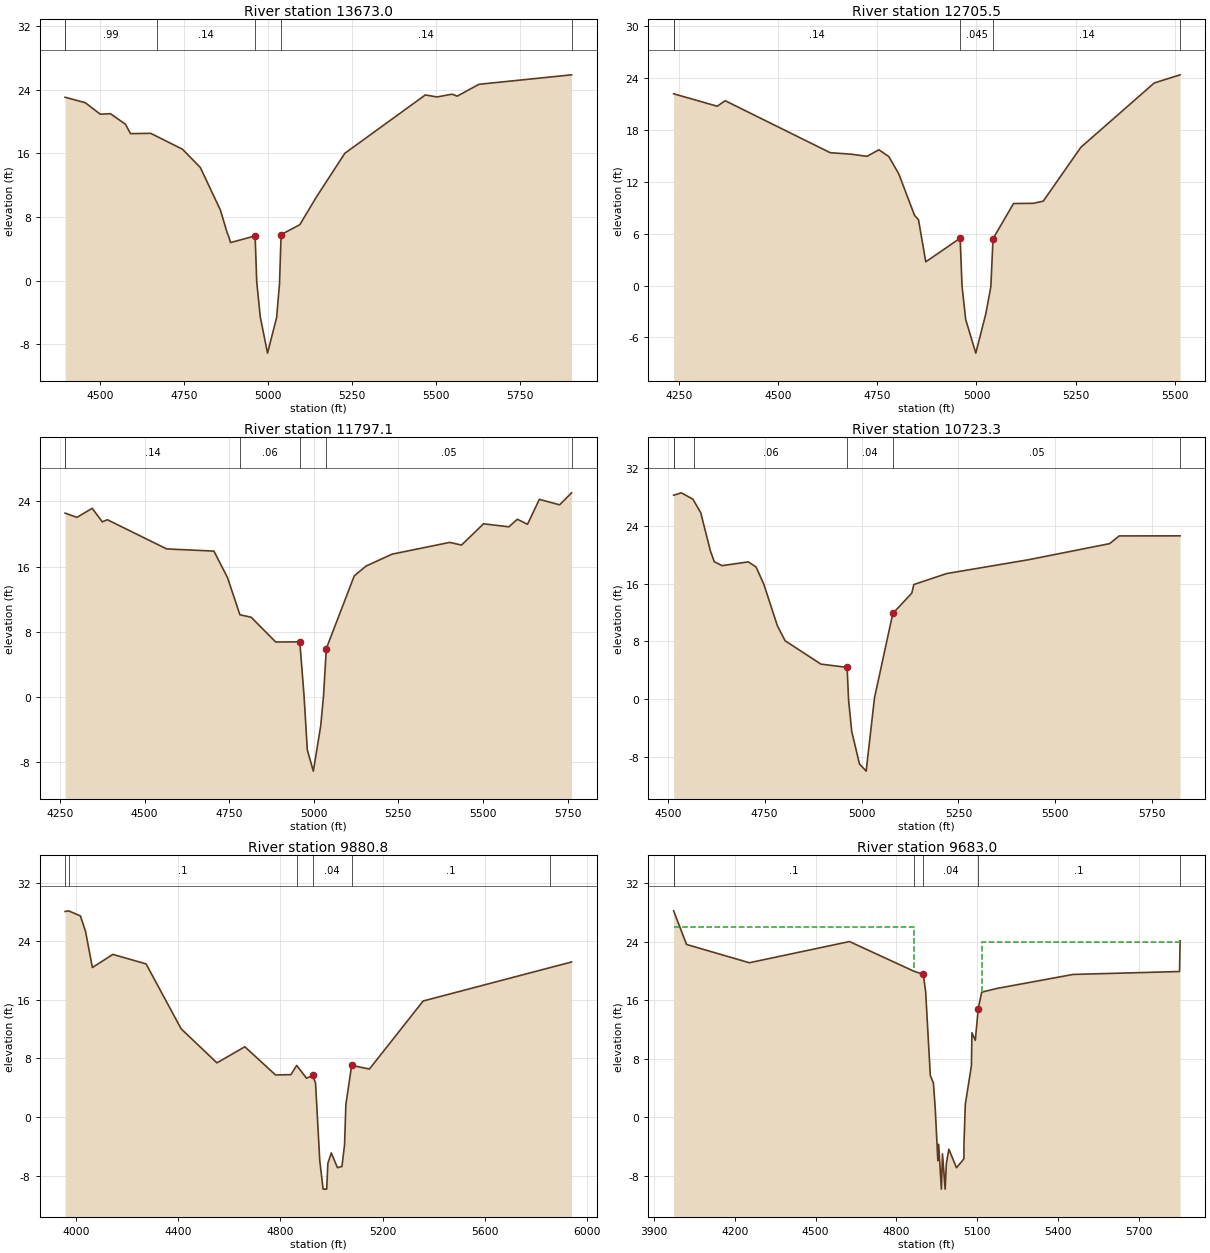
Type RM Length L Ch R = 1 ,13673.0 ,967.1,967.5,991
BEGIN DESCRIPTION:
Cross Section 13673.0
END DESCRIPTION:
XS GIS Cut Line= 4
      3168495.38     13841251.46      3168135.33     13841298.74
      3167855.29     13841564.23      3167109.73     13841716.98
#Sta/Elev= 30
  4394.6   23.06  4454.6   22.38  4499.6   20.93  4529.6      21  4574.6   19.67
  4589.6   18.49  4649.6   18.53  4669.2   18.12  4744.6   16.53  4797.7   14.24
  4857.7    8.88  4877.7    6.05  4882.7    5.53  4887.8     4.8  4961.1    5.64
    4966    -.14  4976.5   -4.54  4998.2   -9.09  5025.2   -4.62  5033.9    -.36
  5038.6     5.8  5094.4    7.05  5143.6   10.51  5228.6   16.02  5468.6   23.35
  5503.6    23.1  5548.6   23.45  5563.6    23.2  5628.6   24.69  5904.7   25.88
#Mann= 6 , 1 , 0
  4394.6      .2       0  4394.6     .99       0  4669.2     .14       0
  4961.1    .045       0  5038.6     .14       0  5904.7      .2       0
Bank Sta=4961.1,5038.6
XS Rating Curve= 0 ,0
Exp/Cntr=0.3,0.1

Type RM Length L Ch R = 1 ,12705.5 ,725.2,908.4,1076.9
BEGIN DESCRIPTION:
Cross Section 12705.5
END DESCRIPTION:
XS GIS Cut Line= 4
      3167808.01     13840211.31      3167502.51     13840538.63
      3167349.76      13840742.3      3166913.34     13841116.89
#Sta/Elev= 25
  4236.2   22.16  4346.2   20.72  4366.2   21.36  4631.2   15.35  4683.9   15.18
  4723.9   14.93  4753.9   15.69  4778.9   14.91  4803.9   12.93  4843.9    8.11
  4853.9     7.6  4872.2    2.74  4958.9    5.47  4963.7    -.07  4972.9   -3.92
  4998.4   -7.81  5023.6   -3.27  5036.4    -.12  5041.8    5.41  5093.6    9.48
  5143.5     9.5  5168.5    9.75  5263.5   15.98  5448.5   23.41  5513.7   24.35
#Mann= 5 , 1 , 0
  4236.2      .2       0  4236.2     .14       0  4958.9    .045       0
  5041.8     .14       0  5513.7      .2       0
Bank Sta=4958.9,5041.8
XS Rating Curve= 0 ,0
Exp/Cntr=0.3,0.1

Type RM Length L Ch R = 1 ,11797.1 ,1353.9,1073.8,954.4
BEGIN DESCRIPTION:
Cross Section 11797.1
END DESCRIPTION:
XS GIS Cut Line= 6
      3167735.27     13840178.58       3167313.4     13840127.66
      3167189.74     13840022.19      3166975.17     13839880.36
      3166855.15     13839858.53      3166331.44     13839774.89
#Sta/Elev= 30
    4265   22.56    4300   22.04    4345   23.15    4375   21.49    4390   21.75
    4565   18.17  4704.9    17.9  4744.9   14.66  4781.7   10.09  4814.9    9.79
  4887.5    6.75  4958.7    6.77  4971.2     .17  4980.9   -6.49  4998.7   -9.09
  5020.6    -3.5  5028.8     .13  5037.1    5.95  5119.7   14.87  5154.7   16.07
  5231.7   17.53  5401.7   18.97  5436.7   18.64  5501.7   21.25  5576.7   20.88
  5601.7   21.81  5631.7   21.19  5666.7   24.25  5726.7   23.58    5762   25.05
#Mann= 6 , 1 , 0
    4265      .2       0    4265     .14       0  4781.7     .06       0
  4958.7     .04       0  5037.1     .05       0    5762      .2       0
Bank Sta=4958.7,5037.1
XS Rating Curve= 0 ,0
Exp/Cntr=0.3,0.1

Type RM Length L Ch R = 1 ,10723.3 ,672.1,842.5,925.7
BEGIN DESCRIPTION:
Cross Section 10723.3
END DESCRIPTION:
XS GIS Cut Line= 5
      3167109.73      13838552.9       3167007.9     13838716.56
      3166887.88     13838872.94      3166644.21     13839072.97
      3166229.61     13839509.39
#Sta/Elev= 28
  4515.1   28.23  4535.1   28.56  4565.1   27.67  4567.3   27.46  4585.1    25.8
  4610.1   20.51  4620.1   19.03  4640.1   18.49  4707.9   19.01  4727.9    18.3
  4747.9   15.92  4782.9   10.17  4802.9     8.1  4895.2    4.87  4962.8    4.42
  4966.6    -.05  4974.7   -4.42  4994.7   -8.93    5012   -9.93  5033.5      .2
  5080.8   11.88  5129.8   14.69    5135   15.88  5220.2    17.4  5430.2    19.3
  5640.2   21.53  5665.2    22.6  5822.2   22.61
#Mann= 6 , 1 , 0
  4515.1      .2       0  4515.1      .1       0  4567.3     .06       0
  4962.8     .04       0  5080.8     .05       0  5822.2      .2       0
Bank Sta=4962.8,5080.8
XS Rating Curve= 0 ,0
Exp/Cntr=0.3,0.1

Type RM Length L Ch R = 1 ,9880.8  ,169.8,197.8,217.1
BEGIN DESCRIPTION:
Cross Section 9880.8
END DESCRIPTION:
XS GIS Cut Line= 6
      3167094.66     13838539.58      3167036.75     13838629.09
      3166452.32     13838513.26      3166231.18     13838507.99
      3166059.87     13838603.17       3165204.1     13838514.17
#Sta/Elev= 30
  3958.5   28.07  3972.2   28.16  4018.5   27.46  4038.5   25.33  4065.1   20.41
  4145.1   22.21  4275.1   20.91  4412.2   12.04  4552.2    7.39  4661.2    9.59
  4781.2    5.74  4841.2    5.78    4864    7.04  4902.4    5.29  4926.2    5.68
  4937.7    4.65  4954.2   -5.98  4967.3   -9.86  4981.3   -9.86  4985.8   -6.35
  4999.2   -4.91  5023.4   -6.93    5041   -6.76  5051.2   -3.76  5056.3    1.72
    5079    7.04  5148.4    6.55  5358.4   15.84  5854.5    20.4  5938.8   21.17
#Mann= 6 , 1 , 0
  3958.5      .2       0  3972.2      .1       0    4864     .06       0
  4926.2     .04       0    5079      .1       0  5854.5      .2       0
Bank Sta=4926.2,5079
XS Rating Curve= 0 ,0
Exp/Cntr=0.5,0.3

Type RM Length L Ch R = 1 ,9683.0  ,40,40,40
BEGIN DESCRIPTION:
Upstream Section of Bridge/Culvert/Weir
END DESCRIPTION:
XS GIS Cut Line= 6
        3167077.     13838561.99      3166735.13     13838452.88
      3166531.47     13838416.51      3166084.13     13838361.96
      3165593.15     13838347.41      3165218.56     13838340.14
#Sta/Elev= 30
  3972.2    28.2  4020.3    23.6  4253.6    21.1  4625.7      24    4864   19.96
  4900.2    19.5  4908.9   17.12  4926.2    5.68  4937.7    4.65  4944.4    1.22
  4954.2   -5.98  4957.2   -3.72  4967.3   -9.86  4971.4   -5.04  4981.3   -9.86
  4985.8   -6.35  4995.1    -4.4  5023.4   -6.93  5051.1   -5.72  5051.2   -3.76
  5056.2    1.72    5079    7.04  5080.8   11.53  5093.4   10.49  5104.4   14.84
  5117.1   17.08  5175.7    17.6  5456.8    19.5  5852.5    19.9  5854.5    24.1
#Mann= 6 , 1 , 0
  3972.2      .2       0  3972.2      .1       0    4864     .06       0
  4900.2     .04       0  5104.4      .1       0  5854.5      .2       0
#XS Ineff= 2 , 0
       0    4865      26    5120       0      24
Permanent Ineff=
       F       F
Bank Sta=4900.2,5104.4
XS Rating Curve= 0 ,0
Exp/Cntr=0.5,0.3

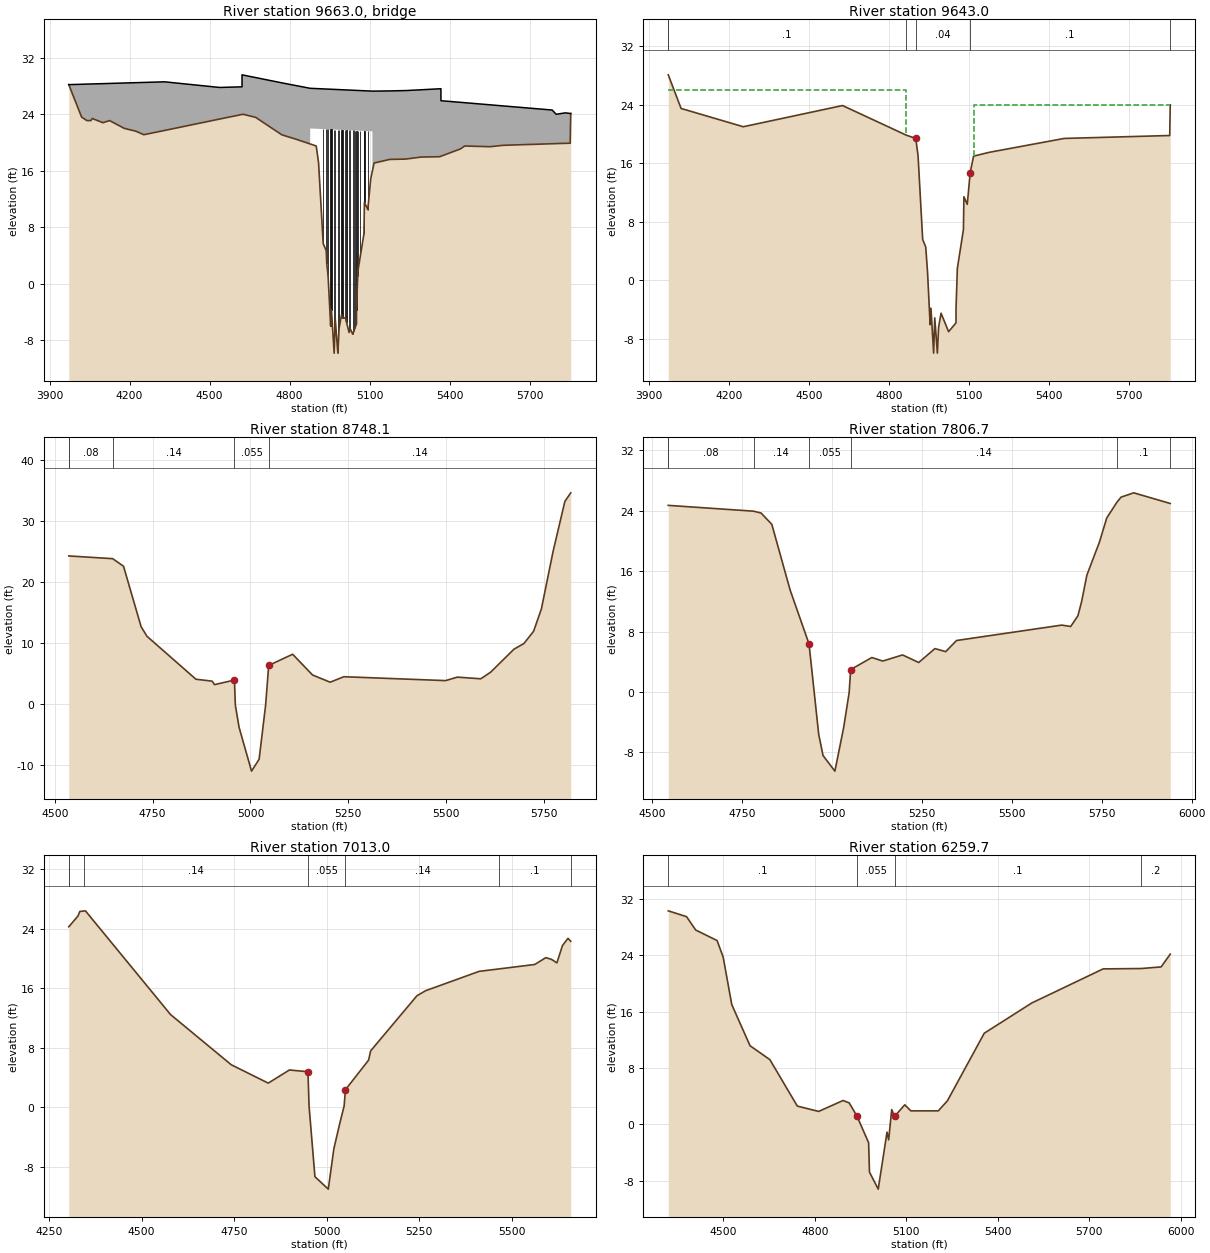
Type RM Length L Ch R = 3 ,9663.0  ,,,
BEGIN DESCRIPTION:
Port Terminal Railroad
Structure ID: H00-7
END DESCRIPTION:
Bridge Culvert--1,0,-1,-1, 0
Deck Dist Width WeirC Skew NumUp NumDn MinLoCord MaxHiCord MaxSubmerge Is_Ogee
10,20,2.6,0, 38, 38, , , 0.95, 0, 1,1,,
  3972.2  4020.3  4040.3  4055.3  4060.3  4100.3  4125.3  4180.3  4223.6  4253.6
  4331.1  4537.9 4621.79  4621.9  4625.6    4673  4771.5  4877.3 4877.41  4877.5
 5110.79  5110.9  5117.1  5175.7  5236.2    5293    5363  5367.7 5367.81  5441.8
  5456.8  5551.8  5601.8  5784.8  5799.8  5834.8  5852.5  5854.5
    28.2   28.25   28.28   28.29    28.3   28.34   28.37   28.43   28.48   28.51
    28.6    27.8   27.89   29.59   29.56    29.2   28.45   27.68   27.68   27.68
   27.28   27.28   27.28   27.31   27.36   27.47   27.61   27.62   25.92   25.69
   25.64   25.34   25.18    24.6      24    24.2   24.11    24.1
    28.2    23.6    23.1    23.1    23.4    22.8    23.1      22    21.6    21.1
    21.7   23.32   23.97   23.97      24   23.56   21.08   19.79   19.79   21.98
   21.58   15.99   17.08    17.6   17.65   17.93   17.98   18.05   18.05    19.1
    19.5    19.4    19.6   19.82   19.84   19.88    19.9    24.1
  3972.2  4020.3  4040.3  4055.3  4060.3  4100.3  4125.3  4180.3  4223.6  4253.6
  4331.1  4537.9 4621.79  4621.9  4625.6    4673  4771.5  4877.3 4877.41  4877.5
 5110.79  5110.9  5117.1  5175.7  5236.2    5293    5363  5367.7 5367.81  5441.8
  5456.8  5551.8  5601.8  5784.8  5799.8  5834.8  5852.5  5854.5
    28.2   28.25   28.28   28.29    28.3   28.34   28.37   28.43   28.48   28.51
    28.6    27.8   27.89   29.59   29.56    29.2   28.45   27.68   27.68   27.68
   27.28   27.28   27.28   27.31   27.36   27.47   27.61   27.62   25.92   25.69
   25.64   25.34   25.18    24.6      24    24.2   24.11    24.1
    28.1    23.5      23      23    23.3    22.7      23    21.9    21.5      21
    21.6   23.22   23.87   23.87    23.9   23.46   20.98   19.69   19.69   21.88
   21.48   15.89   16.98    17.5   17.55   17.83   17.88   17.95   17.95      19
    19.4    19.3    19.5   19.72   19.74   19.78    19.8      24
Pier Skew, UpSta & Num, DnSta & Num=  ,4926.2, 2 ,4926.2, 2 , 0 , 0 , 0 ,,
     1.3     1.3
    4.62    22.9
     1.3     1.3
    4.52    22.8
Pier Skew, UpSta & Num, DnSta & Num=  ,4937.7, 2 ,4937.7, 2 , 0 , 0 , 0 ,,
     1.3     1.3
    3.02   22.88
     1.3     1.3
    2.92   22.78
Pier Skew, UpSta & Num, DnSta & Num=  ,4939.6, 2 ,4939.6, 2 , 0 , 0 , 0 ,,
     1.3     1.3
    1.58   22.87
     1.3     1.3
    1.48   22.77
Pier Skew, UpSta & Num, DnSta & Num=  ,4944.3, 2 ,4944.3, 2 , 0 , 0 , 0 ,,
     1.3     1.3
    -.18   22.87
     1.3     1.3
    -.28   22.77
Pier Skew, UpSta & Num, DnSta & Num=  ,4954.2, 2 ,4954.2, 2 , 0 , 0 , 0 ,,
     1.3     1.3
    -6.5   22.85
     1.3     1.3
    -6.6   22.75
Pier Skew, UpSta & Num, DnSta & Num=  ,4957.2, 2 ,4957.2, 2 , 0 , 0 , 0 ,,
     1.3     1.3
   -5.21   22.84
     1.3     1.3
   -5.31   22.74
Pier Skew, UpSta & Num, DnSta & Num=  ,4967.3, 2 ,4967.3, 2 , 0 , 0 , 0 ,,
     1.3     1.3
  -10.46   22.83
     1.3     1.3
  -10.56   22.73
Pier Skew, UpSta & Num, DnSta & Num=  ,4971.4, 2 ,4971.4, 2 , 0 , 0 , 0 ,,
     1.3     1.3
    -6.8   22.82
     1.3     1.3
    -6.9   22.72
Pier Skew, UpSta & Num, DnSta & Num=  ,4981.3, 2 ,4981.3, 2 , 0 , 0 , 0 ,,
     1.3     1.3
  -10.54    22.8
     1.3     1.3
  -10.64    22.7
Pier Skew, UpSta & Num, DnSta & Num=  ,4985.8, 2 ,4985.8, 2 , 0 , 0 , 0 ,,
     1.3     1.3
   -7.86   22.79
     1.3     1.3
   -7.96   22.69
Pier Skew, UpSta & Num, DnSta & Num=  ,4995.1, 2 ,4995.1, 2 , 0 , 0 , 0 ,,
     1.3     1.3
   -5.54   22.78
     1.3     1.3
   -5.64   22.68
Pier Skew, UpSta & Num, DnSta & Num=  ,4999.2, 2 ,4999.2, 2 , 0 , 0 , 0 ,,
     1.3     1.3
   -5.91   22.77
     1.3     1.3
   -6.01   22.67
Pier Skew, UpSta & Num, DnSta & Num=  ,5009.2, 2 ,5009.2, 2 , 0 , 0 , 0 ,,
     1.3     1.3
   -5.94   22.75
     1.3     1.3
   -6.04   22.65
Pier Skew, UpSta & Num, DnSta & Num=  ,5013.3, 2 ,5013.3, 2 , 0 , 0 , 0 ,,
     1.3     1.3
   -6.54   22.75
     1.3     1.3
   -6.64   22.65
Pier Skew, UpSta & Num, DnSta & Num=  ,5023.4, 2 ,5023.4, 2 , 0 , 0 , 0 ,,
     1.3     1.3
   -7.83   22.73
     1.3     1.3
   -7.93   22.63
Pier Skew, UpSta & Num, DnSta & Num=  ,5027.1, 2 ,5027.1, 2 , 0 , 0 , 0 ,,
     1.3     1.3
   -7.47   22.72
     1.3     1.3
   -7.57   22.62
Pier Skew, UpSta & Num, DnSta & Num=  ,5037, 2 ,5037, 2 , 0 , 0 , 0 ,,
     1.3     1.3
   -8.13   22.71
     1.3     1.3
   -8.23   22.61
Pier Skew, UpSta & Num, DnSta & Num=  ,5041, 2 ,5041, 2 , 0 , 0 , 0 ,,
     1.3     1.3
   -7.83    22.7
     1.3     1.3
   -7.93    22.6
Pier Skew, UpSta & Num, DnSta & Num=  ,5046.1, 2 ,5046.1, 2 , 0 , 0 , 0 ,,
     1.3     1.3
    -7.3   22.69
     1.3     1.3
    -7.4   22.59
Pier Skew, UpSta & Num, DnSta & Num=  ,5051.2, 2 ,5051.2, 2 , 0 , 0 , 0 ,,
     1.3     1.3
   -6.78   22.68
     1.3     1.3
   -6.88   22.58
Pier Skew, UpSta & Num, DnSta & Num=  ,5055.7, 2 ,5055.7, 2 , 0 , 0 , 0 ,,
     1.3     1.3
    -.58   22.67
     1.3     1.3
    -.68   22.57
Pier Skew, UpSta & Num, DnSta & Num=  ,5065, 2 ,5065, 2 , 0 , 0 , 0 ,,
     1.3     1.3
    2.64   22.66
     1.3     1.3
    2.54   22.56
Pier Skew, UpSta & Num, DnSta & Num=  ,5079, 2 ,5079, 2 , 0 , 0 , 0 ,,
     1.3     1.3
    5.89   22.63
     1.3     1.3
    5.79   22.53
Pier Skew, UpSta & Num, DnSta & Num=  ,5080.8, 2 ,5080.8, 2 , 0 , 0 , 0 ,,
     1.3     1.3
    8.91   22.63
     1.3     1.3
    8.81   22.53
Pier Skew, UpSta & Num, DnSta & Num=  ,5093.4, 2 ,5093.4, 2 , 0 , 0 , 0 ,,
     1.3     1.3
    9.54   22.61
     1.3     1.3
    9.44   22.51
Abutment Skew #Up #Dn= , 2 , 2
  4877.3  4908.9
   21.98   17.12
  4877.3  4908.9
   21.88   17.02
Abutment Skew #Up #Dn= , 2 , 2
  5056.3 5110.99
    1.74   21.58
  5056.3 5110.99
    1.64   21.48
BR Coef= 1 , 1 , 0 ,1.25, 0 ,,,0.8,0,2,0,
WSPro=,,,, 1 ,,,, 0 ,,,, 0 ,,,,-1 ,-1 ,-1 , 0 , 0 , 0 , 0 , 0
BR U #Sta/Elev= 83
  3972.2    28.2  4020.3    23.6  4040.3    23.1  4055.3    23.1  4060.3    23.4
  4100.3    22.8  4125.3    23.1  4180.3      22  4223.6    21.6  4253.6    21.1
  4331.1    21.7  4537.9   23.32  4612.9    23.9  4621.4   23.97 4621.79   23.97
  4621.9   23.97 4622.01   23.97  4625.6      24  4625.7      24    4673   23.56
  4726.8    22.2    4730   22.12  4771.5   21.08    4827   20.43    4864   19.96
  4877.3   19.79 4877.41   19.79  4877.5   19.79  4900.2    19.5  4908.8   17.15
  4908.9   17.12  4926.2    5.68  4937.7    4.65  4939.6     2.8  4944.3    1.22
  4944.4    1.22  4954.2   -5.98  4957.2   -3.72  4967.3   -9.86  4971.4   -5.04
  4981.3   -9.86  4985.8   -6.35  4995.1    -4.4  4999.2   -4.91  5009.2   -4.84
  5013.3   -5.44  5023.4   -6.93  5027.1   -6.37    5037   -7.18    5041   -6.76
  5051.1   -5.72  5051.2   -3.76  5055.7    1.12  5056.2    1.72  5056.3    1.74
    5065    3.79    5079    7.04  5080.8   11.53  5093.4   10.49  5104.4   14.84
 5110.79   15.97  5110.9   15.99    5111      16  5117.1   17.08  5175.7    17.6
  5228.7   17.64  5236.2   17.65    5293   17.93  5362.9   17.98    5363   17.98
  5366.9   18.04 5367.59   18.05  5367.7   18.05 5367.81   18.05  5441.8    19.1
  5456.8    19.5  5551.8    19.4  5601.8    19.6  5784.8   19.82  5799.8   19.84
  5834.8   19.88  5852.5    19.9  5854.5    24.1
BR U #Mann= 6
  3972.2      .2  3972.2      .1    4864     .06  4900.2     .04  5104.4      .1
  5854.5      .2
BR U Banks=4900.2,5104.4
BR D #Sta/Elev= 83
  3972.2    28.1  4020.3    23.5  4040.3      23  4055.3      23  4060.3    23.3
  4100.3    22.7  4125.3      23  4180.3    21.9  4223.6    21.5  4253.6      21
  4331.1    21.6  4537.9   23.22  4612.9    23.8  4621.4   23.87 4621.79   23.87
  4621.9   23.87 4622.01   23.87  4625.6    23.9  4625.7    23.9    4673   23.46
  4726.8    22.1    4730   22.02  4771.5   20.98    4827   20.33    4864   19.86
  4877.3   19.69 4877.41   19.69  4877.5   19.69  4900.2    19.4  4908.8   17.05
  4908.9   17.02  4926.2    5.58  4937.7    4.55  4939.6     2.7  4944.3    1.12
  4944.4    1.12  4954.2   -6.08  4957.2   -3.82  4967.3   -9.96  4971.4   -5.14
  4981.3   -9.96  4985.8   -6.45  4995.1    -4.5  4999.2   -5.01  5009.2   -4.94
  5013.3   -5.54  5023.4   -7.03  5027.1   -6.47    5037   -7.28    5041   -6.86
  5051.1   -5.82  5051.2   -3.86  5055.7    1.02  5056.2    1.62  5056.3    1.64
    5065    3.69    5079    6.94  5080.8   11.43  5093.4   10.39  5104.4   14.74
 5110.79   15.87  5110.9   15.89    5111    15.9  5117.1   16.98  5175.7    17.5
  5228.7   17.54  5236.2   17.55    5293   17.83  5362.9   17.88    5363   17.88
  5366.9   17.94 5367.59   17.95  5367.7   17.95 5367.81   17.95  5441.8      19
  5456.8    19.4  5551.8    19.3  5601.8    19.5  5784.8   19.72  5799.8   19.74
  5834.8   19.78  5852.5    19.8  5854.5      24
BR D #Mann= 6
  3972.2      .2  3972.2      .1    4864     .06  4900.2     .04  5104.4      .1
  5854.5      .2
BR D Banks=4900.2,5104.4
BC Design=,, 0 ,, 0 ,,,,,,
BC HTab HWMax=28.2
BC Use User HTab Curves=0
BC User HTab FreeFlow(D)= 0

Type RM Length L Ch R = 1 ,9643.0  ,894.9,894.9,894.9
BEGIN DESCRIPTION:
Downstream Section of Bridge/Culvert/Weir
END DESCRIPTION:
XS GIS Cut Line= 6
        3167077.     13838521.99      3166735.13     13838412.88
      3166531.47     13838376.51      3166084.13     13838321.96
      3165593.15     13838307.41      3165218.56     13838300.14
#Sta/Elev= 30
  3972.2   28.09  4020.3   23.49  4253.6   20.99  4625.7   23.89    4864   19.85
  4900.2   19.39  4908.9   17.01  4926.2    5.57  4937.7    4.54  4944.4    1.11
  4954.2   -6.09  4957.2   -3.83  4967.3   -9.97  4971.4   -5.15  4981.3   -9.97
  4985.8   -6.46  4995.1   -4.51  5023.4   -7.04  5051.1   -5.83  5051.2   -3.87
  5056.2    1.61    5079    6.93  5080.8   11.42  5093.4   10.38  5104.4   14.73
  5117.1   16.97  5175.7   17.49  5456.8   19.39  5852.5   19.79  5854.5   23.99
#Mann= 6 , 1 , 0
  3972.2      .2       0  3972.2      .1       0    4864     .06       0
  4900.2     .04       0  5104.4      .1       0  5854.5      .2       0
#XS Ineff= 2 , 0
       0    4865      26    5120       0      24
Permanent Ineff=
       F       F
Bank Sta=4900.2,5104.4
XS Rating Curve= 0 ,0
Exp/Cntr=0.5,0.3

Type RM Length L Ch R = 1 ,8748.1  ,828,941.4,1227.1
BEGIN DESCRIPTION:
Cross Section 8748.1
END DESCRIPTION:
XS GIS Cut Line= 4
      3166982.44      13837734.6      3166622.39      13837665.5
      3166407.81     13837592.76      3165736.24     13837434.19
#Sta/Elev= 30
  4535.5   24.32  4647.8   23.87  4675.5   22.63  4720.5   12.71  4735.5   11.15
  4860.5    4.12  4902.1     3.8  4908.2    3.23    4959    3.98  4961.3    -.12
  4970.9   -3.77  5002.7  -10.94  5022.1   -8.99  5038.7    -.13  5046.6    6.38
  5107.8    8.21  5158.7    4.81  5203.7    3.63  5238.7    4.53  5498.7    3.89
  5528.7    4.46  5588.7    4.19  5613.7    5.26  5673.7    9.05  5698.7    9.95
  5723.7   11.97  5743.7   15.65  5773.7   25.11  5803.7   33.26  5818.7   34.66
#Mann= 5 , 1 , 0
  4535.5      .2       0  4535.5     .08       0  4647.8     .14       0
    4959    .055       0  5046.6     .14       0
Bank Sta=4959,5046.6
XS Rating Curve= 0 ,0
Exp/Cntr=0.3,0.1

Type RM Length L Ch R = 1 ,7806.7  ,684.9,793.7,722.7
BEGIN DESCRIPTION:
Cross Section 7806.7
END DESCRIPTION:
XS GIS Cut Line= 6
      3166946.07     13837236.35      3166931.52     13837029.05
      3166855.15     13836901.75      3166796.96     13836705.36
      3166735.13      13836363.5      3166571.47     13835905.25
#Sta/Elev= 30
  4545.4   24.71  4782.4   23.94  4803.2    23.7  4833.2    22.2  4884.1    13.5
  4936.6    6.37  4963.5    -5.6  4975.6   -8.41  5008.5  -10.47  5032.8   -4.72
  5048.1    -.09  5052.3    2.97  5111.2    4.57  5141.5     4.1  5196.5    4.91
  5241.5    3.91  5286.5    5.75  5316.5    5.35  5346.5    6.82  5638.9    8.86
  5663.9    8.68  5683.9   10.09  5693.9   11.92  5708.9   15.49  5743.9   19.87
  5763.9   23.03  5792.5   25.14  5803.9    25.8  5838.9   26.37  5940.5   24.96
#Mann= 7 , 1 , 0
  4545.4      .2       0  4545.4     .08       0  4782.4     .14       0
  4936.6    .055       0  5052.3     .14       0  5792.5      .1       0
  5940.5      .2       0
Bank Sta=4936.6,5052.3
XS Rating Curve= 0 ,0
Exp/Cntr=0.3,0.1

Type RM Length L Ch R = 1 ,7013.0  ,745.3,753.3,744.5
BEGIN DESCRIPTION:
Cross Section 7013.0
END DESCRIPTION:
XS GIS Cut Line= 6
      3167280.66     13836887.21      3167244.29     13836614.44
      3167233.38     13836450.78      3167218.84     13836134.37
      3167277.03     13835934.35      3167327.94      13835545.2
#Sta/Elev= 30
  4303.2   24.29  4328.2   25.75  4333.2   26.36  4343.2   26.41  4348.2   26.44
  4578.4   12.48  4742.4    5.73  4842.4    3.26  4899.6    5.03  4949.7    4.79
  4952.6      .2  4968.5   -9.33  5004.6     -11  5019.7   -5.56  5035.2   -2.25
  5047.4     .18  5050.9    2.37  5113.6    6.36  5119.1     7.6  5244.1   15.01
  5267.5   15.69  5412.5    18.3  5467.1   18.63  5562.5   19.22  5592.5   20.14
  5607.5   19.92  5622.5   19.44  5637.5   21.77  5652.5   22.74  5659.9   22.34
#Mann= 7 , 1 , 0
  4303.2      .2       0  4303.2     .08       0  4343.2     .14       0
  4949.7    .055       0  5050.9     .14       0  5467.1      .1       0
  5659.9      .2       0
Bank Sta=4949.7,5050.9
XS Rating Curve= 0 ,0
Exp/Cntr=0.3,0.1

Type RM Length L Ch R = 1 ,6259.7  ,665.2,681.3,662.3
BEGIN DESCRIPTION:
Cross Section 6257.7
END DESCRIPTION:
XS GIS Cut Line= 6
       3168131.9     13836849.47      3167963.41     13836623.07
      3167968.68     13835870.16      3167937.09     13835717.47
      3167747.54     13835580.57      3167538.81     13835510.99
#Sta/Elev= 30
  4319.4   30.32  4379.4   29.49  4409.4   27.59  4479.4    26.1  4499.4   23.75
  4527.6      17  4587.6   11.15  4652.5    9.18  4742.5    2.58  4812.5    1.82
  4892.5    3.37  4912.5    3.04  4937.6    1.19  4976.3   -2.62  4979.1    -6.8
  5007.8   -9.22  5036.6   -1.12    5042   -2.22    5052    2.08  5061.2    1.11
  5094.8    2.76  5114.8     1.9  5204.8     1.9  5234.8    3.34  5355.4   12.93
  5511.4   17.23  5745.2   22.07  5868.8   22.12  5935.2   22.35  5965.2   24.17
#Mann= 4 , 1 , 0
  4319.4      .1       0  4937.6    .055       0  5061.2      .1       0
  5868.8      .2       0
Bank Sta=4937.6,5061.2
XS Rating Curve= 0 ,0
Exp/Cntr=0.5,0.3