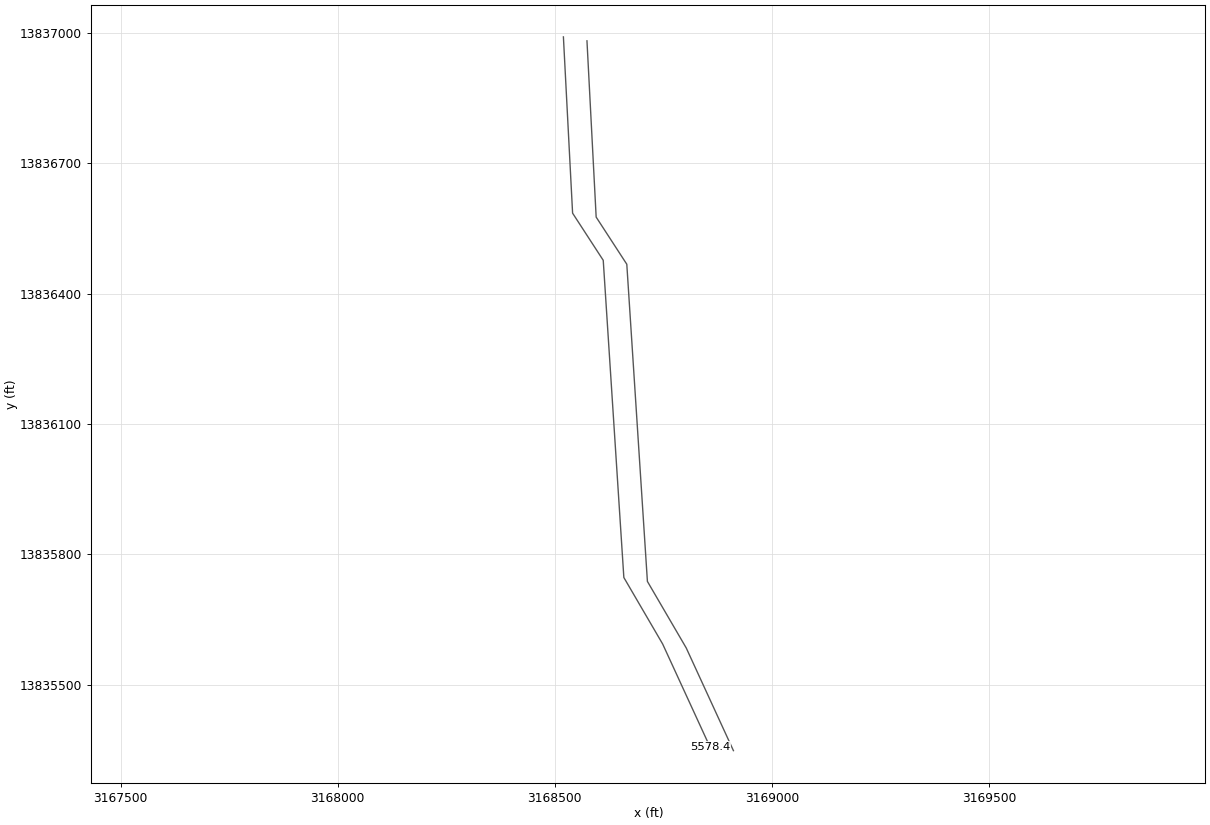
HEC-RAS study H100-00-00.prj: H100-00-00

--- H100-00-00.g01 (geometry) --- (continued)

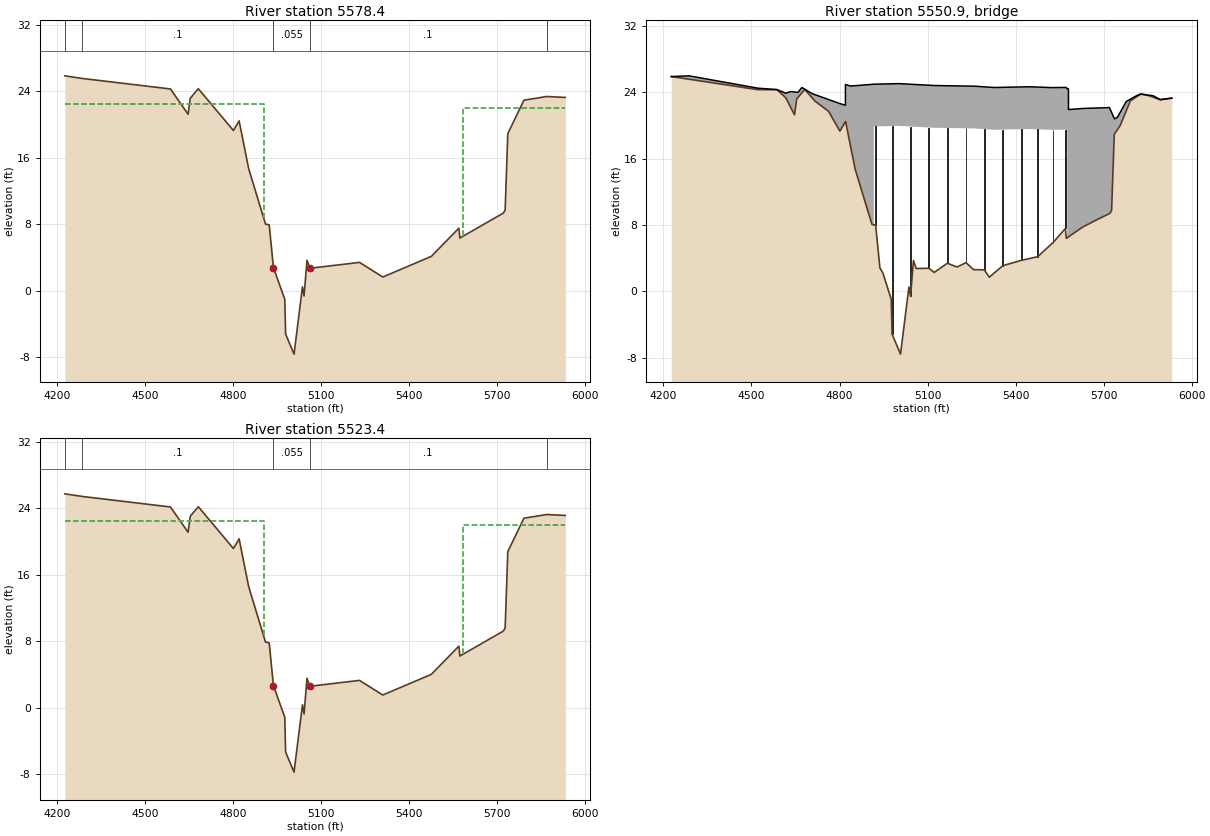
Type RM Length L Ch R = 1 ,5578.4  ,55,55,55
BEGIN DESCRIPTION:
Upstream Section of Bridge/Culvert/Weir
END DESCRIPTION:
XS GIS Cut Line= 6
      3168519.73     13836991.43       3168540.9     13836585.52
      3168611.46     13836476.94      3168658.92     13835746.49
      3168748.29     13835593.36      3168857.02     13835356.82
#Sta/Elev= 30
  4226.7   25.88  4286.9   25.56  4586.7    24.3  4646.7   21.26  4654.2   23.18
  4681.6   24.33  4801.3    19.3  4820.7   20.46  4853.2   14.72  4910.6    8.04
  4923.2    7.95  4937.6     2.8  4976.3   -1.01  4979.1   -5.19  5007.8   -7.61
  5036.6     .49    5042    -.61    5052    3.69  5061.2    2.72  5230.9    3.43
  5310.3    1.67  5475.5    4.15  5569.6    7.55    5573    6.36    5721    9.36
  5727.2    9.72  5736.3   18.92  5791.3   22.95  5868.8   23.39  5932.4   23.28
#Mann= 5 , 1 , 0
  4226.7      .2       0  4286.9      .1       0  4937.6    .055       0
  5061.2      .1       0  5868.8      .2       0
#XS Ineff= 2 , 0
       0    4905   22.45    5585       0      22
Permanent Ineff=
       F       F
Bank Sta=4937.6,5061.2
XS Rating Curve= 0 ,0
Exp/Cntr=0.5,0.3

Type RM Length L Ch R = 3 ,5550.9  ,,,
BEGIN DESCRIPTION:
HOUSTON WATER SUPPLY PLANT
Structure ID: H00-4,,,,
END DESCRIPTION:
Bridge Culvert--1,0,-1,-1, 0
Deck Dist Width WeirC Skew NumUp NumDn MinLoCord MaxHiCord MaxSubmerge Is_Ogee
10,35,2.6,0, 50, 50, , , 0.95, 0, 1,1,,
  4226.7  4286.9  4521.7  4586.7  4616.9  4633.2  4646.7  4654.2  4658.2  4671.8
  4681.6  4707.1  4716.1  4762.6  4801.3 4820.09  4820.2  4820.7    4837  4853.2
  4910.6  4916.7 4916.81  4916.9  5001.9  5122.6  5260.4  5326.5  5446.9  5523.6
  5572.4 5576.09  5576.2  5580.2 5580.31  5628.7  5719.8  5727.2  5736.3  5737.1
  5747.1  5756.3  5777.1  5791.3  5812.1  5826.3  5847.7  5868.8  5892.7  5932.4
   25.91      26   24.51   24.34    23.9    24.1   24.05   24.02      24   24.59
   24.38   23.84   23.73   23.14   22.65   22.45   24.95   24.95   24.77   24.81
   24.97   24.99   24.99   24.99   25.06   24.83   24.75   24.59   24.68   24.58
    24.6   24.43   24.42   24.43   21.93   22.06   22.17   21.58   20.86    20.8
      21   21.58    22.9   23.18    23.6    23.8   23.69    23.6   23.12   23.31
   25.91   25.59   24.33   24.33   23.35   22.22   21.29   23.21   23.38   23.95
   24.36   23.33   22.96   21.72   19.33   20.45   20.46   20.49   17.61   14.75
    8.07    8.03    8.03   19.89   19.96   19.73   19.65   19.49   19.58   19.48
    19.5   19.33    6.47    6.57    6.57    7.75    9.37    9.75   18.95   18.99
   19.51   19.99   21.77   22.98   23.46   23.79   23.68   23.42   23.12   23.31
  4226.7  4286.9  4521.7  4586.7  4616.9  4633.2  4646.7  4654.2  4658.2  4671.8
  4681.6  4707.1  4716.1  4762.6  4801.3 4820.09  4820.2  4820.7    4837  4853.2
  4910.6  4916.7 4916.81  4916.9  5001.9  5122.6  5260.4  5326.5  5446.9  5523.6
  5572.4 5576.09  5576.2  5580.2 5580.31  5628.7  5719.8  5727.2  5736.3  5737.1
  5747.1  5756.3  5777.1  5791.3  5812.1  5826.3  5847.7  5868.8  5892.7  5932.4
   25.91      26   24.51   24.34    23.9    24.1   24.05   24.02      24   24.59
   24.38   23.84   23.73   23.14   22.65   22.45   24.95   24.95   24.77   24.81
   24.97   24.99   24.99   24.99   25.06   24.83   24.75   24.59   24.68   24.58
    24.6   24.43   24.42   24.43   21.93   22.06   22.17   21.58   20.86    20.8
      21   21.58    22.9   23.18    23.6    23.8   23.69    23.6   23.12   23.31
    25.8   25.48   24.22   24.22   23.24   22.11   21.18    23.1   23.27   23.84
   24.25   23.22   22.85   21.61   19.22   20.34   20.35   20.38    17.5   14.64
    7.96    7.92    7.92   19.78   19.85   19.62   19.54   19.38   19.47   19.37
   19.39   19.22    6.36    6.46    6.46    7.64    9.26    9.64   18.84   18.88
    19.4   19.88   21.66   22.87   23.35   23.68   23.57   23.31   23.01    23.2
Pier Skew, UpSta & Num, DnSta & Num=  ,4923.2, 2 ,4923.2, 2 , 0 , 0 , 0 ,,
       3       3
    6.44    20.9
       3       3
    6.33   20.79
Pier Skew, UpSta & Num, DnSta & Num=  ,4979.1, 2 ,4979.1, 2 , 0 , 0 , 0 ,,
       3       3
   -6.29   20.94
       3       3
    -6.4   20.83
Pier Skew, UpSta & Num, DnSta & Num=  ,5042, 2 ,5042, 2 , 0 , 0 , 0 ,,
       3       3
   -1.27   20.88
       3       3
   -1.38   20.77
Pier Skew, UpSta & Num, DnSta & Num=  ,5104.6, 2 ,5104.6, 2 , 0 , 0 , 0 ,,
       3       3
    1.74   20.76
       3       3
    1.63   20.65
Pier Skew, UpSta & Num, DnSta & Num=  ,5167.6, 2 ,5167.6, 2 , 0 , 0 , 0 ,,
       3       3
    2.35   20.69
       3       3
    2.24   20.58
Pier Skew, UpSta & Num, DnSta & Num=  ,5230.9, 2 ,5230.9, 2 , 0 , 0 , 0 ,,
       3       3
    2.41   20.66
       3       3
     2.3   20.55
Pier Skew, UpSta & Num, DnSta & Num=  ,5293.5, 2 ,5293.5, 2 , 0 , 0 , 0 ,,
       3       3
    1.51   20.57
       3       3
     1.4   20.46
Pier Skew, UpSta & Num, DnSta & Num=  ,5356.2, 2 ,5356.2, 2 , 0 , 0 , 0 ,,
       3       3
    2.04   20.51
       3       3
    1.93    20.4
Pier Skew, UpSta & Num, DnSta & Num=  ,5419.1, 2 ,5419.1, 2 , 0 , 0 , 0 ,,
       3       3
    2.71   20.56
       3       3
     2.6   20.45
Pier Skew, UpSta & Num, DnSta & Num=  ,5475.5, 2 ,5475.5, 2 , 0 , 0 , 0 ,,
       3       3
    3.17   20.54
       3       3
    3.06   20.43
Pier Skew, UpSta & Num, DnSta & Num=  ,5527.4, 2 ,5527.4, 2 , 0 , 0 , 0 ,,
       3       3
    4.82   20.48
       3       3
    4.71   20.37
Pier Skew, UpSta & Num, DnSta & Num=  ,5569.6, 2 ,5569.6, 2 , 0 , 0 , 0 ,,
       3       3
    6.05    20.5
       3       3
    5.94   20.39
BR Coef= 1 , 1 , 0 ,1.25, 0 ,,,0.8,0,2,0,
WSPro=,,,, 1 ,,,, 0 ,,,, 0 ,,,,-1 ,-1 ,-1 , 0 , 0 , 0 , 0 , 0
BR U #Sta/Elev= 89
  4226.7   25.91  4286.9   25.59  4521.7   24.33  4586.7   24.33  4616.7   23.36
  4616.9   23.35  4633.2   22.22  4646.7   21.29  4654.2   23.21  4658.2   23.38
  4671.8   23.95  4681.6   24.36  4707.1   23.33  4716.1   22.96  4754.4   21.94
  4762.6   21.72  4801.3   19.33  4802.5    19.4 4820.09   20.45  4820.2   20.46
 4820.31   20.47  4820.7   20.49    4837   17.61  4853.2   14.75  4910.6    8.07
  4916.7    8.03 4916.81    8.03  4916.9    8.03    4917    8.02  4923.2    7.98
  4937.6    2.83  4947.9     2.2  4976.3    -.98  4979.1   -5.16  5001.9   -7.08
  5007.8   -7.58  5036.6     .52    5042    -.58    5052    3.72  5061.2    2.75
  5104.6    2.78  5116.2    2.46  5122.6    2.28  5167.6    3.39    5189    3.09
  5200.9    2.93  5230.9    3.46    5257    2.61  5260.4    2.61  5293.5    2.59
  5310.3     1.7  5326.5    2.19  5356.3    3.09  5394.4    3.48  5419.1    3.73
  5446.9    3.95  5475.5    4.18  5523.6    5.75  5527.4    5.87  5569.6    7.58
  5572.4     6.6    5573    6.39    5576    6.46 5576.09    6.47  5576.2    6.47
  5576.3    6.47 5580.09    6.56  5580.2    6.57 5580.31    6.57  5616.3    7.45
  5628.7    7.75  5678.4    8.66  5685.2    8.78  5719.8    9.37    5721    9.39
  5727.2    9.75  5736.3   18.95  5737.1   18.99  5747.1   19.51  5756.3   19.99
  5777.1   21.77  5791.3   22.98  5812.1   23.46  5826.3   23.79  5842.1   23.71
  5847.7   23.68  5868.8   23.42  5892.7   23.12  5932.4   23.31
BR U #Mann= 5
  4226.7      .2  4286.9      .1  4937.6    .055  5061.2      .1  5868.8      .2
BR U Banks=4937.6,5061.2
BR D #Sta/Elev= 89
  4226.7    25.8  4286.9   25.48  4521.7   24.22  4586.7   24.22  4616.7   23.25
  4616.9   23.24  4633.2   22.11  4646.7   21.18  4654.2    23.1  4658.2   23.27
  4671.8   23.84  4681.6   24.25  4707.1   23.22  4716.1   22.85  4754.4   21.83
  4762.6   21.61  4801.3   19.22  4802.5   19.29 4820.09   20.34  4820.2   20.35
 4820.31   20.36  4820.7   20.38    4837    17.5  4853.2   14.64  4910.6    7.96
  4916.7    7.92 4916.81    7.92  4916.9    7.92    4917    7.91  4923.2    7.87
  4937.6    2.72  4947.9    2.09  4976.3   -1.09  4979.1   -5.27  5001.9   -7.19
  5007.8   -7.69  5036.6     .41    5042    -.69    5052    3.61  5061.2    2.64
  5104.6    2.67  5116.2    2.35  5122.6    2.17  5167.6    3.28    5189    2.98
  5200.9    2.82  5230.9    3.35    5257     2.5  5260.4     2.5  5293.5    2.48
  5310.3    1.59  5326.5    2.08  5356.3    2.98  5394.4    3.37  5419.1    3.62
  5446.9    3.84  5475.5    4.07  5523.6    5.64  5527.4    5.76  5569.6    7.47
  5572.4    6.49    5573    6.28    5576    6.35 5576.09    6.36  5576.2    6.36
  5576.3    6.36 5580.09    6.45  5580.2    6.46 5580.31    6.46  5616.3    7.34
  5628.7    7.64  5678.4    8.55  5685.2    8.67  5719.8    9.26    5721    9.28
  5727.2    9.64  5736.3   18.84  5737.1   18.88  5747.1    19.4  5756.3   19.88
  5777.1   21.66  5791.3   22.87  5812.1   23.35  5826.3   23.68  5842.1    23.6
  5847.7   23.57  5868.8   23.31  5892.7   23.01  5932.4    23.2
BR D #Mann= 5
  4226.7      .2  4286.9      .1  4937.6    .055  5061.2      .1  5868.8      .2
BR D Banks=4937.6,5061.2
BC Design=,, 0 ,, 0 ,,,,,,
BC HTab HWMax=25.88
BC Use User HTab Curves=0
BC User HTab FreeFlow(D)= 0

Type RM Length L Ch R = 1 ,5523.4  ,513.7,513.7,513.7
BEGIN DESCRIPTION:
Downstream Section of Bridge/Culvert/Weir
END DESCRIPTION:
XS GIS Cut Line= 6
      3168573.98     13836982.39      3168595.16     13836576.48
      3168665.72      13836467.9      3168713.18     13835737.45
      3168802.55     13835584.32      3168911.27     13835347.78
#Sta/Elev= 30
  4226.7   25.75  4286.9   25.43  4586.7   24.17  4646.7   21.13  4654.2   23.05
  4681.6    24.2  4801.3   19.17  4820.7   20.33  4853.2   14.59  4910.6    7.91
  4923.2    7.82  4937.6    2.67  4976.3   -1.14  4979.1   -5.32  5007.8   -7.74
  5036.6     .36    5042    -.74    5052    3.56  5061.2    2.59  5230.9     3.3
  5310.3    1.54  5475.5    4.02  5569.6    7.42    5573    6.23    5721    9.23
  5727.2    9.59  5736.3   18.79  5791.3   22.82  5868.8   23.26  5932.4   23.15
#Mann= 5 , 1 , 0
  4226.7      .2       0  4286.9      .1       0  4937.6    .055       0
  5061.2      .1       0  5868.8      .2       0
#XS Ineff= 2 , 0
       0    4905   22.45    5585       0      22
Permanent Ineff=
       F       F
Bank Sta=4937.6,5061.2
XS Rating Curve= 0 ,0
Exp/Cntr=0.5,0.3