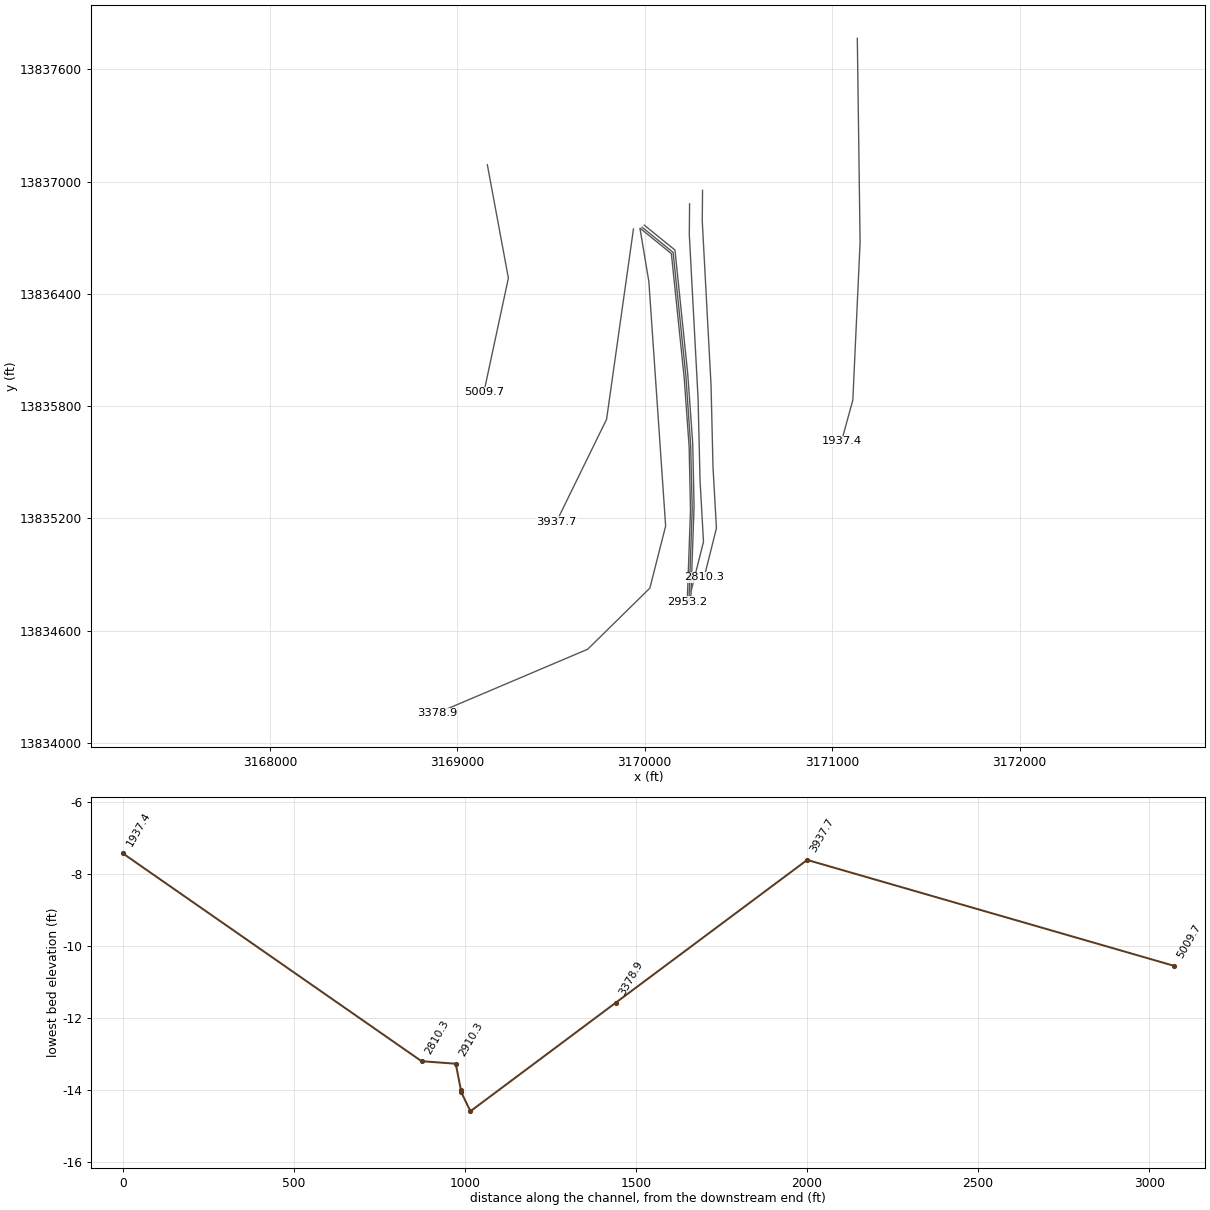
HEC-RAS study H100-00-00.prj: H100-00-00

--- H100-00-00.g01 (geometry) --- (continued)

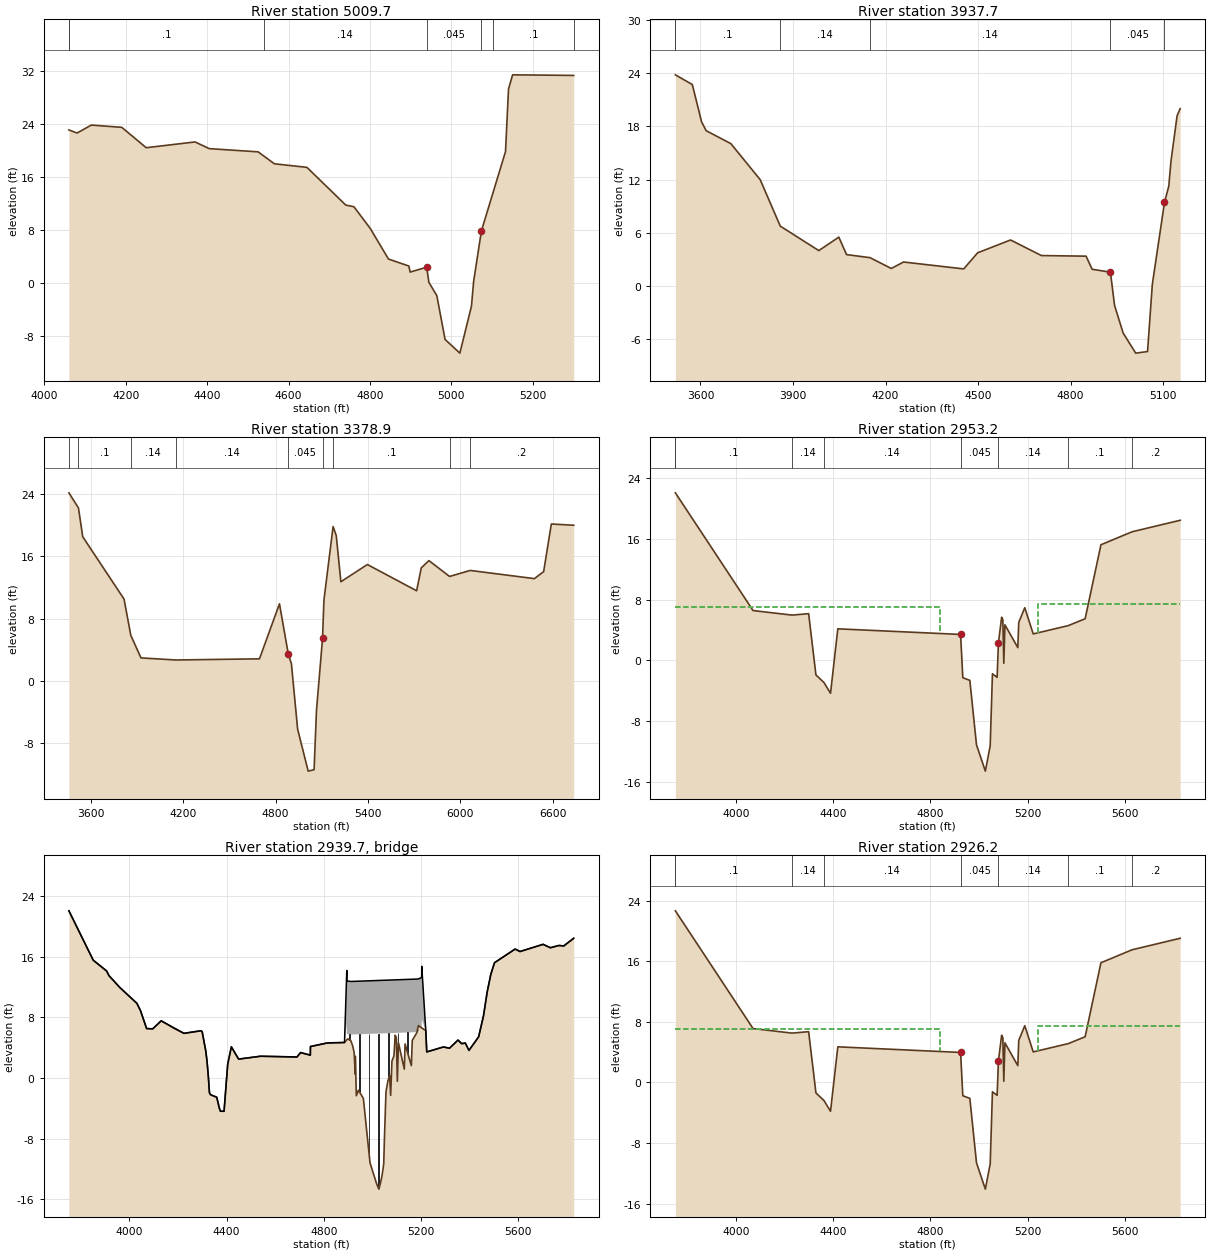
Type RM Length L Ch R = 1 ,5009.7  ,898.4,1072,1003.8
BEGIN DESCRIPTION:
Cross Section 5009.7
END DESCRIPTION:
XS GIS Cut Line= 3
      3169160.13     13837089.35      3169272.41     13836484.28
      3169141.42     13835872.97
#Sta/Elev= 30
  4060.3   23.06  4080.3   22.59  4115.3   23.79  4190.3   23.45  4250.3   20.38
  4370.3   21.25  4405.3   20.24  4525.3   19.76  4539.5   19.12  4565.3   17.96
  4645.3   17.42  4740.7   11.74  4760.7   11.49  4800.7    8.24  4845.7    3.61
  4895.7    2.56    4899    1.65  4939.6    2.38    4945      .1  4964.5    -1.9
  4984.8    -8.5  5021.1  -10.56  5049.6   -3.49    5055     .25    5074    7.83
  5102.7   13.62  5133.3    19.8  5140.7   29.21  5150.7   31.36  5300.9   31.27
#Mann= 7 , 1 , 0
  4060.3      .2       0  4060.3      .1       0  4539.5     .14       0
  4939.6    .045       0    5074     .14       0  5102.7      .1       0
  5300.9      .2       0
Bank Sta=4939.6,5074
XS Rating Curve= 0 ,0
Exp/Cntr=0.3,0.1

Type RM Length L Ch R = 1 ,3937.7  ,286.1,558.8,594.7
BEGIN DESCRIPTION:
Cross Section 3937.7
END DESCRIPTION:
XS GIS Cut Line= 3
      3169939.86     13836746.27      3169796.39      13835729.5
      3169528.49     13835181.52
#Sta/Elev= 30
  3518.6   23.84  3573.6   22.74  3603.6   18.52  3618.6   17.52  3698.6   16.06
  3793.6   11.99  3858.7    6.74  3983.6    3.97  4048.6    5.49  4073.6    3.52
  4149.9    3.17  4218.6    1.95  4258.6    2.68  4453.6     1.9  4498.6    3.72
  4605.4    5.17  4705.4    3.41  4850.4    3.34  4869.9    1.86  4929.3    1.53
  4942.6   -2.22  4970.5   -5.35  5011.2   -7.62  5049.6   -7.44  5065.1     .15
  5104.5    9.41  5118.5   11.26  5125.4   14.02  5145.4   19.21  5155.4   20.01
#Mann= 6 , 1 , 0
  3518.6      .2       0  3518.6      .1       0  3858.7     .14       0
  4149.9     .14       0  4929.3    .045       0  5104.5      .1       0
Bank Sta=4929.3,5104.5
XS Rating Curve= 0 ,0
Exp/Cntr=0.3,0.1

Type RM Length L Ch R = 1 ,3378.9  ,182.5,425.7,183.2
BEGIN DESCRIPTION:
Cross Section 3378.9
END DESCRIPTION:
XS GIS Cut Line= 6
       3169974.7     13836749.44      3170022.08     13836465.12
      3170111.59     13835159.36      3170027.35     13834827.66
      3169695.64     13834501.22      3168890.08     13834158.99
#Sta/Elev= 30
  3456.5   24.13  3518.6   22.19  3546.5   18.49  3814.7    10.5  3858.7    5.85
  3924.7    2.95  4149.9    2.68  4694.7    2.83  4824.7    9.89  4882.2    3.42
  4902.2    2.21  4942.6   -6.18  5011.2  -11.58  5049.6   -11.4  5065.1   -3.81
  5104.5    5.45  5113.6   10.36  5173.1    19.8  5193.6   18.64  5223.6   12.72
  5395.9   14.93  5715.9   11.56  5745.9    14.5  5795.9   15.43    5930    13.4
  6064.1   14.17  6481.2   13.12  6541.2   14.02  6591.2   20.13  6736.5   19.97
#Mann= 9 , 1 , 0
  3456.5      .2       0  3518.6      .1       0  3858.7     .14       0
  4149.9     .14       0  4882.2    .045       0  5104.5      .1       0
  5173.1      .1       0    5930      .1       0  6064.1      .2       0
Bank Sta=4882.2,5104.5
XS Rating Curve= 0 ,0
Exp/Cntr=0.5,0.3

Type RM Length L Ch R = 1 ,2953.2  ,27,27,27
BEGIN DESCRIPTION:
Upstream Section of Bridge/Culvert/Weir
END DESCRIPTION:
XS GIS Cut Line= 6
      3169978.49     13836747.93      3170142.13     13836614.98
      3170210.48      13835952.3      3170237.01     13835581.74
      3170244.17     13835244.93       3170226.8     13834754.17
#Sta/Elev= 30
  3751.5   22.11  4071.1    6.58  4231.5    5.98  4299.7    6.17  4329.7   -1.91
  4362.9   -2.92  4389.7   -4.33  4419.7    4.17 4924.78    3.43  4933.9   -2.28
 4962.81   -2.63 4990.17  -11.13 5026.58   -14.6 5046.52  -11.27 5055.78   -1.76
 5075.01   -2.23 5080.39     2.3 5093.54     5.7 5098.56    5.38 5102.52    -.37
 5107.11     4.7 5160.14    1.69 5164.02    5.02 5188.77    6.96  5223.5     3.5
  5367.4    4.59  5437.1     5.5  5502.1   15.26    5630   16.97    5828   18.49
#Mann= 8 , 1 , 0
  3751.5      .2       0  3751.5      .1       0  4231.5     .14       0
  4362.9     .14       0 4924.78    .045       0 5080.39     .14       0
  5367.4      .1       0    5630      .2       0
#XS Ineff= 2 , 0
       0    4840       7    5245       0     7.5
Permanent Ineff=
       F       F
Bank Sta=4924.78,5080.39
XS Rating Curve= 0 ,0
Exp/Cntr=0.5,0.3

Type RM Length L Ch R = 3 ,2939.7  ,,,
BEGIN DESCRIPTION:
7' Wide Pipe Bridge - 45 Degree Skew
Structure ID: H00-2
END DESCRIPTION:
Bridge Culvert--1,0,-1,-1, 0
Deck Dist Width WeirC Skew NumUp NumDn MinLoCord MaxHiCord MaxSubmerge Is_Ogee
10,7,2.6,0, 60, 60, , , 0.95, 0, 1,1,,
  3751.5  3851.5  3906.5  3916.1  3961.1  4031.1  4046.1  4071.1  4096.1  4131.1
  4224.7  4294.7  4299.7  4314.7  4319.7  4324.7  4329.7  4334.7  4359.7  4369.7
  4374.7  4389.7  4404.7  4419.7  4449.7  4539.7  4689.6  4704.6  4744.6 4745.13
 4814.48 4884.97  4885.2 4894.52 4894.59 4909.79  5183.4 5188.77 5202.56 5202.91
 5219.59  5223.5  5292.1  5317.1  5352.1  5367.1  5382.1  5397.1  5437.1  5457.1
  5472.1  5487.1  5502.1  5587.1  5607.1  5702.1  5732.1  5767.1  5787.1    5828
   22.04   15.53   14.11    13.5   11.92    9.84    8.87    6.51    6.47    7.53
    5.88    6.22     6.1    3.51    2.19     .33   -1.98   -2.23   -2.55   -3.91
   -4.39    -4.4     1.8     4.1    2.48    2.86    2.76    3.34       3    4.14
    4.61    4.67    4.68   14.18   12.81   12.72   13.04   13.05   13.26   14.72
    6.23    3.43    4.08    3.92    4.99    4.52     4.6    3.63    5.43    8.22
   11.34   13.67   15.19      17   16.67   17.62   17.17   17.47   17.41   18.42
   22.04   15.53   14.11    13.5   11.92    9.84    8.87    6.51    6.47    7.53
    5.88    6.22     6.1    3.51    2.19     .33   -1.98   -2.23   -2.55   -3.91
   -4.39    -4.4     1.8     4.1    2.48    2.86    2.76    3.34       3    4.14
    4.61    4.67    4.68    7.18    5.81    5.72    6.04    6.89    6.59    7.72
    6.23    3.43    4.08    3.92    4.99    4.52     4.6    3.63    5.43    8.22
   11.34   13.67   15.19      17   16.67   17.62   17.17   17.47   17.41   18.42
  3751.5  3851.5  3906.5  3916.1  3961.1  4031.1  4046.1  4071.1  4096.1  4131.1
  4224.7  4294.7  4299.7  4314.7  4319.7  4324.7  4329.7  4334.7  4359.7  4369.7
  4374.7  4389.7  4404.7  4419.7  4449.7  4539.7  4689.6  4704.6  4744.6 4745.13
 4814.48 4884.97  4885.2 4894.52 4894.59 4909.79  5183.4 5188.77 5202.56 5202.91
 5219.59  5223.5  5292.1  5317.1  5352.1  5367.1  5382.1  5397.1  5437.1  5457.1
  5472.1  5487.1  5502.1  5587.1  5607.1  5702.1  5732.1  5767.1  5787.1    5828
   22.04   15.53   14.11    13.5   11.92    9.84    8.87    6.51    6.47    7.53
    5.88    6.22     6.1    3.51    2.19     .33   -1.98   -2.23   -2.55   -3.91
   -4.39    -4.4     1.8     4.1    2.48    2.86    2.76    3.34       3    4.14
    4.61    4.67    4.68   14.18   12.81   12.72   13.04   13.05   13.26   14.72
    6.23    3.43    4.08    3.92    4.99    4.52     4.6    3.63    5.43    8.22
   11.34   13.67   15.19      17   16.67   17.62   17.17   17.47   17.41   18.42
   21.94   15.43   14.01    13.4   11.82    9.74    8.77    6.41    6.37    7.43
    5.78    6.12       6    3.41    2.09     .23   -2.08   -2.33   -2.65   -4.01
   -4.49    -4.5     1.7       4    2.38    2.76    2.66    3.24     2.9    4.04
    4.51    4.57    4.58    7.08    5.71    5.62    5.94    6.79    6.49    7.62
    6.13    3.33    3.98    3.82    4.89    4.42     4.5    3.53    5.33    8.12
   11.24   13.57   15.09    16.9   16.57   17.52   17.07   17.37   17.31   18.32
Pier Skew, UpSta & Num, DnSta & Num=  ,4906.5, 2 ,4906.5, 2 , 0 , 0 , 0 ,,
       2       2
       4    6.74
       2       2
     3.9    6.64
Pier Skew, UpSta & Num, DnSta & Num=  ,4947.4, 2 ,4947.4, 2 , 0 , 0 , 0 ,,
       2       2
   -2.94    6.77
       2       2
   -3.04    6.67
Pier Skew, UpSta & Num, DnSta & Num=  ,4986.1, 2 ,4986.1, 2 , 0 , 0 , 0 ,,
       2       2
  -11.25    6.82
       2       2
  -11.35    6.72
Pier Skew, UpSta & Num, DnSta & Num=  ,5025.1, 2 ,5025.1, 2 , 0 , 0 , 0 ,,
       2       2
  -15.63    6.86
       2       2
  -15.73    6.76
Pier Skew, UpSta & Num, DnSta & Num=  ,5065.8, 2 ,5065.8, 2 , 0 , 0 , 0 ,,
       2       2
    -1.3     6.9
       2       2
    -1.4     6.8
Pier Skew, UpSta & Num, DnSta & Num=  ,5106.1, 2 ,5106.1, 2 , 0 , 0 , 0 ,,
       2       2
    1.41    6.95
       2       2
    1.31    6.85
Pier Skew, UpSta & Num, DnSta & Num=  ,5145, 2 ,5145, 2 , 0 , 0 , 0 ,,
       2       2
    2.18       7
       2       2
    2.08     6.9
Pier Skew, UpSta & Num, DnSta & Num=  ,5185.5, 2 ,5185.5, 2 , 0 , 0 , 0 ,,
       2       2
    5.19    7.53
       2       2
    5.09    7.43
Pier Skew, UpSta & Num, DnSta & Num=  ,5226.5, 2 ,5226.5, 2 , 0 , 0 , 0 ,,
       2       2
    2.45    4.47
       2       2
    2.35    4.37
Abutment Skew #Up #Dn= , 2 , 2
  4850.7  4885.2
    4.65    4.68
  4850.7  4885.2
    4.55    4.58
BR Coef= 1 , 1 , 0 ,1.25, 0 ,,,0.8,0,2,0,
WSPro=,,,, 1 ,,,, 0 ,,,, 0 ,,,,-1 ,-1 ,-1 , 0 , 0 , 0 , 0 , 0
BR U #Sta/Elev= 105
  3751.5   22.04  3851.5   15.53  3906.5   14.11  3916.1    13.5  3961.1   11.92
  4031.1    9.84  4046.1    8.87  4071.1    6.51  4096.1    6.47  4131.1    7.53
  4184.7    6.53  4224.7    5.88  4231.5    5.91  4294.7    6.22  4299.7     6.1
  4314.7    3.51  4319.7    2.19  4324.7     .33  4329.7   -1.98  4334.7   -2.23
  4359.7   -2.55  4362.9   -2.99  4369.7   -3.91  4374.7   -4.39  4389.7    -4.4
  4404.7     1.8  4419.7     4.1  4449.7    2.48  4539.7    2.86  4689.6    2.76
  4704.6    3.34  4744.6       3 4745.13    4.14 4814.48    4.61 4850.81    4.65
  4850.9    4.65  4851.6    4.65 4884.97    4.67  4885.2    4.68 4894.52    5.01
 4894.59    5.02 4898.26    5.15 4899.89    5.12 4909.79    4.96 4910.64    4.95
 4918.84    4.22 4924.78    3.36 4929.23     .49 4929.65    2.86  4933.9   -2.35
 4942.45   -1.62 4962.81    -2.7 4973.13   -5.95 4990.17   -11.2 5017.75  -14.01
 5026.58  -14.67 5034.57  -13.67 5040.09  -12.78 5046.52  -11.34 5049.63   -7.79
 5055.78   -1.83 5063.28    -.47 5070.77     .35 5075.01    -2.3 5080.39    2.23
 5088.66    2.93 5093.54    5.63 5098.56    5.31 5102.52    -.44 5107.11    4.63
 5131.15    1.16 5134.26    4.48 5160.14    1.62 5164.02    4.95  5183.4    6.01
 5187.99    6.76 5188.77    6.89 5198.31    6.69 5202.56    6.59 5202.91    6.59
 5219.59    6.23  5223.5    3.43  5286.4    4.03 5286.89    4.03    5287    4.03
  5292.1    4.08  5317.1    3.92  5352.1    4.99  5367.1    4.52  5367.4    4.52
  5382.1     4.6  5397.1    3.63  5437.1    5.43  5457.1    8.22  5472.1   11.34
  5487.1   13.67  5502.1   15.19  5587.1      17  5607.1   16.67    5630    16.9
  5702.1   17.62  5732.1   17.17  5767.1   17.47  5787.1   17.41    5828   18.42
BR U #Mann= 8
  3751.5      .2  3751.5      .1  4231.5     .14  4362.9     .14 4924.78    .045
 5080.39     .14  5367.4      .1    5630      .2
BR U Banks=4924.78,5080.39
BR D #Sta/Elev= 105
  3751.5   21.94  3851.5   15.43  3906.5   14.01  3916.1    13.4  3961.1   11.82
  4031.1    9.74  4046.1    8.77  4071.1    6.41  4096.1    6.37  4131.1    7.43
  4184.7    6.43  4224.7    5.78  4231.5    5.81  4294.7    6.12  4299.7       6
  4314.7    3.41  4319.7    2.09  4324.7     .23  4329.7   -2.08  4334.7   -2.33
  4359.7   -2.65  4362.9   -3.09  4369.7   -4.01  4374.7   -4.49  4389.7    -4.5
  4404.7     1.7  4419.7       4  4449.7    2.38  4539.7    2.76  4689.6    2.66
  4704.6    3.24  4744.6     2.9 4745.13    4.04 4814.48    4.51 4850.81    4.55
  4850.9    4.55  4851.6    4.55 4884.97    4.57  4885.2    4.58 4894.52    4.91
 4894.59    4.92 4898.26    5.05 4899.89    5.02 4909.79    4.86 4910.64    4.85
 4918.84    4.12 4924.78    3.26 4929.23     .39 4929.65    2.76  4933.9   -2.45
 4942.45   -1.72 4962.81    -2.8 4973.13   -6.05 4990.17   -11.3 5017.75  -14.11
 5026.58  -14.77 5034.57  -13.77 5040.09  -12.88 5046.52  -11.44 5049.63   -7.89
 5055.78   -1.93 5063.28    -.57 5070.77     .25 5075.01    -2.4 5080.39    2.13
 5088.66    2.83 5093.54    5.53 5098.56    5.21 5102.52    -.54 5107.11    4.53
 5131.15    1.06 5134.26    4.38 5160.14    1.52 5164.02    4.85  5183.4    5.91
 5187.99    6.66 5188.77    6.79 5198.31    6.59 5202.56    6.49 5202.91    6.49
 5219.59    6.13  5223.5    3.33  5286.4    3.93 5286.89    3.93    5287    3.93
  5292.1    3.98  5317.1    3.82  5352.1    4.89  5367.1    4.42  5367.4    4.42
  5382.1     4.5  5397.1    3.53  5437.1    5.33  5457.1    8.12  5472.1   11.24
  5487.1   13.57  5502.1   15.09  5587.1    16.9  5607.1   16.57    5630    16.8
  5702.1   17.52  5732.1   17.07  5767.1   17.37  5787.1   17.31    5828   18.32
BR D #Mann= 8
  3751.5      .2  3751.5      .1  4231.5     .14  4362.9     .14 4924.78    .045
 5080.39     .14  5367.4      .1    5630      .2
BR D Banks=4924.78,5080.39
BC Design=,, 0 ,, 0 ,,,,,,
BC HTab HWMax=22.11
BC Use User HTab Curves=0
BC User HTab FreeFlow(D)= 0

Type RM Length L Ch R = 1 ,2926.2  ,1,1,1
BEGIN DESCRIPTION:
Downstream Section of Bridge/Culvert/Weir
END DESCRIPTION:
XS GIS Cut Line= 6
      3169997.63     13836766.98      3170161.27     13836634.04
      3170229.62     13835971.36      3170256.15      13835600.8
      3170263.31     13835263.99      3170245.94     13834773.22
#Sta/Elev= 30
  3751.5   22.64  4071.1    7.11  4231.5    6.51  4299.7     6.7  4329.7   -1.38
  4362.9   -2.39  4389.7    -3.8  4419.7     4.7 4924.78    3.96  4933.9   -1.75
 4962.81    -2.1 4990.17   -10.6 5026.58  -14.07 5046.52  -10.74 5055.78   -1.23
 5075.01    -1.7 5080.39    2.83 5093.54    6.23 5098.56    5.91 5102.52     .16
 5107.11    5.23 5160.14    2.22 5164.02    5.55 5188.77    7.49  5223.5    4.03
  5367.4    5.12  5437.1    6.03  5502.1   15.79    5630    17.5    5828   19.02
#Mann= 8 , 1 , 0
  3751.5      .2       0  3751.5      .1       0  4231.5     .14       0
  4362.9     .14       0 4924.78    .045       0 5080.39     .14       0
  5367.4      .1       0    5630      .2       0
#XS Ineff= 2 , 0
       0    4840       7    5245       0     7.5
Permanent Ineff=
       F       F
Bank Sta=4924.78,5080.39
XS Rating Curve= 0 ,0
Exp/Cntr=0.5,0.3

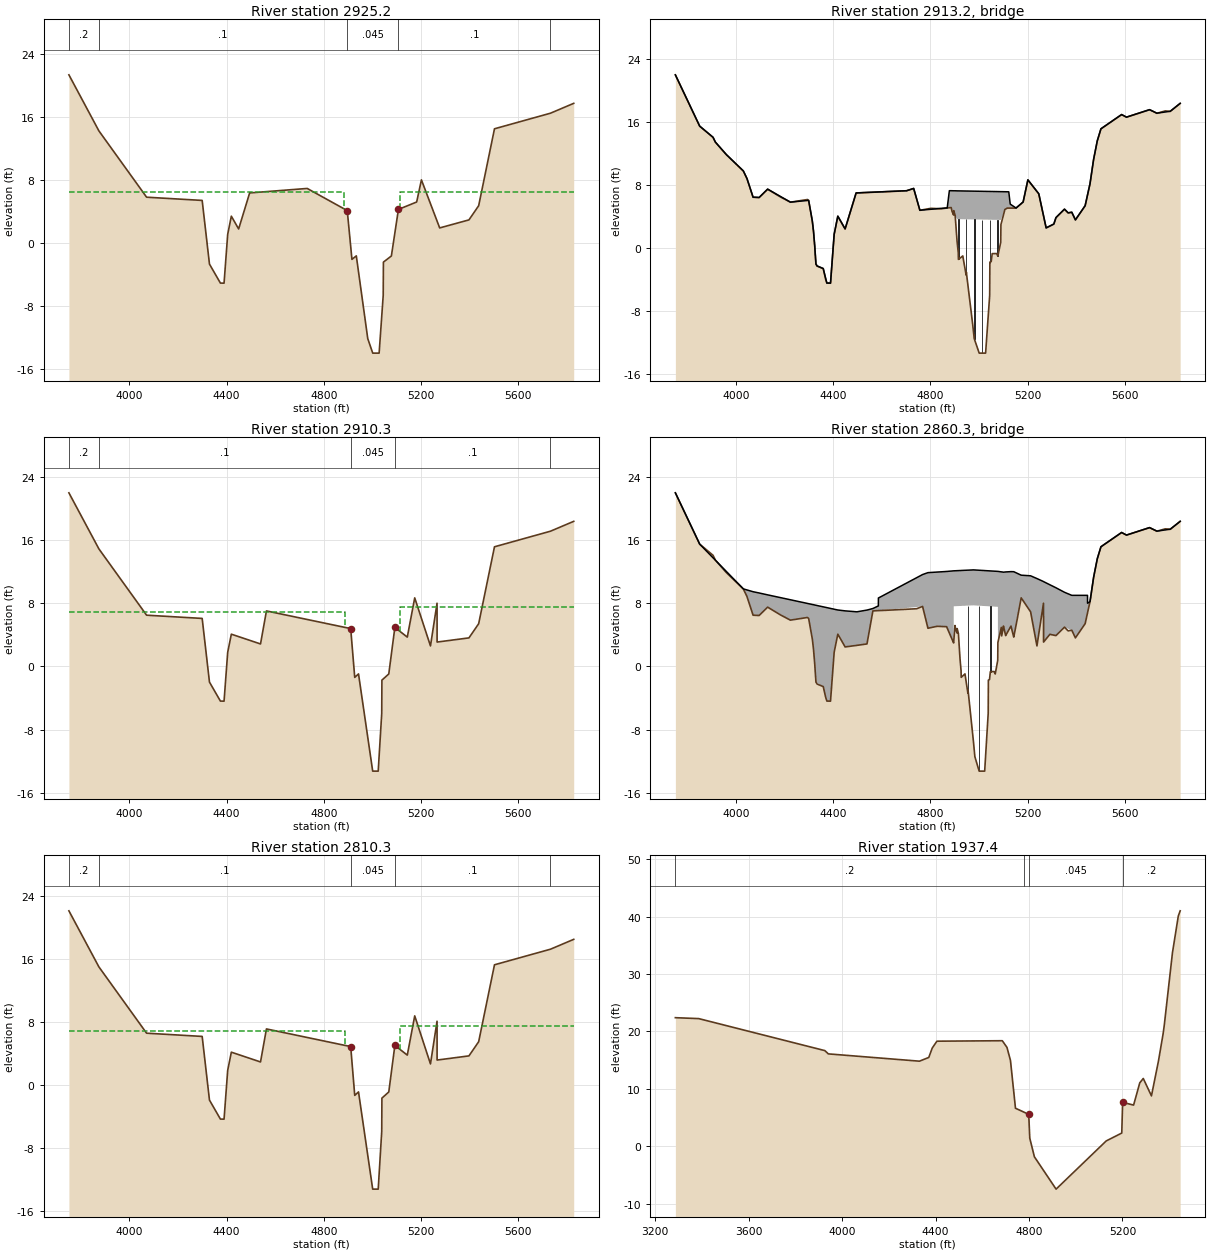
Type RM Length L Ch R = 1 ,2925.2  ,14.9,14.9,14.9
BEGIN DESCRIPTION:
Upstream Section of Bridge/Culvert/Weir
END DESCRIPTION:
XS GIS Cut Line= 6
      3169986.53     13836755.47      3170151.36     13836621.54
      3170219.72     13835958.86      3170245.07     13835589.71
       3170253.4     13835251.49      3170236.08     13834762.21
#Sta/Elev= 30
  3751.5   21.32  3874.8   14.21  4071.1    5.79  4299.7    5.38  4329.7    -2.7
  4374.7   -5.11  4389.7   -5.12  4404.7    1.08  4419.7    3.38  4449.7    1.76
 4495.03    6.33 4731.72     6.9  4896.5    4.09 4915.75    -2.1 4933.77   -1.66
 4980.86  -12.16 5001.33     -14 5027.62     -14 5044.41   -6.67 5045.23   -2.45
 5077.99   -1.67 5106.99    4.24 5182.01    5.18 5201.58    7.99 5276.68    1.89
  5397.1    2.91  5437.1    4.71  5502.1   14.47  5732.5   16.45    5828    17.7
#Mann= 5 , 1 , 0
  3751.5      .2       0  3874.8      .1       0  4896.5    .045       0
 5106.99      .1       0  5732.5      .2       0
#XS Ineff= 2 , 0
       0    4885     6.5    5115       0     6.5
Permanent Ineff=
       F       F
Bank Sta=4896.5,5106.99
XS Rating Curve= 0 ,0
Exp/Cntr=0.5,0.3

Type RM Length L Ch R = 3 ,2913.2  ,,,
BEGIN DESCRIPTION:
Pipeline - 35 Degree Skew
END DESCRIPTION:
Bridge Culvert--1,0,-1,-1, 0
Deck Dist Width WeirC Skew NumUp NumDn MinLoCord MaxHiCord MaxSubmerge Is_Ogee
10,4,2.6,0, 60, 60, , , 0.95, 0, 1,1,,
  3751.5  3851.5  3906.5  3916.1  3961.1  4031.1  4046.1  4071.1  4096.1  4131.1
  4224.7  4299.7  4314.7  4319.7  4324.7  4329.7  4334.7  4359.7  4374.7  4389.7
  4404.7  4419.7  4449.7 4495.03 4702.81 4731.72 4757.27 4869.73 4878.53 4886.02
 4896.01  4896.5 4902.48  4910.1 5090.69 5106.99 5122.93 5128.93 5152.85 5182.01
 5201.58 5246.38 5276.68  5308.3  5317.1  5352.1  5367.1  5382.1  5397.1  5437.1
  5457.1  5472.1  5487.1  5502.1  5587.1  5607.1  5702.1  5732.1  5787.1    5828
   22.04   15.53   14.11    13.5   11.92    9.84    8.87    6.51    6.47    7.53
    5.88     6.1    3.51    2.19     .33   -1.98   -2.23   -2.55   -4.39    -4.4
     1.8     4.1    2.48    7.05    7.33    7.62    4.85    5.15    7.33    7.33
    7.32    7.32    7.32    7.31    7.21     7.2    7.19    5.63    5.13     5.9
    8.71    6.94    2.61     3.1    3.92    4.99    4.52     4.6    3.63    5.43
    8.22   11.34   13.67   15.19      17   16.67   17.62   17.17   17.41   18.42
   22.03   15.52    14.1   13.49   11.91    9.83    8.86     6.5    6.46    7.52
    5.87    6.09     3.5    2.18     .32   -1.99   -2.24   -2.56    -4.4   -4.41
    1.79    4.09    2.47    7.04    7.32    7.61    4.84    5.13    5.16    5.19
    4.24     4.8    4.17    3.72    3.62    4.95    5.12    5.12    5.12    5.89
     8.7    6.93     2.6    3.09    3.91    4.98    4.51    4.59    3.62    5.42
    8.21   11.33   13.66   15.18   16.99   16.66   17.61   17.16    17.4   18.41
  3751.5  3851.5  3906.5  3916.1  3961.1  4031.1  4046.1  4071.1  4096.1  4131.1
  4224.7  4299.7  4314.7  4319.7  4324.7  4329.7  4334.7  4359.7  4374.7  4389.7
  4404.7  4419.7  4449.7 4495.03 4702.81 4731.72 4757.27 4869.73 4878.53 4886.02
 4896.01  4896.5 4902.48  4910.1 5090.69 5106.99 5122.93 5128.93 5152.85 5182.01
 5201.58 5246.38 5276.68  5308.3  5317.1  5352.1  5367.1  5382.1  5397.1  5437.1
  5457.1  5472.1  5487.1  5502.1  5587.1  5607.1  5702.1  5732.1  5787.1    5828
   22.04   15.53   14.11    13.5   11.92    9.84    8.87    6.51    6.47    7.53
    5.88     6.1    3.51    2.19     .33   -1.98   -2.23   -2.55   -4.39    -4.4
     1.8     4.1    2.48    7.05    7.33    7.62    4.85    5.15    7.33    7.33
    7.32    7.32    7.32    7.31    7.21     7.2    7.19    5.63    5.13     5.9
    8.71    6.94    2.61     3.1    3.92    4.99    4.52     4.6    3.63    5.43
    8.22   11.34   13.67   15.19      17   16.67   17.62   17.17   17.41   18.42
   22.04   15.53   14.11    13.5   11.92    9.84    8.87    6.51    6.47    7.53
    5.88     6.1    3.51    2.19     .33   -1.98   -2.23   -2.55   -4.39    -4.4
     1.8     4.1    2.48    7.05    7.33    7.62    4.85    5.14    5.17     5.2
    4.25    4.81    4.18    3.73    3.63    4.96    5.13    5.13    5.13     5.9
    8.71    6.94    2.61     3.1    3.92    4.99    4.52     4.6    3.63    5.43
    8.22   11.34   13.67   15.19      17   16.67   17.62   17.17   17.41   18.42
Pier Skew, UpSta & Num, DnSta & Num=  ,4915.7, 2 ,4915.7, 2 , 0 , 0 , 0 ,,
     2.9     2.9
   -2.35    4.72
     2.9     2.9
   -2.34    4.73
Pier Skew, UpSta & Num, DnSta & Num=  ,4947.5, 2 ,4947.5, 2 , 0 , 0 , 0 ,,
     2.9     2.9
   -4.16     4.7
     2.9     2.9
   -4.15    4.71
Pier Skew, UpSta & Num, DnSta & Num=  ,4980.9, 2 ,4980.9, 2 , 0 , 0 , 0 ,,
     2.9     2.9
  -12.58    4.68
     2.9     2.9
  -12.57    4.69
Pier Skew, UpSta & Num, DnSta & Num=  ,5012.4, 2 ,5012.4, 2 , 0 , 0 , 0 ,,
     2.9     2.9
  -14.29    4.66
     2.9     2.9
  -14.28    4.67
Pier Skew, UpSta & Num, DnSta & Num=  ,5045.2, 2 ,5045.2, 2 , 0 , 0 , 0 ,,
     2.9     2.9
   -7.23    4.64
     2.9     2.9
   -7.22    4.65
Pier Skew, UpSta & Num, DnSta & Num=  ,5078, 2 ,5078, 2 , 0 , 0 , 0 ,,
     2.9     2.9
   -1.87    4.63
     2.9     2.9
   -1.86    4.64
BR Coef= 1 , 1 , 0 ,1.25, 0 ,,,0.8,0,2,0,
WSPro=,,,, 1 ,,,, 0 ,,,, 0 ,,,,-1 ,-1 ,-1 , 0 , 0 , 0 , 0 , 0
BR U #Sta/Elev= 91
  3751.5   22.03  3851.5   15.52  3874.8   14.92  3906.5    14.1  3916.1   13.49
  3961.1   11.91  4031.1    9.83  4046.1    8.86  4071.1     6.5  4096.1    6.46
  4131.1    7.52  4184.7    6.52  4224.7    5.87  4294.7    6.21  4299.7    6.09
  4314.7     3.5  4319.7    2.18  4324.7     .32  4329.7   -1.99  4334.7   -2.24
  4359.7   -2.56  4369.7   -3.92  4374.7    -4.4  4389.7   -4.41  4404.7    1.79
  4419.7    4.09  4449.7    2.47 4495.03    7.04 4702.81    7.32 4731.72    7.61
 4757.27    4.84 4801.91    5.09 4846.22    5.04 4869.73    5.13 4878.53    5.16
 4886.02    5.19 4889.38    4.72 4893.22    4.44 4893.31    4.44 4896.01    4.24
  4896.5     4.8 4902.48    4.17  4910.1     .97 4915.18    -.56 4915.75   -1.39
 4933.77    -.95 4947.53   -3.38 4948.35      -3 4974.31   -9.59 4980.86  -11.45
 5001.33  -13.29 5012.39  -13.29 5027.62  -13.29 5044.41   -5.96 5045.23   -1.74
 5050.64   -1.67 5054.73    -.66 5072.83    -.65 5077.99    -.96 5089.87     .78
 5090.69    3.03 5105.48    4.77 5105.59    4.79 5106.99    4.95 5117.14    5.12
 5122.93    5.12 5128.93    5.12 5152.85    5.12 5182.01    5.89 5201.58     8.7
 5246.38    6.93 5276.68     2.6  5308.3    3.09  5317.1    3.91  5352.1    4.98
  5367.1    4.51  5382.1    4.59  5397.1    3.62  5437.1    5.42  5457.1    8.21
  5472.1   11.33  5487.1   13.66  5502.1   15.18  5587.1   16.99  5607.1   16.66
  5702.1   17.61  5732.1   17.16  5732.5   17.16  5767.1   17.46  5787.1    17.4
    5828   18.41
BR U #Mann= 5
  3751.5      .2  3874.8      .1  4896.5    .045 5106.99      .1  5732.5      .2
BR U Banks=4896.5,5106.99
BR D #Sta/Elev= 91
  3751.5   22.04  3851.5   15.53  3874.8   14.93  3906.5   14.11  3916.1    13.5
  3961.1   11.92  4031.1    9.84  4046.1    8.87  4071.1    6.51  4096.1    6.47
  4131.1    7.53  4184.7    6.53  4224.7    5.88  4294.7    6.22  4299.7     6.1
  4314.7    3.51  4319.7    2.19  4324.7     .33  4329.7   -1.98  4334.7   -2.23
  4359.7   -2.55  4369.7   -3.91  4374.7   -4.39  4389.7    -4.4  4404.7     1.8
  4419.7     4.1  4449.7    2.48 4495.03    7.05 4702.81    7.33 4731.72    7.62
 4757.27    4.85 4801.91     5.1 4846.22    5.05 4869.73    5.14 4878.53    5.17
 4886.02     5.2 4889.38    4.73 4893.22    4.45 4893.31    4.45 4896.01    4.25
  4896.5    4.81 4902.48    4.18  4910.1     .98 4915.18    -.55 4915.75   -1.38
 4933.77    -.94 4947.53   -3.37 4948.35   -2.99 4974.31   -9.58 4980.86  -11.44
 5001.33  -13.28 5012.39  -13.28 5027.62  -13.28 5044.41   -5.95 5045.23   -1.73
 5050.64   -1.66 5054.73    -.65 5072.83    -.64 5077.99    -.95 5089.87     .79
 5090.69    3.04 5105.48    4.78 5105.59     4.8 5106.99    4.96 5117.14    5.13
 5122.93    5.13 5128.93    5.13 5152.85    5.13 5182.01     5.9 5201.58    8.71
 5246.38    6.94 5276.68    2.61  5308.3     3.1  5317.1    3.92  5352.1    4.99
  5367.1    4.52  5382.1     4.6  5397.1    3.63  5437.1    5.43  5457.1    8.22
  5472.1   11.34  5487.1   13.67  5502.1   15.19  5587.1      17  5607.1   16.67
  5702.1   17.62  5732.1   17.17  5732.5   17.17  5767.1   17.47  5787.1   17.41
    5828   18.42
BR D #Mann= 5
  3751.5      .2  3874.8      .1  4896.5    .045 5106.99      .1  5732.5      .2
BR D Banks=4896.5,5106.99
BC Design=,, 0 ,, 0 ,,,,,,
BC HTab HWMax=21.32
BC Use User HTab Curves=0
BC User HTab FreeFlow(D)= 0

Type RM Length L Ch R = 1 ,2910.3  ,100,100,100
BEGIN DESCRIPTION:
Upstream Section of Bridge/Culvert/Weir
END DESCRIPTION:
XS GIS Cut Line= 6
      3170239.34     13836880.71      3170237.93     13836715.27
       3170284.8     13835837.85      3170295.25     13835401.06
      3170313.57     13835075.74      3170248.17     13834814.15
#Sta/Elev= 30
  3751.5   22.04  3874.8   14.93  4071.1    6.51  4299.7     6.1  4329.7   -1.98
  4374.7   -4.39  4389.7    -4.4  4404.7     1.8  4419.7     4.1  4539.7    2.86
 4564.06    7.05 4910.64    4.81 4927.25   -1.38  4942.8    -.94 5001.13  -13.28
 5023.83  -13.28 5038.32   -5.95 5039.03   -1.73 5067.31    -.95 5092.33    4.96
 5143.45    3.73 5173.99    8.71 5238.82    2.61 5265.83    8.03 5266.11     3.1
  5397.1    3.63  5437.1    5.43  5502.1   15.19  5732.5   17.17    5828   18.42
#Mann= 5 , 1 , 0
  3751.5      .2       0  3874.8      .1       0 4910.64    .045       0
 5092.33      .1       0  5732.5      .2       0
#XS Ineff= 2 , 0
       0    4886    6.86    5115       0     7.5
Permanent Ineff=
       F       F
Bank Sta=4910.64,5092.33
XS Rating Curve= 0 ,0
Exp/Cntr=0.5,0.3

Type RM Length L Ch R = 3 ,2860.3  ,,,
BEGIN DESCRIPTION:
FEDERAL ROAD - 45 Degree Skew
Structure ID: H00-1
END DESCRIPTION:
Bridge Culvert--1,0,-1,-1, 0
Deck Dist Width WeirC Skew NumUp NumDn MinLoCord MaxHiCord MaxSubmerge Is_Ogee
10,80,2.6,0, 60, 60, , , 0.95, 0, 1,1,,
  3751.5  3851.5  4031.1  4071.1  4096.1  4131.1  4224.7  4299.7  4314.7  4319.7
  4329.7  4359.7  4374.7  4389.7  4404.7  4419.7  4449.7  4498.1  4539.7 4564.06
 4586.49  4586.6 4768.39 4790.45 4867.23 4896.12 4896.35 4896.42  4977.8 5078.23
 5078.34 5092.33 5093.82  5101.1 5110.08 5131.93 5143.45 5173.99 5212.67 5238.82
 5265.83 5266.11  5292.1  5317.1  5352.1  5382.1  5397.1  5437.1  5446.8 5446.91
  5457.1  5472.1  5487.1  5502.1  5587.1  5607.1  5702.1  5732.1  5787.1    5828
   22.04   15.53    9.85    9.49    9.33    9.09    8.47    7.97    7.87    7.84
    7.77    7.57    7.47    7.37    7.27    7.17    7.06    6.94    7.16    7.36
    7.69    8.69   11.67   11.91   12.06   12.14   12.14   12.14   12.26   12.07
   12.07   12.01   12.01   11.97      12   12.04   12.03   11.59   11.51   11.16
   10.78   10.77   10.37    9.99    9.42    9.03    9.03    9.03    9.03    8.03
    8.23   11.35   13.68    15.2   17.01   16.68   17.63   17.18   17.42   18.42
   22.04   15.53    9.84    6.51    6.47    7.53    5.88     6.1    3.51    2.19
   -1.98   -2.55   -4.39    -4.4     1.8     4.1    2.48    2.68    2.86    7.05
    7.09    7.09    7.62    4.85    5.05    2.99    3.08    7.64    7.76    7.57
    3.06    4.96    3.88    5.13    3.92    5.13    3.73    8.71    6.94    2.61
    8.03     3.1    4.08    3.92    4.99     4.6    3.63    5.43    6.78     6.8
    8.22   11.34   13.67   15.19      17   16.67   17.62   17.17   17.41   18.42
  3751.5  3851.5  4031.1  4071.1  4096.1  4131.1  4224.7  4299.7  4314.7  4319.7
  4329.7  4359.7  4374.7  4389.7  4404.7  4419.7  4449.7  4498.1  4539.7 4564.06
 4586.49  4586.6 4768.39 4790.45 4867.23 4896.12 4896.35 4896.42  4977.8 5078.23
 5078.34 5092.33 5093.82  5101.1 5110.08 5131.93 5143.45 5173.99 5212.67 5238.82
 5265.83 5266.11  5292.1  5317.1  5352.1  5382.1  5397.1  5437.1  5446.8 5446.91
  5457.1  5472.1  5487.1  5502.1  5587.1  5607.1  5702.1  5732.1  5787.1    5828
   22.04   15.53    9.85    9.49    9.33    9.09    8.47    7.97    7.87    7.84
    7.77    7.57    7.47    7.37    7.27    7.17    7.06    6.94    7.16    7.36
    7.69    8.69   11.67   11.91   12.06   12.14   12.14   12.14   12.26   12.07
   12.07   12.01   12.01   11.97      12   12.04   12.03   11.59   11.51   11.16
   10.78   10.77   10.37    9.99    9.42    9.03    9.03    9.03    9.03    8.03
    8.23   11.35   13.68    15.2   17.01   16.68   17.63   17.18   17.42   18.42
   22.04   15.53    9.84    6.51    6.47    7.53    5.88     6.1    3.51    2.19
   -1.98   -2.55   -4.39    -4.4     1.8     4.1    2.48    2.68    2.86    7.05
    7.09    7.09    7.62    4.85    5.05    2.99    3.08    7.64    7.76    7.57
    3.06    4.96    3.88    5.13    3.92    5.13    3.73    8.71    6.94    2.61
    8.03     3.1    4.08    3.92    4.99     4.6    3.63    5.43    6.78     6.8
    8.22   11.34   13.67   15.19      17   16.67   17.62   17.17   17.41   18.42
Pier Skew, UpSta & Num, DnSta & Num=  ,4955.4, 2 ,4955.4, 2 , 0 , 0 , 0 ,,
     1.5     1.5
   -4.36    8.74
     1.5     1.5
   -4.36    8.74
Pier Skew, UpSta & Num, DnSta & Num=  ,5001.1, 2 ,5001.1, 2 , 0 , 0 , 0 ,,
     1.5     1.5
  -14.28    8.74
     1.5     1.5
  -14.28    8.74
Pier Skew, UpSta & Num, DnSta & Num=  ,5047.2, 2 ,5047.2, 2 , 0 , 0 , 0 ,,
     1.5     1.5
   -1.86    8.71
     1.5     1.5
   -1.86    8.71
BR Coef= 1 , 1 , 0 ,1.25, 0 ,,,0.8,0,2,0,
WSPro=,,,, 1 ,,,, 0 ,,,, 0 ,,,,-1 ,-1 ,-1 , 0 , 0 , 0 , 0 , 0
BR U #Sta/Elev= 127
  3751.5   22.04  3851.5   15.53  3874.8   14.93  3906.5   14.11  3916.1    13.5
  3961.1   11.92  4031.1    9.84  4046.1    8.87  4071.1    6.51  4096.1    6.47
  4131.1    7.53  4184.7    6.53  4224.7    5.88  4294.7    6.22  4299.7     6.1
  4314.7    3.51  4319.7    2.19  4324.7     .33  4329.7   -1.98  4334.7   -2.23
  4359.7   -2.55  4369.7   -3.91  4374.7   -4.39  4389.7    -4.4  4404.7     1.8
  4419.7     4.1  4427.9    3.66  4449.7    2.48  4498.1    2.68  4539.7    2.86
  4555.5    5.58 4564.06    7.05 4586.49    7.09  4586.6    7.09 4586.71    7.09
  4616.3    7.13  4675.6    7.22 4743.43    7.33  4744.6    7.34 4768.39    7.62
 4790.45    4.85  4811.3    4.99 4828.98     5.1  4849.7    5.07  4853.5    5.07
 4867.23    5.05 4896.12    2.99 4896.23    3.03 4896.35    3.08 4896.42    3.11
 4901.59     5.2 4904.48    4.73 4910.21    4.25 4910.64    4.81  4915.8    4.18
  4916.4    3.89 4922.37     .98 4926.75    -.55 4927.25   -1.38  4942.8    -.94
 4954.68   -3.37 4955.39   -2.99  4977.8   -9.58  4980.9   -10.6 4983.46  -11.44
 5001.13  -13.28 5010.68  -13.28 5023.83  -13.28 5038.32   -5.95 5039.03   -1.73
 5043.69   -1.66  5046.2    -.94 5047.23    -.65 5062.85    -.64 5067.31    -.95
 5077.56     .79 5078.06    2.66 5078.16    3.04 5078.23    3.05 5078.34    3.06
 5092.33    4.96 5093.82    3.88  5101.1    5.13  5104.5    4.67  5108.2    4.17
 5110.08    3.92 5131.93    5.13  5142.2    3.88 5143.45    3.73  5157.1     5.9
    5164    7.05 5173.99    8.71  5195.8    7.71 5212.67    6.94 5238.82    2.61
  5253.9    5.64 5265.83    8.03 5266.11     3.1  5292.1    4.08  5315.2    3.93
  5317.1    3.92  5352.1    4.99  5367.1    4.52  5375.9    4.57  5382.1     4.6
  5397.1    3.63  5437.1    5.43 5446.69    6.77  5446.8    6.78 5446.91     6.8
  5457.1    8.22  5472.1   11.34  5487.1   13.67  5502.1   15.19  5558.4   16.39
  5587.1      17  5607.1   16.67  5702.1   17.62  5732.1   17.17  5732.5   17.17
  5767.1   17.47  5773.4   17.45  5787.1   17.41  5798.4   17.69  5808.4   17.94
  5813.4   18.06    5828   18.42
BR U #Mann= 5
  3751.5      .2  3874.8      .1 4910.64    .045 5092.33      .1  5732.5      .2
BR U Banks=4910.64,5092.33
BR D #Sta/Elev= 127
  3751.5   22.04  3851.5   15.53  3874.8   14.93  3906.5   14.11  3916.1    13.5
  3961.1   11.92  4031.1    9.84  4046.1    8.87  4071.1    6.51  4096.1    6.47
  4131.1    7.53  4184.7    6.53  4224.7    5.88  4294.7    6.22  4299.7     6.1
  4314.7    3.51  4319.7    2.19  4324.7     .33  4329.7   -1.98  4334.7   -2.23
  4359.7   -2.55  4369.7   -3.91  4374.7   -4.39  4389.7    -4.4  4404.7     1.8
  4419.7     4.1  4427.9    3.66  4449.7    2.48  4498.1    2.68  4539.7    2.86
  4555.5    5.58 4564.06    7.05 4586.49    7.09  4586.6    7.09 4586.71    7.09
  4616.3    7.13  4675.6    7.22 4743.43    7.33  4744.6    7.34 4768.39    7.62
 4790.45    4.85  4811.3    4.99 4828.98     5.1  4849.7    5.07  4853.5    5.07
 4867.23    5.05 4896.12    2.99 4896.23    3.03 4896.35    3.08 4896.42    3.11
 4901.59     5.2 4904.48    4.73 4910.21    4.25 4910.64    4.81  4915.8    4.18
  4916.4    3.89 4922.37     .98 4926.75    -.55 4927.25   -1.38  4942.8    -.94
 4954.68   -3.37 4955.39   -2.99  4977.8   -9.58  4980.9   -10.6 4983.46  -11.44
 5001.13  -13.28 5010.68  -13.28 5023.83  -13.28 5038.32   -5.95 5039.03   -1.73
 5043.69   -1.66  5046.2    -.94 5047.23    -.65 5062.85    -.64 5067.31    -.95
 5077.56     .79 5078.06    2.66 5078.16    3.04 5078.23    3.05 5078.34    3.06
 5092.33    4.96 5093.82    3.88  5101.1    5.13  5104.5    4.67  5108.2    4.17
 5110.08    3.92 5131.93    5.13  5142.2    3.88 5143.45    3.73  5157.1     5.9
    5164    7.05 5173.99    8.71  5195.8    7.71 5212.67    6.94 5238.82    2.61
  5253.9    5.64 5265.83    8.03 5266.11     3.1  5292.1    4.08  5315.2    3.93
  5317.1    3.92  5352.1    4.99  5367.1    4.52  5375.9    4.57  5382.1     4.6
  5397.1    3.63  5437.1    5.43 5446.69    6.77  5446.8    6.78 5446.91     6.8
  5457.1    8.22  5472.1   11.34  5487.1   13.67  5502.1   15.19  5558.4   16.39
  5587.1      17  5607.1   16.67  5702.1   17.62  5732.1   17.17  5732.5   17.17
  5767.1   17.47  5773.4   17.45  5787.1   17.41  5798.4   17.69  5808.4   17.94
  5813.4   18.06    5828   18.42
BR D #Mann= 5
  3751.5      .2  3874.8      .1 4910.64    .045 5092.33      .1  5732.5      .2
BR D Banks=4910.64,5092.33
BC Design=,, 0 ,, 0 ,,,,,,
BC HTab HWMax=22.04
BC Use User HTab Curves=0
BC User HTab FreeFlow(D)= 0

Type RM Length L Ch R = 1 ,2810.3  ,872.9,872.9,872.9
BEGIN DESCRIPTION:
Downstream Section of Bridge/Culvert/Weir
END DESCRIPTION:
XS GIS Cut Line= 6
      3170308.49     13836952.94      3170307.07     13836787.51
      3170353.94     13835910.09      3170364.39      13835473.3
      3170382.71     13835147.98      3170317.32     13834886.39
#Sta/Elev= 30
  3751.5   22.11  3874.8      15  4071.1    6.58  4299.7    6.17  4329.7   -1.91
  4374.7   -4.32  4389.7   -4.33  4404.7    1.87  4419.7    4.17  4539.7    2.93
 4564.06    7.12 4910.64    4.88 4927.25   -1.31  4942.8    -.87 5001.13  -13.21
 5023.83  -13.21 5038.32   -5.88 5039.03   -1.66 5067.31    -.88 5092.33    5.03
 5143.45     3.8 5173.99    8.78 5238.82    2.68 5265.83     8.1 5266.11    3.17
  5397.1     3.7  5437.1     5.5  5502.1   15.26  5732.5   17.24    5828   18.49
#Mann= 5 , 1 , 0
  3751.5      .2       0  3874.8      .1       0 4910.64    .045       0
 5092.33      .1       0  5732.5      .2       0
#XS Ineff= 2 , 0
       0    4886    6.86    5115       0     7.5
Permanent Ineff=
       F       F
Bank Sta=4910.64,5092.33
XS Rating Curve= 0 ,0
Exp/Cntr=0.5,0.3

Type RM Length L Ch R = 1 ,1937.4  ,0,0,0
BEGIN DESCRIPTION:
Cross Section 1937.4
END DESCRIPTION:
XS GIS Cut Line= 4
      3171134.46     13837765.11      3171149.28      13836675.4
      3171110.58     13835832.73      3171050.29     13835612.84
#Sta/Elev= 30
  3285.7    22.4  3385.7   22.24  3925.7   16.67  3940.7    16.1  4330.7   14.83
  4370.7   15.48  4385.5   17.11  4405.5   18.31  4685.5   18.39  4705.5   17.23
  4720.5   14.96  4741.9    6.64  4777.2    5.98  4798.7    5.57  4803.1    1.44
  4822.9   -1.81  4915.8   -7.44  5130.5     .95    5197    2.32  5200.7    7.66
  5247.7    7.19  5274.1   11.06  5289.1   11.82  5324.1    8.79  5354.1   14.85
  5374.1   19.61  5379.1   21.11  5414.1   33.72  5439.1    40.1  5447.1      41
#Mann= 4 , 1 , 0
  3285.7      .2       0  4777.2     .14       0  4798.7    .045       0
  5200.7      .2       0
Bank Sta=4798.7,5200.7
XS Rating Curve= 0 ,0
Exp/Cntr=0.3,0.1

Chan Stop Cuts=-1
Use User Specified Reach Order=0
Composite Channel Slope=5